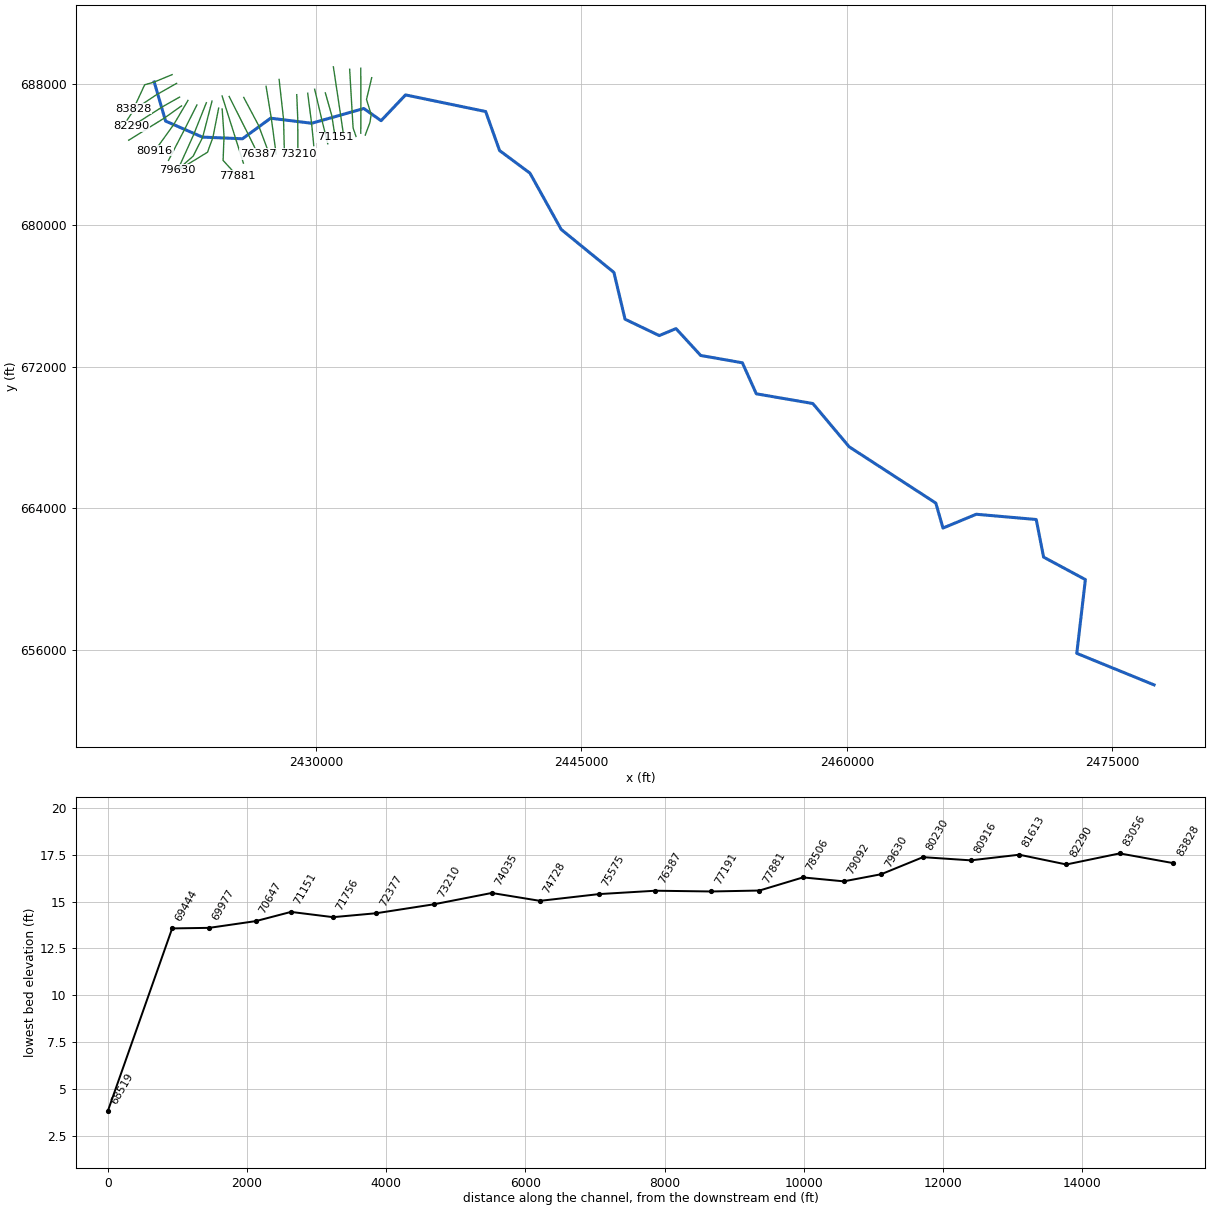
--- Black Mingo Creek.prj (project) ---

Proj Title=Black Mingo Creek Limited Detail Study
Current Plan=p06
Current HD=h01
Default Exp/Contr=0.3,0.1
English Units
Geom File=g01
Geom File=g02
Geom File=g03
Geom File=g04
Geom File=g05
Flow File=f01
Flow File=f02
Plan File=p02
Plan File=p03
Plan File=p01
Plan File=p05
Plan File=p06
Plan File=p04
HD File=h01
Y Axis Title=Elevation
X Axis Title(PF)=Main Channel Distance
X Axis Title(XS)=Station
BEGIN DESCRIPTION:
Black Mingo Creek
END DESCRIPTION:
DSS Export Rating Curves= 0
DSS Export Rating Curve Sorted= 0
DSS Export Volume Flow Curves= 0
DXF OffsetX= 0
DXF OffsetY= 0
DXF ScaleX= 1
DXF ScaleY= 10

--- Black Mingo Creek.p06 (plan) ---

Plan Title=Proposed SCDOT
Program Version=4.10
Short Identifier=PROP SCDOT
Geom File=g04
Flow File=f02
Subcritical Flow
K Sum by GR= 0
Std Step Tol= 0.01
Critical Tol= 0.01
Num of Std Step Trials= 20
Max Error Tol= 0.3
Flow Tol Ratio= 0.001
Split Flow NTrial= 30
Split Flow Tol= 0.02
Split Flow Ratio= 0.02
Log Output Level= 0
Friction Slope Method= 1
Unsteady Friction Slope Method= 2
Unsteady Bridges Friction Slope Method= 1
Parabolic Critical Depth
Global Vel Dist= 0 , 0 , 0
Global Log Level= 0
CheckData=True
Encroach Param=-1 ,0,0, 0
Computation Interval=1HOUR
Output Interval=1HOUR
Run HTab= 0
Run UNet= 0
Run PostProcess= 0
Run WQNet= 0
UNET Theta= 1
UNET Theta Warmup= 1
UNET ZTol= 0.02
UNET ZSATol= 0.05
UNET MxIter= 20
UNET MaxInSteps= 0
UNET DtIC= 0
UNET DtMin= 0
UNET MaxCRTS= 20
UNET WFStab= 2
UNET SFStab= 1
UNET WFX= 1
UNET SFX= 1
UNET DSS MLevel= 4
UNET DZMax Abort= 100
UNET Convert EG Bridges= 0
UNET Use Existing IB Tables=-1
UNET Froude Reduction=False
UNET Froude Limit= 1
UNET Froude Power= 10
UNET Time Slicing=0,0, 5
UNET Junction Losses=0
Instantaneous Interval=1HOUR
Write IC File= 0
Write IC File at Sim End=0
Echo Input=False
Echo Parameters=False
Echo Output=False
Write Detailed= 0
WQ AD Non Conservative
WQ ULTIMATE=-1
WQ Max Comp Step=1HOUR
WQ Output Interval=15MIN
WQ Output Selected Increments= 0
WQ Output face flow=0
WQ Output face velocity=0
WQ Output face area=0
WQ Output face dispersion=0
WQ Output cell volume=0
WQ Output cell surface area=0
WQ Output cell continuity=0
WQ Output cumulative cell continuity=0
WQ Output face conc=0
WQ Output face dconc_dx=0
WQ Output face courant=0
WQ Output face peclet=0
WQ Output face adv mass=0
WQ Output face disp mass=0
WQ Output cell mass=0
WQ Output cell source sink temp=0
WQ Output cell source sink nsm=0
WQ Output MaxMinRange=-1
WQ Daily Max Min Mean=-1
WQ Daily Range=0
WQ Daily Time=0
WQ Create Restart=0
WQ Fixed Restart=0
WQ System Summary=0
WQ Use Fixed Temperature=0
Sorting and Armoring Iterations= 10
XS Update Threshold= 0.02
Hydraulics Update Threshold= 0.02
Energy Slope Method= 1
Volume Change Method= 0
XS Weighting Method= 0
Number of US Weighted Cross Sections= 1
Number of DS Weighted Cross Sections= 1
Upstream XS Weight=0.25
Main XS Weight=0.5
Downstream XS Weight=0.25
Number of DS XS's Weighted with US Boundary= 1
Upstream Boundary Weight= 1
Weight of XSs Associated with US Boundary= 0
Number of US XS's Weighted with DS Boundary= 1
Downstream Boundary Weight= 0.5
Weight of XSs Associated with DS Boundary= 0.5
Sediment Output Level= 4
Mass or Volume Output= 0
Output Increment Type= 1
Profile and TS Output Increment= 10
XS Output Flag= 0
XS Output Increment= 10
Disregard all LS=0
Disregard all Conn=0
Disregard all Breaches=0
Disregard all Pumps=0

--- Black Mingo Creek.p01 (plan) ---

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Plan Title=Revised Effective
Short Identifier=REM
Geom File=g04
Flow File=f01

--- Black Mingo Creek.p02 (plan) ---

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Plan Title=Duplicate Effective
Short Identifier=DEM
Geom File=g01
Flow File=f01

--- Black Mingo Creek.p03 (plan) ---

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Plan Title=Corrected Effective
Short Identifier=CEM
Geom File=g02
Flow File=f01

--- Black Mingo Creek.p04 (plan) ---

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Plan Title=Natural SCDOT
Short Identifier=NAT
Geom File=g05
Flow File=f02

--- Black Mingo Creek.p05 (plan) ---

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Plan Title=Existing SCDOT
Short Identifier=EX SCDOT
Geom File=g02
Flow File=f02

--- Black Mingo Creek.f02 (steady flow) ---

Flow Title=SCDOT Multi
Program Version=4.10
Number of Profiles= 6
Profile Names=2,10,25,50,100 FEMA,500
River Rch & RM=Black Mingo Cree,Reach-1         ,83828
     976    2450    3310    4060    4873    6700
River Rch & RM=Black Mingo Cree,Reach-1         ,80916
    1020    2560    3440    4220    5058    6970
River Rch & RM=Black Mingo Cree,Reach-1         ,77881
    1160    2890    3880    4750    5677    7820
River Rch & RM=Black Mingo Cree,Reach-1         ,68519
    1250    3100    4160    5090    6349    8350
River Rch & RM=Black Mingo Cree,Reach-1         ,56571
    1460    3600    4820    5890    7039    9640
River Rch & RM=Black Mingo Cree,Reach-1         ,47130
    1490    3670    4900    5990    7173    9800
River Rch & RM=Black Mingo Cree,Reach-1         ,38116
    1540    3780    5050    6170    7366   10100
Boundary for River Rch & Prof#=Black Mingo Cree,Reach-1         , 1
Up Type= 0
Dn Type= 3
Dn Slope=0.0001
Boundary for River Rch & Prof#=Black Mingo Cree,Reach-1         , 2
Up Type= 0
Dn Type= 3
Dn Slope=0.0001
Boundary for River Rch & Prof#=Black Mingo Cree,Reach-1         , 3
Up Type= 0
Dn Type= 3
Dn Slope=0.0001
Boundary for River Rch & Prof#=Black Mingo Cree,Reach-1         , 4
Up Type= 0
Dn Type= 3
Dn Slope=0.0001
Boundary for River Rch & Prof#=Black Mingo Cree,Reach-1         , 5
Up Type= 0
Dn Type= 3
Dn Slope=0.0001
Boundary for River Rch & Prof#=Black Mingo Cree,Reach-1         , 6
Up Type= 0
Dn Type= 3
Dn Slope=0.0001
DSS Import GetInterval= 0
DSS Import GetPeak= 0
DSS Import FillOption= 0

--- Black Mingo Creek.f01 (steady flow) ---

Flow Title=100-year Single
Number of Profiles=1
Profile Names=100-year
River Rch & RM= Black Mingo Cree,Reach-1,83828
    4873
River Rch & RM= Black Mingo Cree,Reach-1,80916
    5058
River Rch & RM= Black Mingo Cree,Reach-1,77881
    5677
River Rch & RM= Black Mingo Cree,Reach-1,68519
    6349
River Rch & RM= Black Mingo Cree,Reach-1,56571
    7039
River Rch & RM= Black Mingo Cree,Reach-1,47130
    7173
River Rch & RM= Black Mingo Cree,Reach-1,38116
    7366
River Rch & RM= Black Mingo Cree,Reach-1,33183
    7581
River Rch & RM= Black Mingo Cree,Reach-1,25515
    7803
River Rch & RM= Black Mingo Cree,Reach-1,24235
    7836
River Rch & RM= Black Mingo Cree,Reach-1,17315
    8411
River Rch & RM= Black Mingo Cree,Reach-1,12658
    8591
River Rch & RM= Black Mingo Cree,Reach-1,3757
    8667
Boundary for River Rch & Prof#=Black Mingo Cree,Reach-1,1
Up Type=0
Dn Type=3
Dn Slope=0.0001

--- Black Mingo Creek.g04 (geometry) ---

Geom Title=Revised Effective
Program Version=4.10

River Reach=Black Mingo Cree,Reach-1
Reach XY= 30
      2420849.56       688109.49      2421490.51       685900.43
      2423569.34       684994.53      2425837.44       684899.58
      2427430.54       686062.47      2429751.18        685776.5
      2432696.54        686611.7      2433673.96       685922.22
      2435055.37       687380.23      2439586.46       686440.58
      2440372.41       684233.69      2442089.41       682956.34
      2443856.66       679771.13      2446836.24       677339.68
      2447465.75       674693.54      2449399.25       673767.41
       2450346.4        674161.7      2451743.17       672641.73
      2454097.76       672228.85      2454886.47       670473.21
      2458081.67       669924.42      2460132.65       667478.76
      2465033.36       664293.61       2465437.7       662881.19
      2467321.97       663660.84      2470710.26       663363.94
      2471126.93       661236.92      2473488.69       659965.55
       2473002.6       655793.69      2477371.84       654009.36

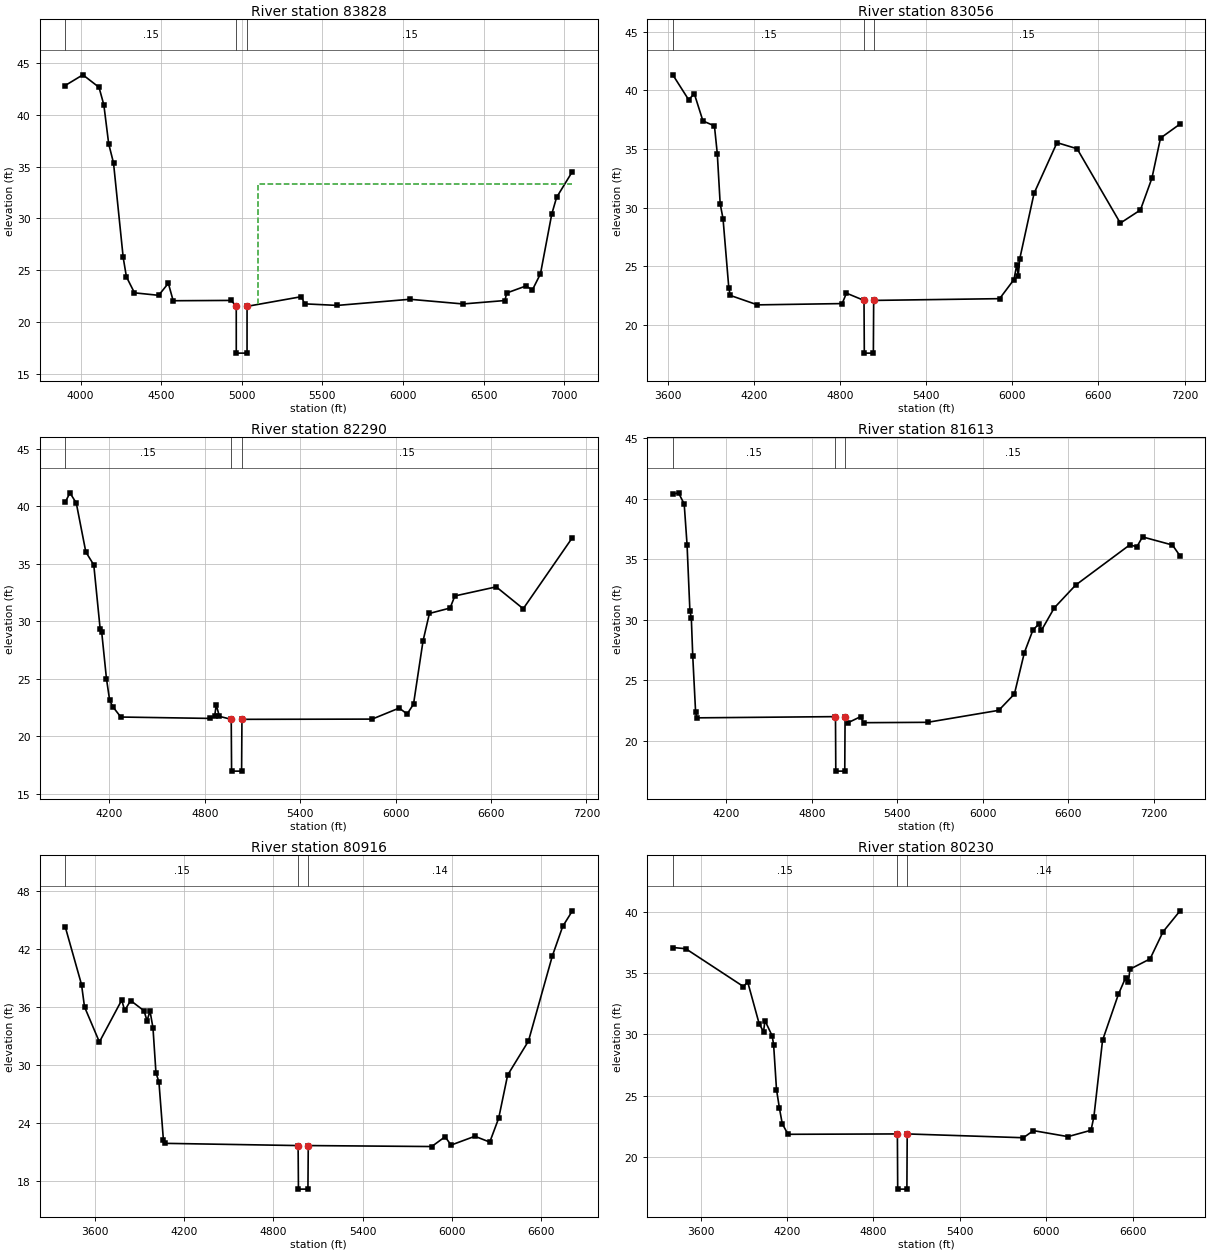
Type RM Length L Ch R = 1 ,83828   ,772,772,772
BEGIN DESCRIPTION:
Black Mingo Creek 168.0
END DESCRIPTION:
XS GIS Cut Line= 4
      2421861.65       688527.77      2420849.52       688109.09
      2420308.69       687953.19      2419684.46        686602.3
#Sta/Elev= 30
  3904.7   42.79  4014.7   43.82  4114.7   42.62  4144.7   40.93  4174.7   37.19
  4204.7   35.34  4264.7   26.25  4284.7   24.39  4334.7   22.85  4484.7   22.61
  4544.7   23.77  4574.7   22.09  4934.7   22.12    4966   21.55  4966.1   17.05
  5032.9   17.05    5033   21.55    5370   22.48    5390   21.79  5592.9   21.64
  6042.9   22.23  6372.9   21.78  6632.9   22.11  6642.9   22.83  6762.9   23.51
  6802.9   23.13  6852.9   24.68  6922.9   30.42  6952.9   32.03    7051   34.52
#Mann= 3 ,-1 , 0
  3904.7     .15       0    4966     .05       0    5033     .15       0
#XS Ineff= 2 , 0
       0                    5100       0   33.32
Permanent Ineff=
       F       F
Bank Sta=4966,5033
XS Rating Curve= 0 ,0
Exp/Cntr=0.3,0.1

Type RM Length L Ch R = 1 ,83056   ,766,766,766
BEGIN DESCRIPTION:
Black Mingo Creek 167.0
END DESCRIPTION:
XS GIS Cut Line= 4
      2422114.52       688033.51      2420925.76       687358.08
        2419710.       686547.57      2419318.28       685959.98
#Sta/Elev= 30
    3634   41.33    3744   39.21    3784   39.71    3844   37.39    3924   36.97
    3944    34.6    3964   30.33    3984   29.04    4024   23.17    4034    22.5
    4224   21.69    4814    21.8    4844   22.69  4966.3   22.07  4968.5   17.57
  5031.5   17.57  5033.7   22.07  5911.2   22.22  6011.2   23.85  6031.2   25.13
  6041.2   24.16  6051.2    25.6  6151.2   31.21  6311.2   35.54  6451.2   35.02
  6752.4   28.67  6892.4   29.79  6972.4    32.5  7032.4   35.93  7168.6   37.13
#Mann= 3 ,-1 , 0
    3634     .15       0  4966.3     .05       0  5033.7     .15       0
Bank Sta=4966.3,5033.7
XS Rating Curve= 0 ,0
Exp/Cntr=0.3,0.1

Type RM Length L Ch R = 1 ,82290   ,677,677,677
BEGIN DESCRIPTION:
Black Mingo Creek 166.0
END DESCRIPTION:
XS GIS Cut Line= 3
      2422283.36       687256.77      2421351.27       686729.94
      2419561.42       685595.24
#Sta/Elev= 30
  3921.9   40.33  3951.9   41.16  3991.9   40.27  4051.9   36.02  4101.9    34.9
  4141.9   29.35  4151.9   29.04  4181.9   24.98  4201.9   23.12  4221.9   22.57
  4271.9   21.68  4831.9   21.56  4861.9   21.73  4871.9   22.74  4891.9   21.74
  4966.3   21.48  4968.5   16.98  5031.5   16.98  5033.7   21.48  5852.6    21.5
  6022.6   22.46  6072.6   21.94  6112.6    22.8  6172.6    28.3  6212.6   30.68
  6342.6   31.15  6372.6    32.2  6632.6   32.99  6802.6   31.09  7111.8   37.27
#Mann= 3 ,-1 , 0
  3921.9     .15       0  4966.3     .05       0  5033.7     .15       0
Bank Sta=4966.3,5033.7
XS Rating Curve= 0 ,0
Exp/Cntr=0.3,0.1

Type RM Length L Ch R = 1 ,81613   ,697,697,697
BEGIN DESCRIPTION:
Black Mingo Creek 164.0
END DESCRIPTION:
XS GIS Cut Line= 3
       2422392.2       686758.99      2421439.08       686081.53
      2419406.03       684818.48
#Sta/Elev= 30
  3823.7   40.37  3863.7   40.48  3903.7   39.56  3923.7   36.21  3943.7   30.75
  3953.7   30.15  3963.7   27.02  3983.7   22.39  3993.7    21.9  4966.3      22
  4968.5    17.5  5031.5    17.5  5033.7      22  5053.1   21.49  5143.1      22
  5163.1    21.5  5613.1   21.53  6113.1   22.52  6223.1   23.87  6293.1   27.29
  6353.1   29.15  6393.1   29.63  6413.1   29.13  6503.1   30.98  6653.1   32.86
  7033.1   36.18  7083.1   36.03  7123.1   36.84  7333.1   36.17  7386.5   35.27
#Mann= 3 ,-1 , 0
  3823.7     .15       0  4966.3     .05       0  5033.7     .15       0
Bank Sta=4966.3,5033.7
XS Rating Curve= 0 ,0
Exp/Cntr=0.3,0.1

Type RM Length L Ch R = 1 ,80916   ,686,686,686
BEGIN DESCRIPTION:
Black Mingo Creek 163.0
END DESCRIPTION:
XS GIS Cut Line= 3
      2422756.16       687067.67      2421958.01       685713.03
      2420885.24       684224.14
#Sta/Elev= 30
    3401   44.33    3511   38.33    3531   36.03    3631    32.4    3781   36.73
    3801   35.66    3841   36.68    3931   35.62    3951   34.59    3971   35.61
    3991   33.85    4011   29.21    4031   28.27    4061   22.27    4071   21.93
  4965.9    21.7  4968.1    17.2  5031.9    17.2  5034.1    21.7  5863.3    21.6
  5953.3   22.61  5993.3   21.75  6153.3   22.66  6253.3   22.06  6313.3   24.53
  6373.3   28.98  6513.3    32.5  6673.3   41.27  6743.3   44.34  6808.4   45.95
#Mann= 3 ,-1 , 0
    3401     .15       0  4965.9     .05       0  5034.1     .14       0
Bank Sta=4965.9,5034.1
XS Rating Curve= 0 ,0
Exp/Cntr=0.3,0.1

Type RM Length L Ch R = 1 ,80230   ,600,600,600
BEGIN DESCRIPTION:
Black Mingo Creek 162.0
END DESCRIPTION:
XS GIS Cut Line= 3
      2423262.72         686811.      2422540.01        685379.1
      2421655.23       683677.09
#Sta/Elev= 30
  3406.5   37.07  3496.5   36.97  3896.5   33.89  3926.5   34.26  4006.5   30.84
  4036.5   30.21  4046.5   31.11  4096.5   29.86  4106.5   29.15  4126.5   25.49
  4146.5   23.99  4166.5    22.7  4206.5   21.84  4965.9   21.87  4968.1   17.37
  5031.9   17.37  5034.1   21.87  5840.5   21.56  5910.5   22.14  6150.5   21.65
  6310.5   22.17  6330.5   23.28  6390.5    29.5  6500.5   33.25  6550.5    34.6
  6570.5   34.25  6580.5    35.3  6720.5   36.14  6810.5   38.35  6928.7   40.06
#Mann= 3 ,-1 , 0
  3406.5     .15       0  4965.9     .05       0  5034.1     .14       0
Bank Sta=4965.9,5034.1
XS Rating Curve= 0 ,0
Exp/Cntr=0.3,0.1

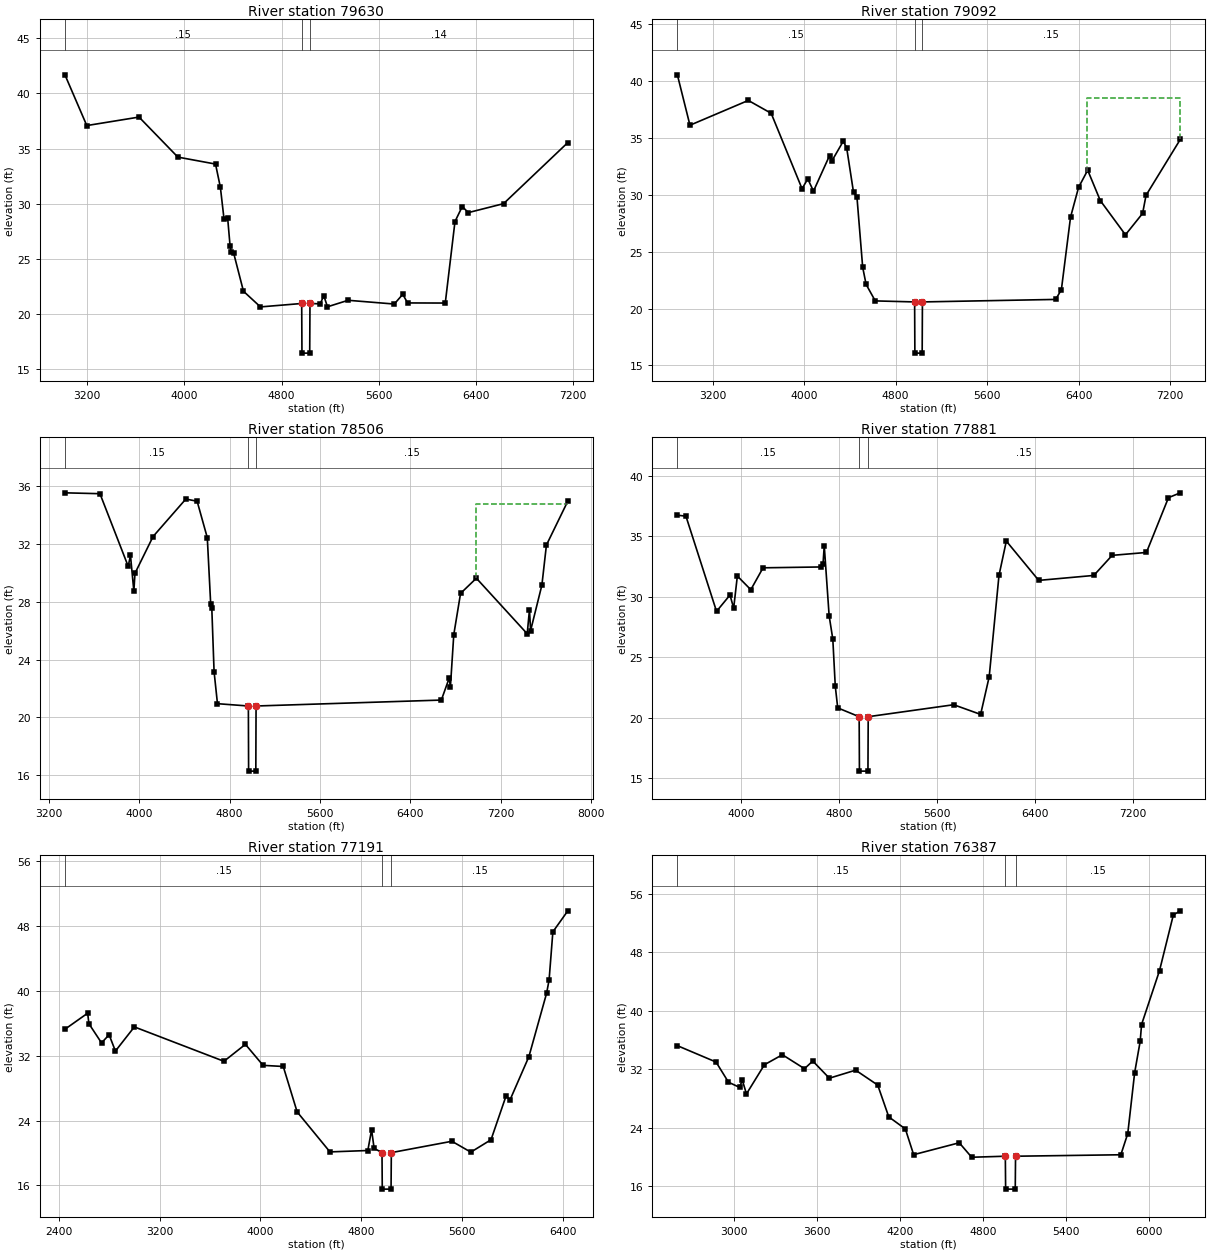
Type RM Length L Ch R = 1 ,79630   ,538,538,538
BEGIN DESCRIPTION:
Black Mingo Creek 161.0
END DESCRIPTION:
XS GIS Cut Line= 3
       2423796.3       686939.34      2423060.08       685088.67
      2422175.29       683129.97
#Sta/Elev= 30
  3016.4   41.69  3196.4   37.09  3626.4   37.86  3946.4   34.23  4256.4    33.6
  4296.4   31.49  4326.4   28.61  4356.4   28.69  4376.4   26.14  4386.4   25.62
  4406.4    25.5  4486.4   22.07  4626.4   20.65  4965.9   20.96  4968.1   16.46
  5031.9   16.46  5034.1   20.96  5118.1   20.93  5148.1   21.66  5178.1   20.66
  5348.1   21.25  5728.1   20.91  5798.1   21.79  5838.1   21.01  6148.1      21
  6228.1   28.39  6288.1   29.75  6338.1    29.2  6628.1   30.01  7157.4   35.55
#Mann= 3 ,-1 , 0
  3016.4     .15       0  4965.9     .05       0  5034.1     .14       0
Bank Sta=4965.9,5034.1
XS Rating Curve= 0 ,0
Exp/Cntr=0.3,0.1

Type RM Length L Ch R = 1 ,79092   ,586,586,586
BEGIN DESCRIPTION:
Black Mingo Creek 160.0
END DESCRIPTION:
XS GIS Cut Line= 4
       2424117.3       687033.92      2423588.12       684985.69
      2423052.72       683921.12      2422237.21       683198.98
#Sta/Elev= 30
  2891.8   40.54  3001.8   36.11  3511.8   38.29  3711.8   37.16  3981.8   30.53
  4031.8   31.39  4081.8   30.32  4221.8   33.43  4241.8   32.96  4341.8    34.7
  4371.8   34.13  4431.8   30.21  4461.8   29.79  4511.8   23.63  4541.8   22.12
  4621.8   20.67  4965.9   20.58  4968.1   16.08  5031.9   16.08  5034.1   20.58
  6198.9    20.8  6248.9   21.66  6328.9   28.03  6398.9   30.64  6478.9   32.16
  6588.9   29.49  6808.9   26.48  6958.9   28.36  6988.9   29.95  7288.2   34.86
#Mann= 3 ,-1 , 0
  2891.8     .15       0  4965.9     .05       0  5034.1     .15       0
#XS Ineff= 2 , 0
       0                  6471.7       0   38.52
Permanent Ineff=
       F       F
Bank Sta=4965.9,5034.1
XS Rating Curve= 0 ,0
Exp/Cntr=0.3,0.1

Type RM Length L Ch R = 1 ,78506   ,625,625,625
BEGIN DESCRIPTION:
Black Mingo Creek 158.0
END DESCRIPTION:
XS GIS Cut Line= 4
      2424491.97       686635.37       2424167.1       684979.46
      2423862.05       684139.01      2422268.27       683161.58
#Sta/Elev= 30
  3342.4   35.52  3652.4   35.46  3902.4   30.44  3922.4    31.2  3952.4   28.72
  3962.4   29.96  4122.4    32.5  4412.4   35.09  4512.4   34.94  4602.4   32.42
  4632.4   27.84  4642.4   27.53  4662.4   23.17  4692.4   20.95  4965.9   20.79
  4968.1   16.29  5031.9   16.29  5034.1   20.79    6674    21.2    6744   22.73
    6754   22.09    6784   25.72    6844   28.57    6984   29.62    7434   25.78
    7454   27.45    7464      26    7564   29.15    7604   31.91  7793.6   34.95
#Mann= 3 ,-1 , 0
  3342.4     .15       0  4965.9     .05       0  5034.1     .15       0
#XS Ineff= 2 , 0
       0                  6981.5       0   34.74
Permanent Ineff=
       F       F
Bank Sta=4965.9,5034.1
XS Rating Curve= 0 ,0
Exp/Cntr=0.3,0.1

Type RM Length L Ch R = 1 ,77881   ,690,690,690
BEGIN DESCRIPTION:
Black Mingo Creek 157.0
END DESCRIPTION:
XS GIS Cut Line= 4
      2424690.51       686583.44       2424795.6       685059.59
      2424743.05       683675.89      2425548.73        682791.4
#Sta/Elev= 30
  3477.8   36.75  3547.8   36.67  3797.8    28.8  3907.8   30.15  3937.8   29.06
  3967.8   31.72  4077.8   30.59  4177.8    32.4  4647.8   32.47  4667.8   32.72
  4677.8   34.23  4717.8   28.43  4747.8    26.5  4767.8   22.62  4787.8   20.82
    4963   20.09  4965.2   15.59  5034.8   15.59    5037   20.09  5735.3   21.08
  5955.3   20.28  6025.3   23.39  6105.3   31.77  6165.3   34.61    6430   31.36
    6880   31.77    7030   33.43    7310   33.67    7490    38.2  7586.4    38.6
#Mann= 3 ,-1 , 0
  3477.8     .15       0    4963     .05       0    5037     .15       0
Bank Sta=4963,5037
XS Rating Curve= 0 ,0
Exp/Cntr=0.3,0.1

Type RM Length L Ch R = 1 ,77191   ,804,804,804
BEGIN DESCRIPTION:
Black Mingo Creek 156.0
END DESCRIPTION:
XS GIS Cut Line= 3
      2424686.33       687321.39      2425455.98       684894.04
      2425890.15       683522.46
#Sta/Elev= 30
  2450.6   35.25  2630.6   37.23  2640.6   35.93  2740.6   33.57  2800.6   34.57
  2850.6   32.56  3000.6   35.54  3710.6    31.3  3880.6   33.39  4020.6    30.8
  4180.6   30.66  4290.6   25.06  4550.6   20.13  4850.6    20.3  4880.6   22.85
  4900.6   20.57    4963   20.04  4965.2   15.54  5034.8   15.54    5037   20.04
    5517   21.44    5667    20.1    5827   21.63    5947   27.07    5977   26.52
    6127   31.87    6267   39.67    6287    41.3    6317   47.26  6435.7   49.85
#Mann= 3 ,-1 , 0
  2450.6     .15       0    4963     .05       0    5037     .15       0
Bank Sta=4963,5037
XS Rating Curve= 0 ,0
Exp/Cntr=0.3,0.1

Type RM Length L Ch R = 1 ,76387   ,812,812,812
BEGIN DESCRIPTION:
Black Mingo Creek 154.0
END DESCRIPTION:
XS GIS Cut Line= 3
      2425086.32       687290.58      2426173.76       685129.19
      2426713.49         684035.
#Sta/Elev= 30
  2589.5    35.2  2869.5   32.96  2959.5    30.2  3039.5    29.5  3059.5   30.49
  3089.5    28.6  3219.5   32.59  3349.5   33.96  3509.5   32.05  3569.5    33.1
  3689.5   30.75  3879.5   31.85  4039.5   29.81  4119.5   25.46  4239.5   23.81
  4299.5   20.29  4629.5   21.92  4719.5   19.94    4963   20.08  4965.2   15.58
  5034.8   15.58    5037   20.08    5799   20.28    5849   23.17    5899   31.51
    5939    35.8    5949   38.09    6079   45.47    6179   53.08  6229.1   53.64
#Mann= 3 ,-1 , 0
  2589.5     .15       0    4963     .05       0    5037     .15       0
Bank Sta=4963,5037
XS Rating Curve= 0 ,0
Exp/Cntr=0.3,0.1

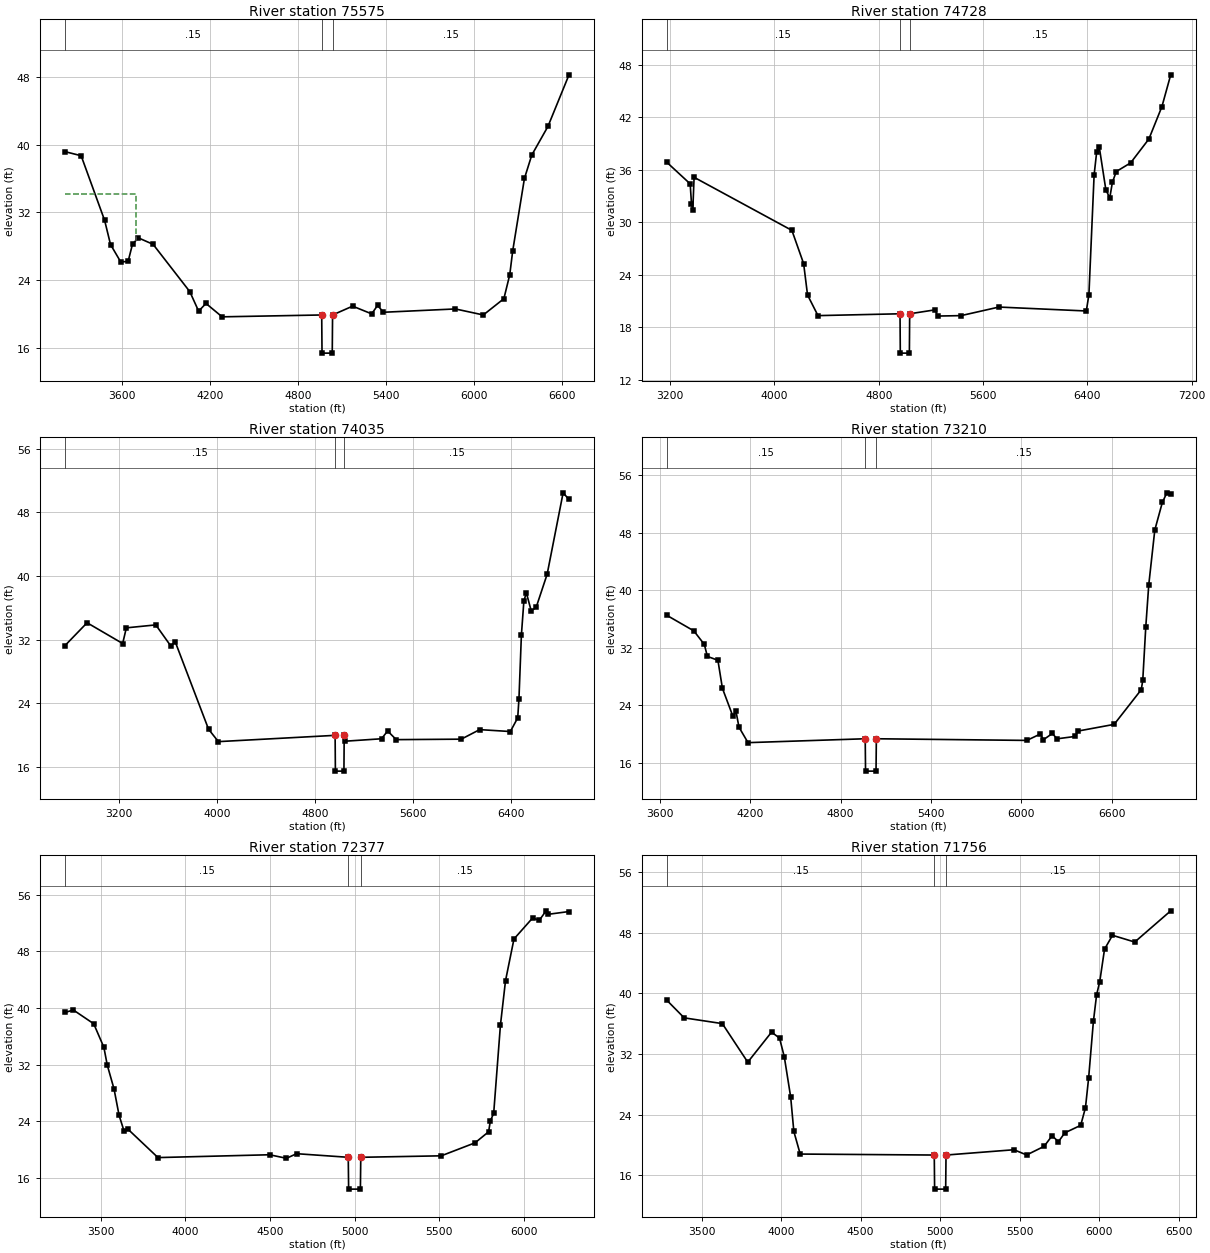
Type RM Length L Ch R = 1 ,75575   ,847,847,847
BEGIN DESCRIPTION:
Black Mingo Creek 152.0
END DESCRIPTION:
XS GIS Cut Line= 3
      2425910.37       687236.47      2426747.87       685656.02
      2427321.97       684116.09
#Sta/Elev= 30
  3214.9   39.16  3324.9   38.68  3484.9   31.05  3524.9   28.21  3594.9   26.14
  3644.9   26.23  3674.9   28.27  3714.9   28.99  3814.9   28.23  4064.9   22.65
  4124.9   20.35  4174.9   21.26  4284.9   19.68    4963    19.9  4965.2    15.4
  5034.8    15.4    5037    19.9  5173.5   20.94  5303.5   20.03  5343.5   21.03
  5383.5   20.22  5873.5   20.61  6063.5    19.9  6203.5   21.82  6243.5   24.64
  6263.5   27.44  6343.5      36  6393.5   38.76  6503.5   42.13    6647   48.22
#Mann= 3 ,-1 , 0
  3214.9     .15       0    4963     .05       0    5037     .15       0
#XS Ineff= 2 , 0
       0  3697.4   34.17               0
Permanent Ineff=
       F       F
Bank Sta=4963,5037
XS Rating Curve= 0 ,0
Exp/Cntr=0.3,0.1

Type RM Length L Ch R = 1 ,74728   ,693,693,693
BEGIN DESCRIPTION:
Black Mingo Creek 150.0
END DESCRIPTION:
XS GIS Cut Line= 3
      2427173.38       687864.64      2427470.57       686041.01
      2427740.73       684041.77
#Sta/Elev= 30
  3173.8   36.88  3353.8    34.4  3363.8   32.13  3373.8    31.4  3383.8   35.15
  4133.8   29.08  4223.8   25.28  4253.8   21.69  4333.8   19.33    4963   19.54
  4965.2   15.04  5034.8   15.04    5037   19.54  5231.5   19.99  5251.5   19.28
  5431.5   19.33  5721.5   20.31  6391.5   19.86  6411.5   21.71  6451.5   35.43
  6471.5    38.1  6491.5   38.56  6541.5   33.72  6571.5   32.79  6591.5   34.57
  6621.5   35.81  6731.5    36.8  6871.5   39.53  6971.5   43.24  7038.9   46.87
#Mann= 3 ,-1 , 0
  3173.8     .15       0    4963     .05       0    5037     .15       0
Bank Sta=4963,5037
XS Rating Curve= 0 ,0
Exp/Cntr=0.3,0.1

Type RM Length L Ch R = 1 ,74035   ,825,825,825
BEGIN DESCRIPTION:
Black Mingo Creek 149.0
END DESCRIPTION:
XS GIS Cut Line= 3
      2427909.59        688256.4      2428159.49       686020.75
      2428206.77       684163.33
#Sta/Elev= 30
  2761.5   31.25  2941.5   34.12  3231.5   31.51  3261.5   33.48  3501.5   33.85
  3621.5   31.25  3661.5   31.66  3931.5   20.73  4011.5   19.17    4963   19.96
  4965.2   15.46  5034.8   15.46    5037   19.96  5041.1   19.22  5341.1   19.53
  5391.1   20.51  5461.1   19.42  5991.1   19.48  6141.1   20.68  6391.1   20.44
  6451.1   22.16  6461.1   24.51  6481.1   32.57  6501.1    36.8  6521.1   37.91
  6561.1   35.62  6601.1   36.04  6691.1   40.23  6821.1   50.46  6869.1   49.63
#Mann= 3 ,-1 , 0
  2761.5     .15       0    4963     .05       0    5037     .15       0
Bank Sta=4963,5037
XS Rating Curve= 0 ,0
Exp/Cntr=0.3,0.1

Type RM Length L Ch R = 1 ,73210   ,833,833,833
BEGIN DESCRIPTION:
Black Mingo Creek 148.0
END DESCRIPTION:
XS GIS Cut Line= 3
      2428906.56        687394.5      2428964.21       686014.17
        2428970.       684048.51
#Sta/Elev= 30
  3644.7   36.53  3824.7   34.36  3894.7   32.47  3914.7   30.81  3984.7   30.27
  4014.7   26.37  4084.7   22.46  4104.7   23.18  4124.7   20.97  4184.7   18.82
    4963   19.36  4965.2   14.86  5034.8   14.86    5037   19.36  6036.2   19.13
  6126.2   20.02  6146.2   19.22  6206.2    20.1  6236.2   19.35  6356.2   19.68
  6376.2   20.43  6616.2   21.36  6796.2   26.18  6806.2   27.47  6826.2   34.89
  6846.2   40.79  6886.2   48.38  6936.2   52.21  6966.2   53.55  6991.9   53.45
#Mann= 3 ,-1 , 0
  3644.7     .15       0    4963     .05       0    5037     .15       0
Bank Sta=4963,5037
XS Rating Curve= 0 ,0
Exp/Cntr=0.3,0.1

Type RM Length L Ch R = 1 ,72377   ,621,621,621
BEGIN DESCRIPTION:
Black Mingo Creek 145.0
END DESCRIPTION:
XS GIS Cut Line= 3
      2429526.96       687475.76      2429746.73       685764.09
      2429868.31       684514.51
#Sta/Elev= 30
  3287.5   39.37  3337.5    39.7  3457.5   37.76  3517.5   34.43  3537.5   31.92
  3577.5   28.55  3607.5   24.81  3637.5   22.54  3657.5   22.91  3837.5   18.84
  4497.5   19.24  4597.5   18.74  4657.5   19.39    4963   18.88  4965.2   14.38
  5034.8   14.38    5037   18.88  5513.2   19.09  5713.2   20.93  5793.2   22.49
  5803.2      24  5823.2    25.1  5863.2   37.59  5893.2   43.85  5943.2   49.75
  6053.2   52.71  6093.2    52.4  6133.2   53.73  6143.2   53.23  6268.7   53.63
#Mann= 3 ,-1 , 0
  3287.5     .15       0    4963     .05       0    5037     .15       0
Bank Sta=4963,5037
XS Rating Curve= 0 ,0
Exp/Cntr=0.3,0.1

Type RM Length L Ch R = 1 ,71756   ,605,605,605
BEGIN DESCRIPTION:
Black Mingo Creek 144.0
END DESCRIPTION:
XS GIS Cut Line= 3
      2429919.15       687699.96      2430314.08       686020.75
      2430658.54       684615.89
#Sta/Elev= 30
  3279.4   39.12  3389.4   36.78  3629.4   36.02  3789.4   30.93  3939.4    34.9
  3989.4    34.1  4019.4   31.63  4059.4   26.34  4079.4   21.78  4119.4    18.8
    4963   18.67  4965.2   14.17  5034.8   14.17    5037   18.67  5464.4   19.37
  5544.4   18.68  5654.4   19.82  5704.4   21.22  5744.4   20.43  5784.4    21.6
  5884.4   22.59  5914.4   24.92  5934.4   28.85  5964.4   36.32  5984.4   39.81
  6004.4   41.58  6034.4   45.84  6084.4   47.68  6224.4   46.79  6450.9   50.91
#Mann= 3 ,-1 , 0
  3279.4     .15       0    4963     .05       0    5037     .15       0
Bank Sta=4963,5037
XS Rating Curve= 0 ,0
Exp/Cntr=0.3,0.1

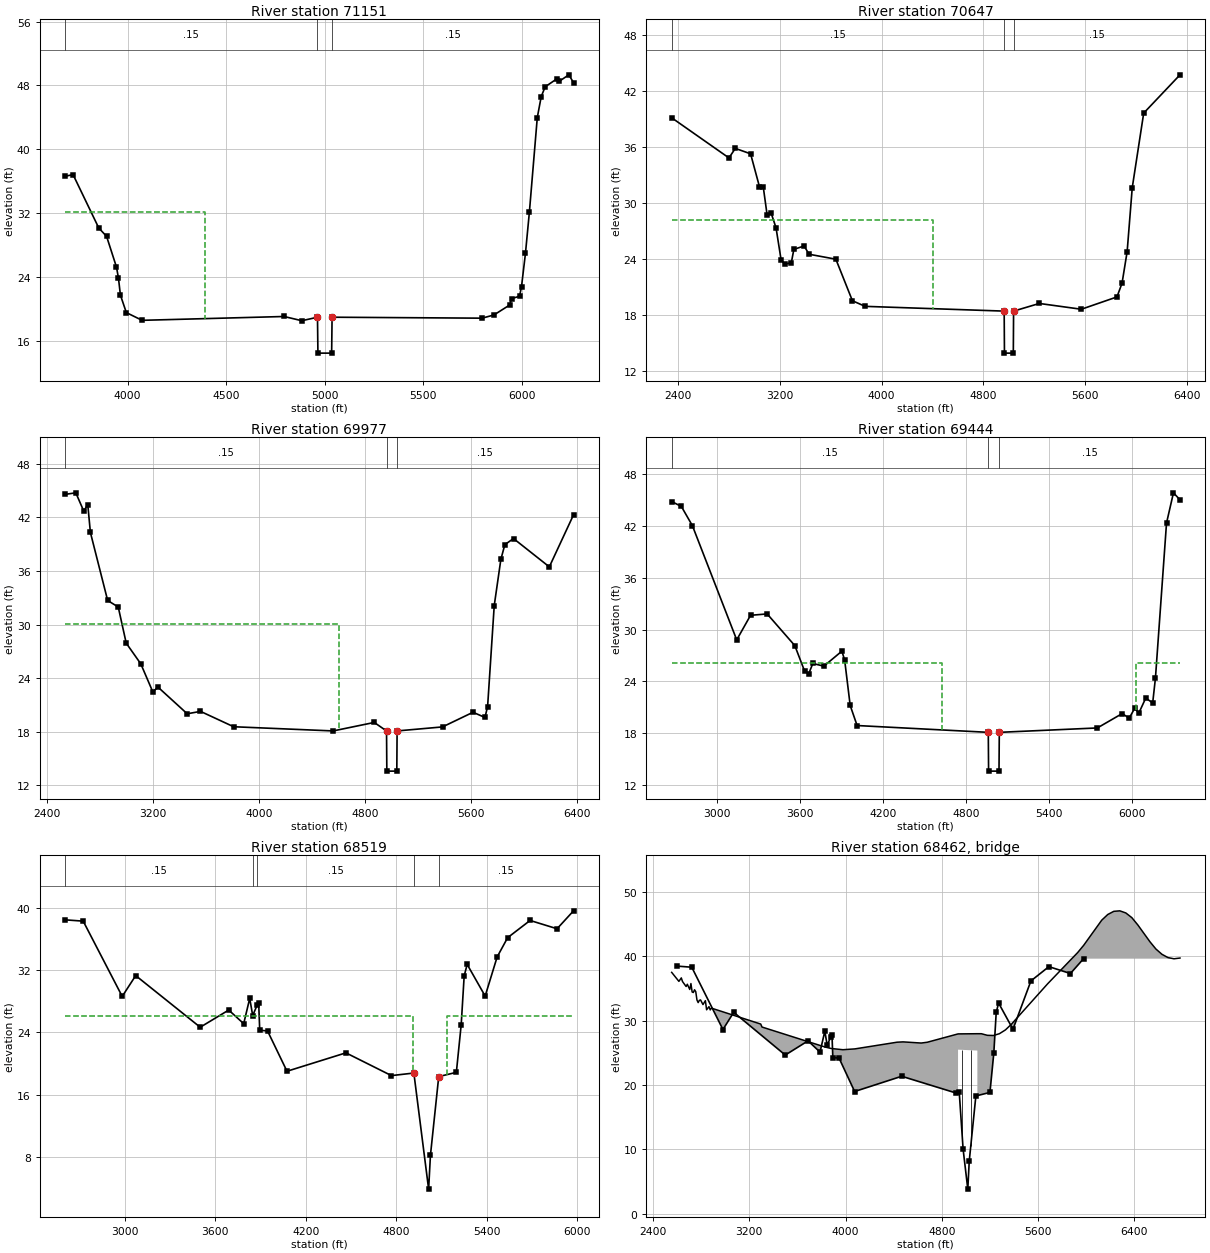
Type RM Length L Ch R = 1 ,71151   ,504,504,504
BEGIN DESCRIPTION:
Black Mingo Creek 143.0
END DESCRIPTION:
XS GIS Cut Line= 3
      2430523.45       687493.18      2430888.18       686209.86
      2431077.31       684980.56
#Sta/Elev= 30
  3683.6   36.62  3723.6   36.81  3853.6   30.14  3893.6   29.07  3943.6   25.23
  3953.6   23.86  3963.6   21.72  3993.6   19.53  4073.6   18.56  4793.6   19.04
  4883.6   18.51    4963   18.95  4965.2   14.45  5034.8   14.45    5037   18.95
  5797.7   18.83  5857.7   19.23  5937.7   20.48  5947.7   21.28  5987.7   21.58
  5997.7   22.79  6017.7   26.96  6037.7   32.15  6077.7   43.97  6097.7    46.6
  6117.7   47.82  6177.7   48.83  6187.7   48.49  6237.7   49.32  6261.5   48.34
#Mann= 3 ,-1 , 0
  3683.6     .15       0    4963     .05       0    5037     .15       0
#XS Ineff= 2 , 0
       0  4390.8   32.08               0
Permanent Ineff=
       F       F
Bank Sta=4963,5037
XS Rating Curve= 0 ,0
Exp/Cntr=0.3,0.1

Type RM Length L Ch R = 1 ,70647   ,670,670,670
BEGIN DESCRIPTION:
Black Mingo Creek 142.0
END DESCRIPTION:
XS GIS Cut Line= 3
      2430977.13       688969.22      2431368.55       686359.97
      2431565.27       685019.07
#Sta/Elev= 30
  2350.7   39.17  2800.7   34.87  2850.7   35.89  2970.7   35.31  3040.7   31.77
  3070.7   31.72  3100.7   28.74  3130.7   29.02  3170.7   27.38  3210.7   23.92
  3240.7   23.49  3290.7   23.65  3310.7   25.07  3390.7   25.44  3430.7   24.55
  3640.7   24.02  3770.7   19.57  3870.7   18.97    4963   18.46  4965.2   13.96
  5034.8   13.96    5037   18.46  5239.2   19.28  5569.2   18.66  5849.2   19.98
  5889.2   21.46  5929.2   24.84  5969.2   31.68  6059.2   39.67  6344.4   43.77
#Mann= 3 ,-1 , 0
  2350.7     .15       0    4963     .05       0    5037     .15       0
#XS Ineff= 2 , 0
       0    4400   28.27               0
Permanent Ineff=
       F       F
Bank Sta=4963,5037
XS Rating Curve= 0 ,0
Exp/Cntr=0.3,0.1

Type RM Length L Ch R = 1 ,69977   ,533,533,533
BEGIN DESCRIPTION:
Black Mingo Creek 141.0
END DESCRIPTION:
XS GIS Cut Line= 4
      2431897.27       688830.36      2432039.29       686379.66
      2432093.66       685505.97      2432257.27       685030.84
#Sta/Elev= 30
  2537.4   44.59  2617.4   44.76  2677.4   42.71  2707.4   43.45  2727.4   40.32
  2857.4   32.71  2937.4   31.97  2997.4   27.93  3107.4   25.61  3197.4   22.49
  3237.4      23  3457.4   20.02  3557.4   20.29  3807.4   18.57  4557.4    18.1
  4867.4   19.05  4960.2    18.1  4962.4    13.6  5037.6    13.6  5039.8    18.1
  5382.2   18.55  5612.2   20.19  5702.2   19.61  5722.2   20.83  5772.2   32.14
  5822.2   37.31  5852.2   38.96  5917.6   39.64  6187.6   36.47  6370.1    42.3
#Mann= 3 ,-1 , 0
  2537.4     .15       0  4960.2     .05       0  5039.8     .15       0
#XS Ineff= 2 , 0
       0    4600   30.06               0
Permanent Ineff=
       F       F
Bank Sta=4960.2,5039.8
XS Rating Curve= 0 ,0
Exp/Cntr=0.3,0.1

Type RM Length L Ch R = 1 ,69444   ,925,925,925
BEGIN DESCRIPTION:
Black Mingo Creek 140.0
END DESCRIPTION:
XS GIS Cut Line= 3
      2432526.37       688887.18      2432531.63       686551.21
      2432526.53       685213.79
#Sta/Elev= 30
  2672.2   44.85  2742.2   44.28  2822.2   42.04  3142.2    28.8  3242.2   31.65
  3362.2   31.81  3562.2   28.13  3632.2    25.2  3662.2   24.85  3692.2   26.06
  3772.2   25.75  3902.2   27.49  3922.2   26.46  3962.2   21.19  4012.2   18.86
  4960.2   18.07  4962.4   13.57  5037.6   13.57  5039.8   18.07  5748.2   18.58
  5928.2   20.25  5978.2   19.71  6018.2   20.86  6048.2   20.31  6098.2   22.05
  6148.2   21.48  6168.2   24.38  6248.2   42.35  6298.2   45.86  6345.6   45.05
#Mann= 3 ,-1 , 0
  2672.2     .15       0  4960.2     .05       0  5039.8     .15       0
#XS Ineff= 2 , 0
       0    4625    26.1    6027       0    26.1
Permanent Ineff=
       T       T
Bank Sta=4960.2,5039.8
XS Rating Curve= 0 ,0
Exp/Cntr=0.5,0.3

Type RM Length L Ch R = 1 ,68519   ,126,126,126
BEGIN DESCRIPTION:
Battery Park Rd - US
END DESCRIPTION:
XS GIS Cut Line= 5
      2433143.53        688353.8      2432850.46       687123.91
      2433112.57       686271.48       2433042.9       685814.76
      2432779.69       685106.43
#Sta/Elev= 30
  2603.5    38.5 2722.96   38.33  2981.8   28.64  3071.4   31.32 3499.48   24.67
 3688.64   26.88 3788.19   25.13 3828.01   28.38 3847.92   26.18 3877.74   27.53
 3887.65   27.75  3894.5   24.28  3946.5   24.19  4075.5      19  4466.5   21.37
  4768.5   18.44  4917.5   18.77  5015.5    3.82  5027.5    8.17  5082.5   18.31
  5199.5   18.86 5231.59   24.98 5251.47   31.29 5271.35   32.76 5390.66   28.68
 5470.19   33.72 5539.78    36.2 5688.91   38.42 5867.86   37.35 5977.22   39.66
#Mann= 5 ,-1 , 0
  2603.5     .15       0 3847.92     .05       0 3877.74     .15       0
  4917.5     .05       0  5082.5     .15       0
#XS Ineff= 2 , 0
       0    4910    26.1    5138       0    26.1
Permanent Ineff=
       T       T
Bank Sta=4917.5,5082.5
XS Rating Curve= 0 ,0
Exp/Cntr=0.5,0.3

Type RM Length L Ch R = 3 ,68462   ,,,
BEGIN DESCRIPTION:
Battery Park Rd - TOR
Structure ID: LDS_BMC_04
Approximate Survey Structure
END DESCRIPTION:
Bridge Culvert--1,0,-1,-1, 0
Deck Dist Width WeirC Skew NumUp NumDn MinLoCord MaxHiCord MaxSubmerge Is_Ogee
43.85,36,3,0, 58, 57, , , 0.95, 0, 2,2,,
    2556    2616    2636    2646    2676    2686    2706    2716    2726    2736
    2746    2756    2766    2776    2786    2796    2816    2836    2846    2866
    2876    2886    3296    3306    3828    3878    3978    4078    4428    4478
    4628    4678  4934.5  4934.5    5095    5095    5128    5178    5228    5278
    5328    5378    5678    5928    5978    6128    6178    6228    6278    6328
    6378    6428    6528    6578    6628    6678    6728    6778
   37.53   36.13   36.67    36.1   35.33   35.68   34.87   35.79   34.47    34.4
   34.82   34.53   33.23   32.83   33.18   33.24   32.52   33.13   31.71    32.2
   31.69   31.97   29.49   29.03   25.93    25.7    25.5   25.63   26.67   26.72
   26.54   26.66   27.96   27.96   27.99   27.99   27.99   27.74   27.71   27.99
   28.58   29.47   35.74   40.61   41.74   45.65   46.53   47.02    47.1   46.77
   46.04    44.9    42.3   41.16   40.34   39.83   39.64   39.76
   -6.28   -6.28   -6.28   -6.28   -6.28   -6.28   -6.28   -6.28   -6.28   -6.28
   -6.28   -6.28   -6.28   -6.28   -6.28   -6.28   -6.28   -6.28   -6.28   -6.28
   -6.28   -6.28   -6.28   -6.28   -6.28   -6.28   -6.28   -6.28   -6.28   -6.28
   -6.28   -6.28   -6.28   25.51   25.37   -6.28   -6.28   -6.28   -6.28   -6.28
   -6.28   -6.28   -6.28   -6.28   -6.28   -6.28   -6.28   -6.28   -6.28   -6.28
   -6.28   -6.28   -6.28   -6.28   -6.28   -6.28   -6.28   -6.28
    2556    2616    2636    2646    2676    2686    2706    2716    2726    2736
    2746    2756    2766    2776    2786    2796    2816    2836    2846    2866
    2876    2886    3296    3306 3722.44 3822.44 3922.44 4022.44 4372.44 4422.44
 4572.44 4622.44 4872.44 4926.25 4926.25 5086.75 5086.75 5172.44 5222.44 5272.44
 5322.44 5622.44 5872.44 5922.44 6072.44 6122.44 6172.44 6222.44 6272.44 6322.44
 6372.44 6472.44 6522.44 6572.44 6622.44 6672.44 6722.44
   37.53   36.13   36.67    36.1   35.33   35.68   34.87   35.79   34.47    34.4
   34.82   34.53   33.23   32.83   33.18   33.24   32.52   33.13   31.71    32.2
   31.69   31.97   29.49   29.03   26.23    25.7    25.5   25.63   26.67   26.72
   26.54   26.66   27.96   28.16   28.16   27.74   27.74   27.71   27.99   28.58
   29.47   35.74   40.61   41.74   45.65   46.53   47.02    47.1   46.77   46.04
    44.9    42.3   41.16   40.34   39.83   39.64   39.76
   -6.28   -6.28   -6.28   -6.28   -6.28   -6.28   -6.28   -6.28   -6.28   -6.28
   -6.28   -6.28   -6.28   -6.28   -6.28   -6.28   -6.28   -6.28   -6.28   -6.28
   -6.28   -6.28   -6.28   -6.28   -6.28   -6.28   -6.28   -6.28   -6.28   -6.28
   -6.28   -6.28   -6.28   -6.28   25.51   25.37   -6.28   -6.28   -6.28   -6.28
   -6.28   -6.28   -6.28   -6.28   -6.28   -6.28   -6.28   -6.28   -6.28   -6.28
   -6.28   -6.28   -6.28   -6.28   -6.28   -6.28   -6.28
Pier Skew, UpSta & Num, DnSta & Num=  ,4970.25, 2 ,4962, 2 , 0 , 0 , 0 ,,
     1.5     1.5
       1   25.51
     1.5     1.5
       1   25.51
Pier Skew, UpSta & Num, DnSta & Num=  ,5040.25, 2 ,5032, 2 , 0 , 0 , 0 ,,
     1.5     1.5
       1   25.51
     1.5     1.5
       1   25.51
Abutment Skew #Up #Dn= , 3 , 3
  4934.5  4936.5  4976.5
   22.87   22.87    2.87
 4926.25 4928.25 4968.25
   22.87   22.87    3.87
Abutment Skew #Up #Dn= , 3 , 3
    5053    5093    5095
    1.37   21.37   21.37
 5044.75 5084.75 5086.75
    1.37   21.37   21.37
BR Coef= 1 , 1 , 0 ,1.25, 0 ,,,0.8,-1,2,0,
WSPro=,,,, 1 ,,,, 0 ,,,, 0 ,,,,-1 ,-1 ,-1 , 0 , 0 , 0 , 0 , 0
BR U #Sta/Elev= 30
  2603.5    38.5 2722.96   38.33  2981.8   28.64  3071.4   31.32 3499.48   24.67
 3688.64   26.88 3788.19   25.13 3828.01   28.38 3847.92   26.18 3877.74   27.53
 3887.65   27.75  3894.5   24.28  3946.5   24.19  4075.5      19  4466.5   21.37
  4917.5   18.77  4944.5   18.87  4976.5   10.05  5015.5    3.82  5027.5    8.17
  5082.5   18.31  5199.5   18.86 5231.59   24.98 5251.47   31.29 5271.35   32.76
 5390.66   28.68 5539.78    36.2 5688.91   38.42 5867.86   37.35 5977.22   39.66
BR U #Mann= 5
  2603.5     .15 3847.92     .05 3877.74     .15  4917.5     .05  5082.5     .15
BR U Banks=4944.5,
BR D #Sta/Elev= 30
    2557   37.83 2646.97   37.95 2906.88   33.63 3266.75   30.37 3546.65   23.86
  3666.6   24.49 3706.59    20.2 3716.59   20.05 3786.56   20.36 3836.49   24.11
    3931   17.95    4163   20.34    4640   19.93    4755   17.83  4929.5   18.51
    4952   18.46    4960    7.74    4998    7.03    5042    8.12    5048   18.98
  5064.5   19.67  5174.1   20.55 5203.63   28.25 5243.21   33.87  5263.1    34.7
 5432.21   31.47 5551.58   31.89 5720.69   35.45 5830.12   40.16 5949.49      42
BR D #Mann= 3
    2557     .15  4929.5     .05  5064.5     .15
BC Design=,, 0 ,, 0 ,,8,4952.75,4944.5,15,1
BC HTab HWMax=39.9
BC Use User HTab Curves=0
BC User HTab FreeFlow(D)= 0