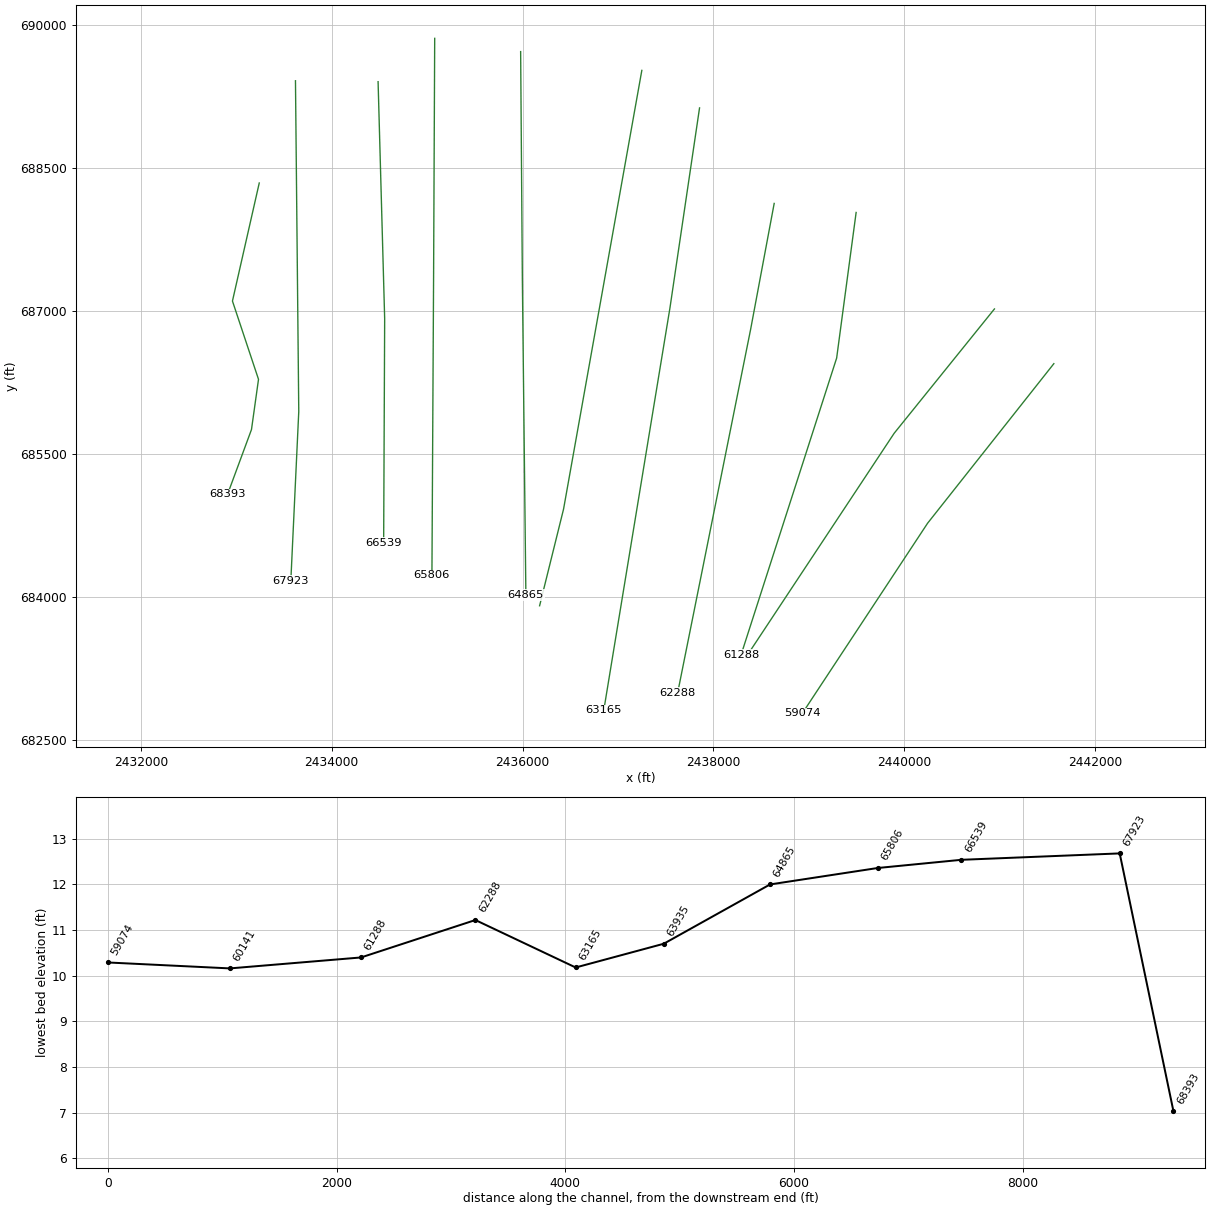
HEC-RAS study Black Mingo Creek.prj: Black Mingo Creek Limited Detail Study

--- Black Mingo Creek.g04 (geometry) --- (continued)

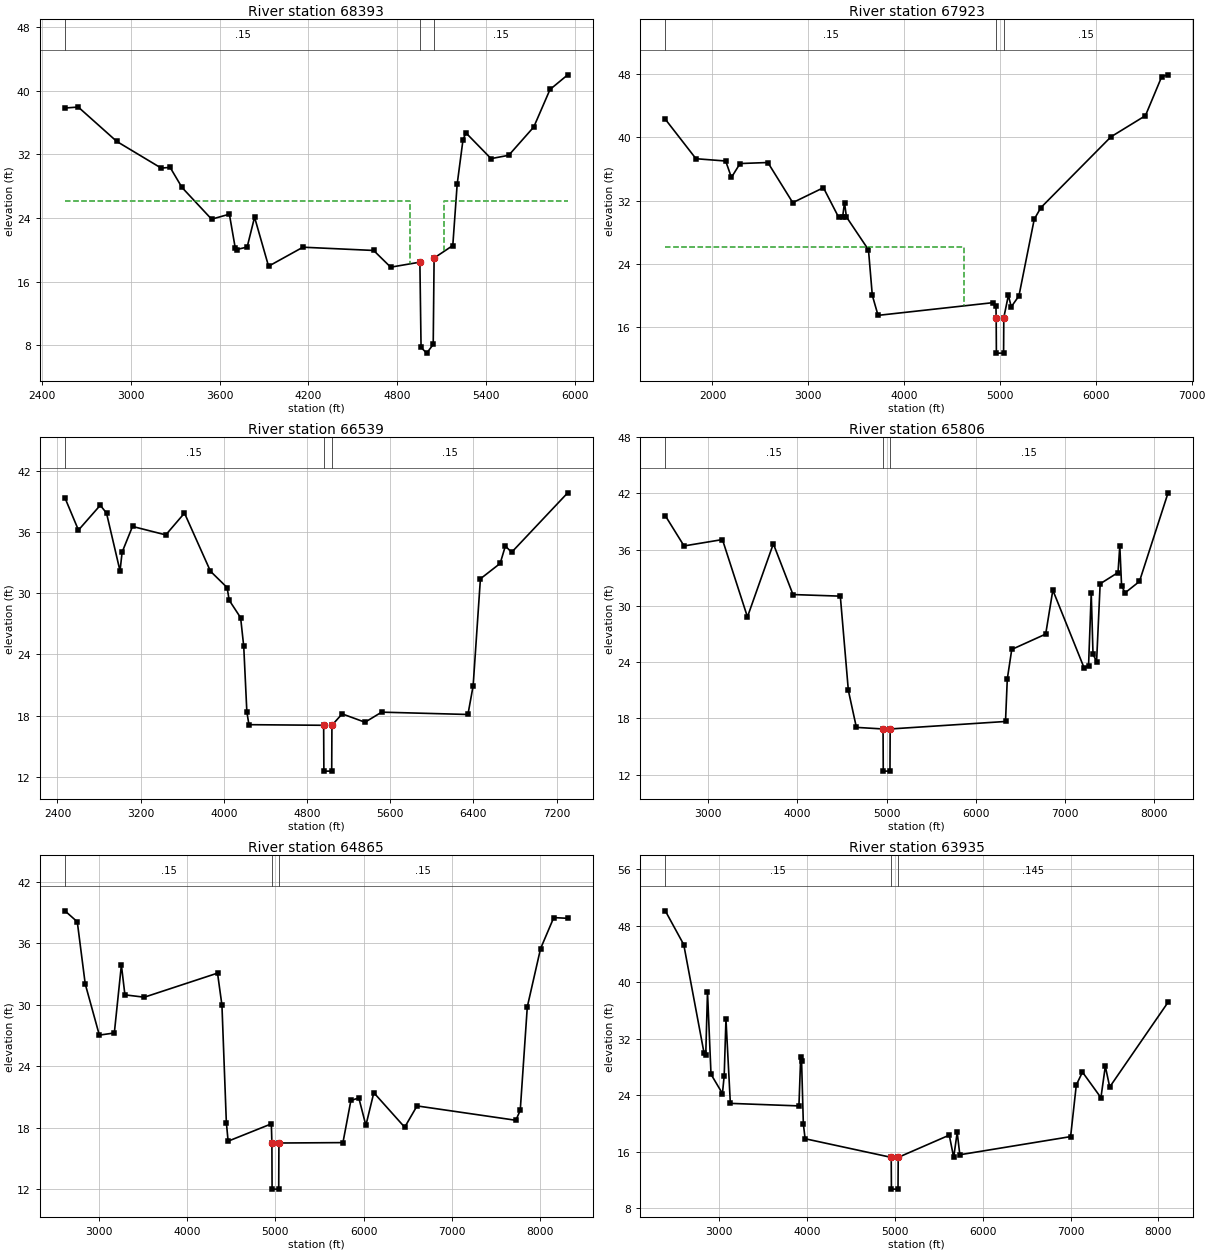
Type RM Length L Ch R = 1 ,68393   ,470,470,470
BEGIN DESCRIPTION:
Battery Park Rd - DS
END DESCRIPTION:
XS GIS Cut Line= 5
       2433240.3       688342.21      2432959.45       687104.09
      2433232.55       686283.09      2433159.01        685756.7
      2432907.43       685075.48
#Sta/Elev= 30
    2557   37.83 2646.97   37.95 2906.88   33.63 3206.77   30.28 3266.75   30.37
 3346.72   27.85 3546.65   23.86  3666.6   24.49 3706.59    20.2 3716.59   20.05
 3786.56   20.36 3836.49   24.11    3931   17.95    4163   20.34    4640   19.93
    4755   17.83    4952   18.46    4960    7.74    4998    7.03    5042    8.12
    5048   18.98  5174.1   20.55 5203.63   28.25 5243.21   33.87  5263.1    34.7
 5432.21   31.47 5551.58   31.89 5720.69   35.45 5830.12   40.16 5949.49      42
#Mann= 3 ,-1 , 0
    2557     .15       0    4952     .05       0    5048     .15       0
#XS Ineff= 2 , 0
       0    4882    26.1    5117       0    26.1
Permanent Ineff=
       T       T
Bank Sta=4952,5048
XS Rating Curve= 0 ,0
Exp/Cntr=0.5,0.3

Type RM Length L Ch R = 1 ,67923   ,1384,1384,1384
BEGIN DESCRIPTION:
Black Mingo Creek 136.0
END DESCRIPTION:
XS GIS Cut Line= 3
        2433620.       689414.69       2433654.5       685944.91
      2433571.35       684170.71
#Sta/Elev= 30
  1507.7   42.29  1827.7   37.29  2137.7      37  2197.7   34.92  2287.7   36.68
  2577.7   36.81  2837.7   31.73  3157.7   33.62  3317.7   29.85  3357.7   29.89
  3377.7   31.73  3397.7   29.92  3627.7   25.76  3667.7      20  3727.7   17.46
  4927.7   19.07  4957.7   18.69  4960.2   17.18  4962.4   12.68  5037.6   12.68
  5039.8   17.18  5087.6      20  5117.6   18.54  5197.6   19.92  5357.6   29.64
  5427.6   31.11  6157.6   40.06  6517.6   42.74  6687.6   47.68  6753.8   47.91
#Mann= 3 ,-1 , 0
  1507.7     .15       0  4960.2     .05       0  5039.8     .15       0
#XS Ineff= 2 , 0
       0    4626    26.1               0
Permanent Ineff=
       T       F
Bank Sta=4960.2,5039.8
XS Rating Curve= 0 ,0
Exp/Cntr=0.3,0.1

Type RM Length L Ch R = 1 ,66539   ,733,733,733
BEGIN DESCRIPTION:
Black Mingo Creek 135.0
END DESCRIPTION:
XS GIS Cut Line= 3
      2434485.89       689404.96      2434554.89       686919.31
      2434544.26       684569.65
#Sta/Elev= 30
  2471.5   39.37  2601.5    36.2  2811.5   38.64  2871.5   37.87  3001.5   32.19
  3021.5   34.03  3121.5   36.56  3441.5   35.73  3621.5   37.87  3871.5   32.16
  4031.5   30.56  4051.5   29.32  4161.5    27.6  4191.5   24.78  4221.5   18.35
  4241.5    17.1  4960.2   17.04  4962.4   12.54  5037.6   12.54  5039.8   17.04
  5138.1   18.16  5358.1   17.34  5518.1   18.33  6348.1    18.1  6398.1   20.91
  6468.1   31.42  6658.1   32.93  6708.1   34.64  6768.1   34.02  7307.8   39.86
#Mann= 3 ,-1 , 0
  2471.5     .15       0  4960.2     .05       0  5039.8     .15       0
Bank Sta=4960.2,5039.8
XS Rating Curve= 0 ,0
Exp/Cntr=0.3,0.1

Type RM Length L Ch R = 1 ,65806   ,941,941,941
BEGIN DESCRIPTION:
Black Mingo Creek 133.0
END DESCRIPTION:
XS GIS Cut Line= 3
      2435079.21       689859.59      2435067.68       687369.67
      2435050.17       684229.17
#Sta/Elev= 30
  2521.5   39.63  2731.5    36.4  3161.5   37.08  3441.5   28.82  3731.5   36.63
  3951.5   31.21  4481.5   31.04  4571.5   20.98  4661.5   17.03  4960.2   16.86
  4962.4   12.36  5037.6   12.36  5039.8   16.86  6331.5   17.66  6351.5    22.2
  6401.5   25.35  6781.5   26.99  6861.5   31.68  7211.5   23.39  7261.5    23.6
  7291.5   31.38  7311.5   24.85  7351.5   24.05  7391.5   32.36  7591.5   33.56
  7611.5   36.42  7631.5   32.11  7671.5    31.4  7831.5   32.61    8152   42.07
#Mann= 3 ,-1 , 0
  2521.5     .15       0  4960.2     .05       0  5039.8     .15       0
Bank Sta=4960.2,5039.8
XS Rating Curve= 0 ,0
Exp/Cntr=0.3,0.1

Type RM Length L Ch R = 1 ,64865   ,930,930,930
BEGIN DESCRIPTION:
Black Mingo Creek 131.0
END DESCRIPTION:
XS GIS Cut Line= 3
      2435980.09       689720.38      2435997.99       687338.67
      2436034.99       684020.75
#Sta/Elev= 30
  2613.9   39.16  2753.9   38.09  2843.9   32.03  3003.9   27.03  3173.9   27.24
  3253.9   33.87  3293.9   30.96  3513.9   30.73  4343.9   33.08  4393.9   29.95
  4443.9    18.5  4463.9   16.68  4953.9   18.37  4960.2    16.5  4962.4      12
  5037.6      12  5039.8    16.5  5765.7   16.54  5855.7   20.65  5945.7    20.9
  6025.7   18.22  6115.7   21.41  6465.7   18.04  6605.7   20.12  7725.7   18.72
  7775.7   19.69  7855.7   29.79  8005.7   35.46  8155.7    38.5  8313.8   38.43
#Mann= 3 ,-1 , 0
  2613.9     .15       0  4960.2     .05       0  5039.8     .15       0
Bank Sta=4960.2,5039.8
XS Rating Curve= 0 ,0
Exp/Cntr=0.3,0.1

Type RM Length L Ch R = 1 ,63935   ,770,770,770
BEGIN DESCRIPTION:
Black Mingo Creek 129.0
END DESCRIPTION:
XS GIS Cut Line= 3
      2437250.23       689523.41      2436429.69       684921.17
      2436178.75        683908.1
#Sta/Elev= 30
  2390.6   50.13  2600.6   45.34  2830.6   30.04  2850.6   29.65  2870.6   38.64
  2910.6   26.97  3040.6   24.24  3060.6   26.78  3080.6   34.79  3130.6   22.85
  3910.6   22.49  3930.6    29.4  3940.6    28.9  3960.6   19.99  3980.6   17.84
  4960.2    15.2  4962.4    10.7  5037.6    10.7  5039.8    15.2  5620.6   18.35
  5670.6    15.2  5710.6   18.73  5740.6   15.57  7000.6   18.14  7065.4   25.46
  7135.4   27.28  7345.4   23.66  7395.4    28.1  7445.4   25.17  8109.1   37.18
#Mann= 3 ,-1 , 0
  2390.6     .15       0  4960.2     .05       0  5039.8    .145       0
Bank Sta=4960.2,5039.8
XS Rating Curve= 0 ,0
Exp/Cntr=0.3,0.1

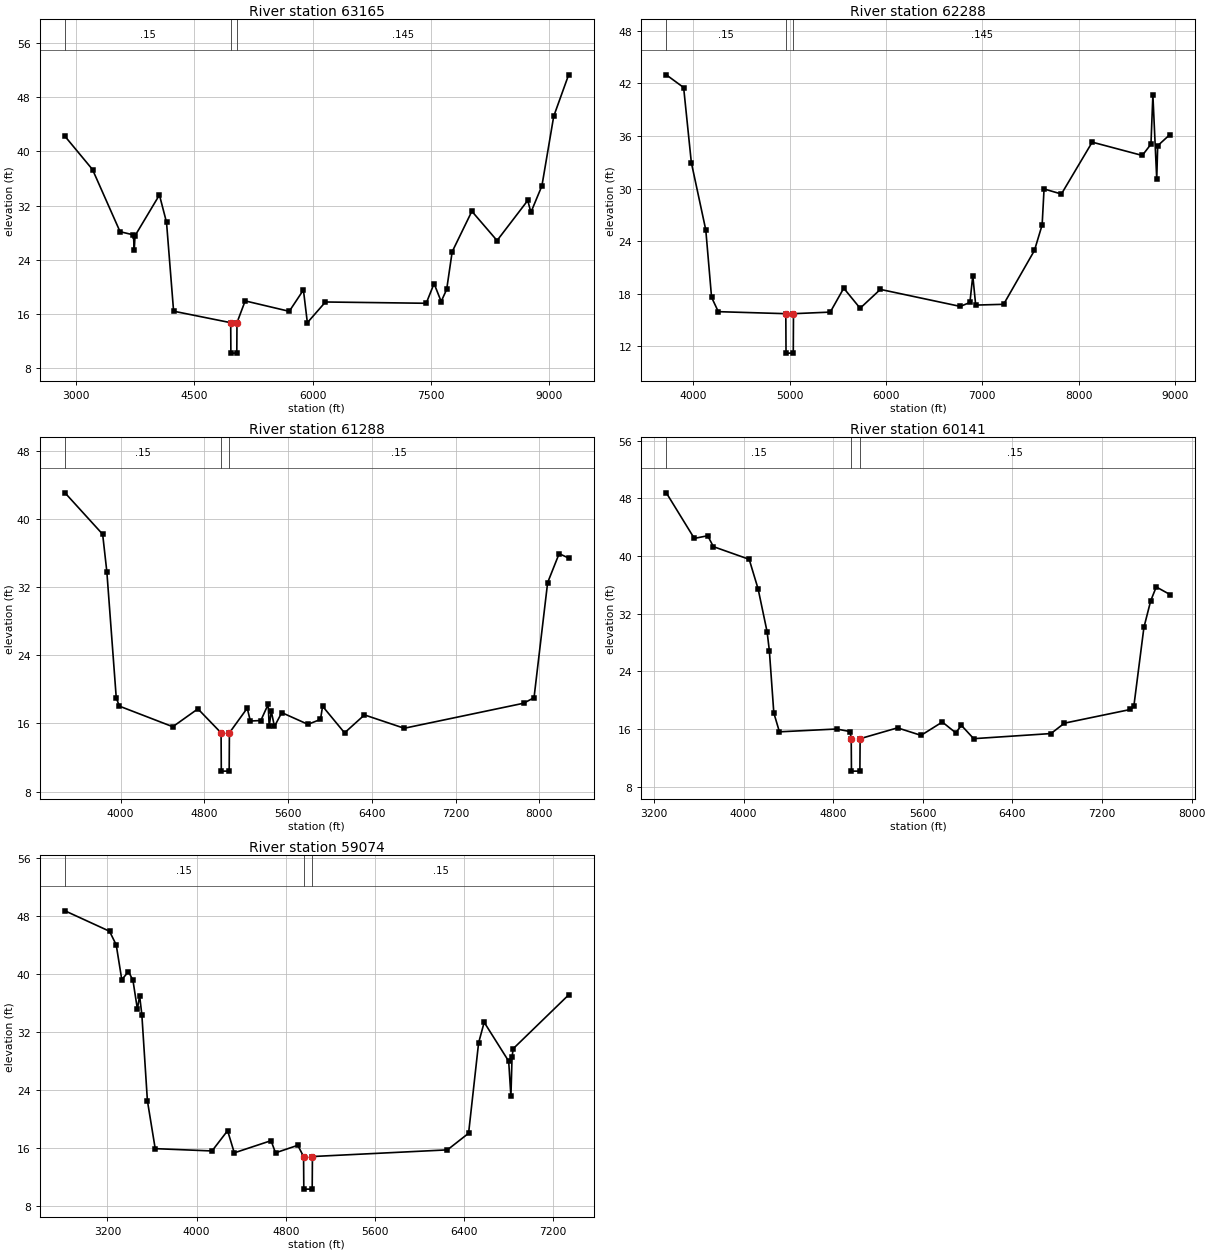
Type RM Length L Ch R = 1 ,63165   ,877,877,877
BEGIN DESCRIPTION:
Black Mingo Creek 127.0
END DESCRIPTION:
XS GIS Cut Line= 3
      2437855.21       689129.84      2437545.15       687033.22
       2436851.2       682810.48
#Sta/Elev= 30
  2854.6   42.23  3204.6   37.32  3554.6   28.13  3724.6   27.66  3734.6   25.44
  3744.6   27.53  4054.6   33.56  4144.6   29.52  4234.6   16.38  4960.2   14.68
  4962.4   10.18  5037.6   10.18  5039.8   14.68    5144    17.9    5704   16.36
    5884   19.52    5934   14.68    6164   17.74    7444   17.55    7544   20.46
    7634   17.81    7704    19.6    7774   25.17    8024   31.15    8344   26.82
    8734   32.75    8774   30.99    8914   34.91    9064   45.19  9253.4   51.32
#Mann= 3 ,-1 , 0
  2854.6     .15       0  4960.2     .05       0  5039.8    .145       0
Bank Sta=4960.2,5039.8
XS Rating Curve= 0 ,0
Exp/Cntr=0.3,0.1

Type RM Length L Ch R = 1 ,62288   ,1000,1000,1000
BEGIN DESCRIPTION:
Black Mingo Creek 125.0
END DESCRIPTION:
XS GIS Cut Line= 3
       2438637.5       688128.07      2438390.82        686808.3
      2437626.09       682996.99
#Sta/Elev= 30
  3719.2   42.97  3899.2   41.52  3979.2   32.96  4129.2   25.27  4189.2   17.59
  4259.2   15.95  4960.2   15.72  4962.4   11.22  5037.6   11.22  5039.8   15.72
  5421.8    15.9  5561.8   18.63  5731.8   16.34  5941.8   18.49  6771.8   16.55
  6871.8      17  6901.8   20.05  6931.8    16.7  7221.8   16.79  7541.8   22.93
  7621.8   25.85  7641.8   29.95  7821.8   29.37  8141.8   35.29  8661.8   33.77
  8751.8   35.06  8771.8   40.67  8811.8   31.08  8821.8   34.88  8949.1   36.16
#Mann= 3 ,-1 , 0
  3719.2     .15       0  4960.2     .05       0  5039.8    .145       0
Bank Sta=4960.2,5039.8
XS Rating Curve= 0 ,0
Exp/Cntr=0.3,0.1

Type RM Length L Ch R = 1 ,61288   ,1147,1147,1147
BEGIN DESCRIPTION:
Black Mingo Creek 123.0
END DESCRIPTION:
XS GIS Cut Line= 3
      2439496.37       688033.22      2439292.06       686505.74
      2438289.96       683392.42
#Sta/Elev= 30
  3468.9   43.12  3828.9   38.25  3868.9   33.84  3958.9      19  3988.9   18.04
  4498.9   15.62  4738.9   17.72  4960.2    14.9  4962.4    10.4  5037.6    10.4
  5039.8    14.9    5210    17.8    5240   16.29    5340   16.35    5410   18.25
    5420   15.68    5440   17.44    5470   15.65    5540   17.28    5790    15.9
    5910   16.48    5930   18.03    6140    14.9    6330   17.01    6710   15.44
    7850   18.38    7950   19.03    8080   32.56    8190   35.97  8280.6   35.45
#Mann= 3 ,-1 , 0
  3468.9     .15       0  4960.2     .05       0  5039.8     .15       0
Bank Sta=4960.2,5039.8
XS Rating Curve= 0 ,0
Exp/Cntr=0.3,0.1

Type RM Length L Ch R = 1 ,60141   ,1067,1067,1067
BEGIN DESCRIPTION:
Black Mingo Creek 121.0
END DESCRIPTION:
XS GIS Cut Line= 3
      2440946.02        687021.4      2439895.26       685717.68
      2438338.58       683363.21
#Sta/Elev= 30
  3309.2   48.75  3559.2   42.43  3679.2    42.8  3729.2   41.29  4049.2   39.53
  4129.2   35.41  4209.2   29.48  4229.2   26.88  4269.2   18.23  4319.2   15.61
  4829.2      16  4949.2   15.65  4960.2   14.66  4962.4   10.16  5037.6   10.16
  5039.8   14.66  5373.7   16.16  5583.7   15.12  5773.7   16.97  5893.7   15.47
  5943.7   16.51  6053.7   14.66  6743.7   15.37  6863.7   16.81  7453.7   18.71
  7483.7   19.15  7573.7   30.09  7633.7   33.75  7683.7    35.7  7806.2   34.65
#Mann= 3 ,-1 , 0
  3309.2     .15       0  4960.2     .05       0  5039.8     .15       0
Bank Sta=4960.2,5039.8
XS Rating Curve= 0 ,0
Exp/Cntr=0.3,0.1

Type RM Length L Ch R = 1 ,59074   ,672,672,672
BEGIN DESCRIPTION:
Black Mingo Creek 119.0
END DESCRIPTION:
XS GIS Cut Line= 3
      2441568.67       686447.36      2440245.51       684773.96
      2438932.08        682779.5
#Sta/Elev= 30
  2818.3   48.71  3218.3   45.89  3278.3   44.01  3328.3   39.21  3388.3   40.31
  3428.3   39.14  3468.3   35.14  3488.3   36.99  3508.3   34.39  3558.3   22.49
  3628.3   15.88  4138.3   15.56  4278.3   18.36  4338.3    15.3  4668.3   16.98
  4708.3    15.3  4908.3   16.34  4960.2   14.79  4962.4   10.29  5037.6   10.29
  5039.8   14.79  6251.6   15.71  6441.6      18  6531.6   30.49  6581.6   33.32
  6801.6   27.95  6821.6   23.08  6831.6   28.47  6841.6   29.67  7339.7    37.1
#Mann= 3 ,-1 , 0
  2818.3     .15       0  4960.2     .05       0  5039.8     .15       0
Bank Sta=4960.2,5039.8
XS Rating Curve= 0 ,0
Exp/Cntr=0.3,0.1