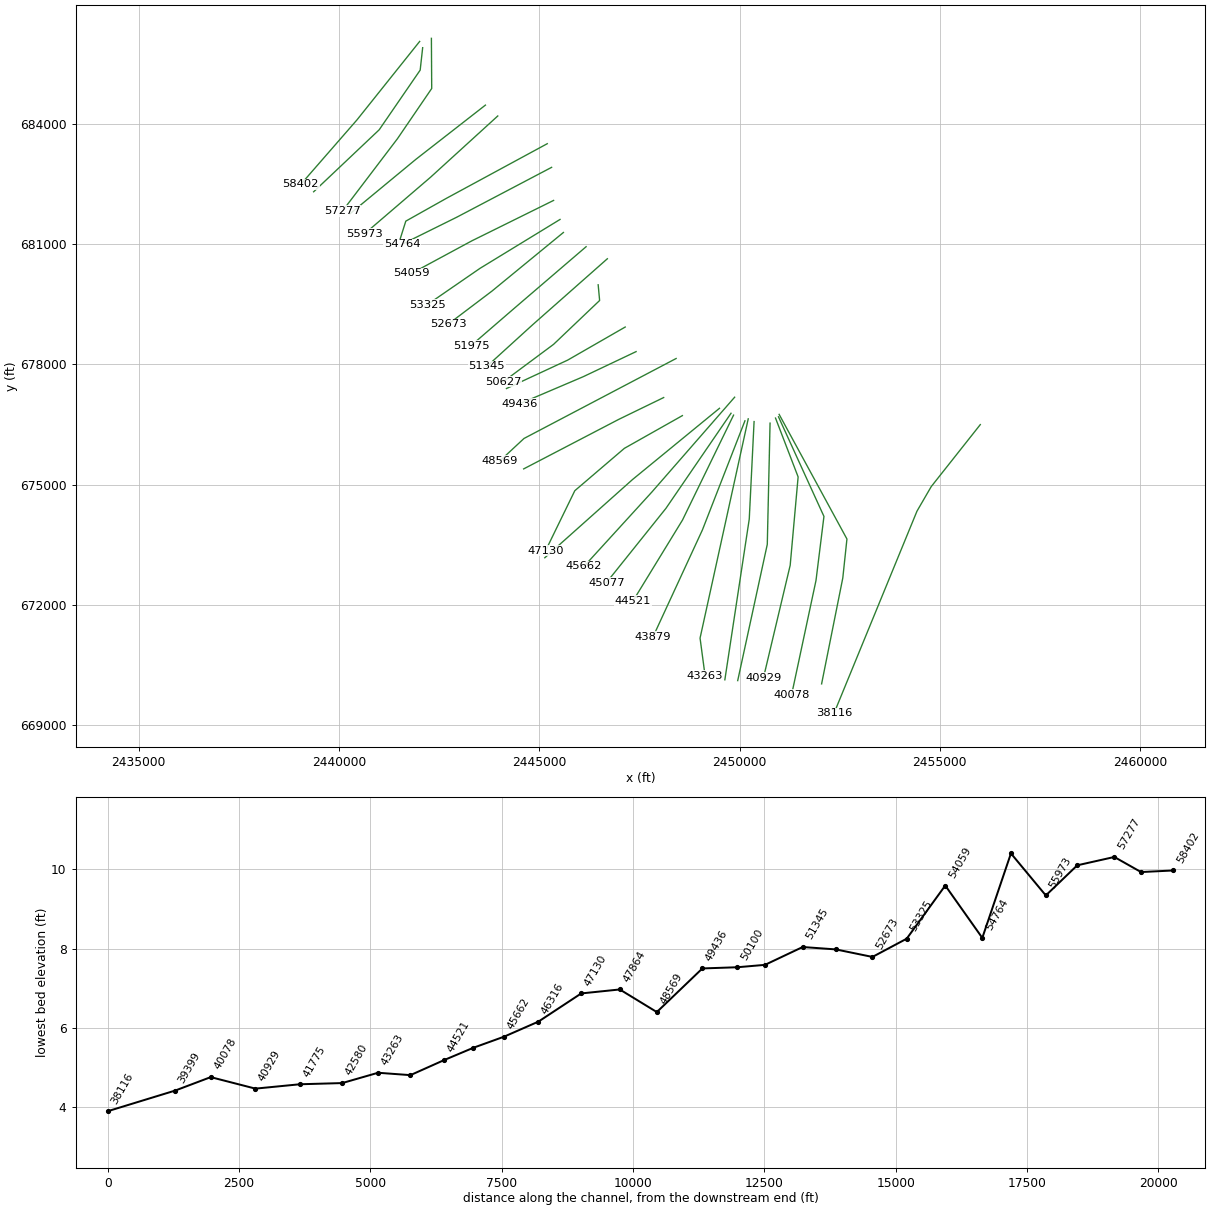
HEC-RAS study Black Mingo Creek.prj: Black Mingo Creek Limited Detail Study

--- Black Mingo Creek.g04 (geometry) --- (continued)

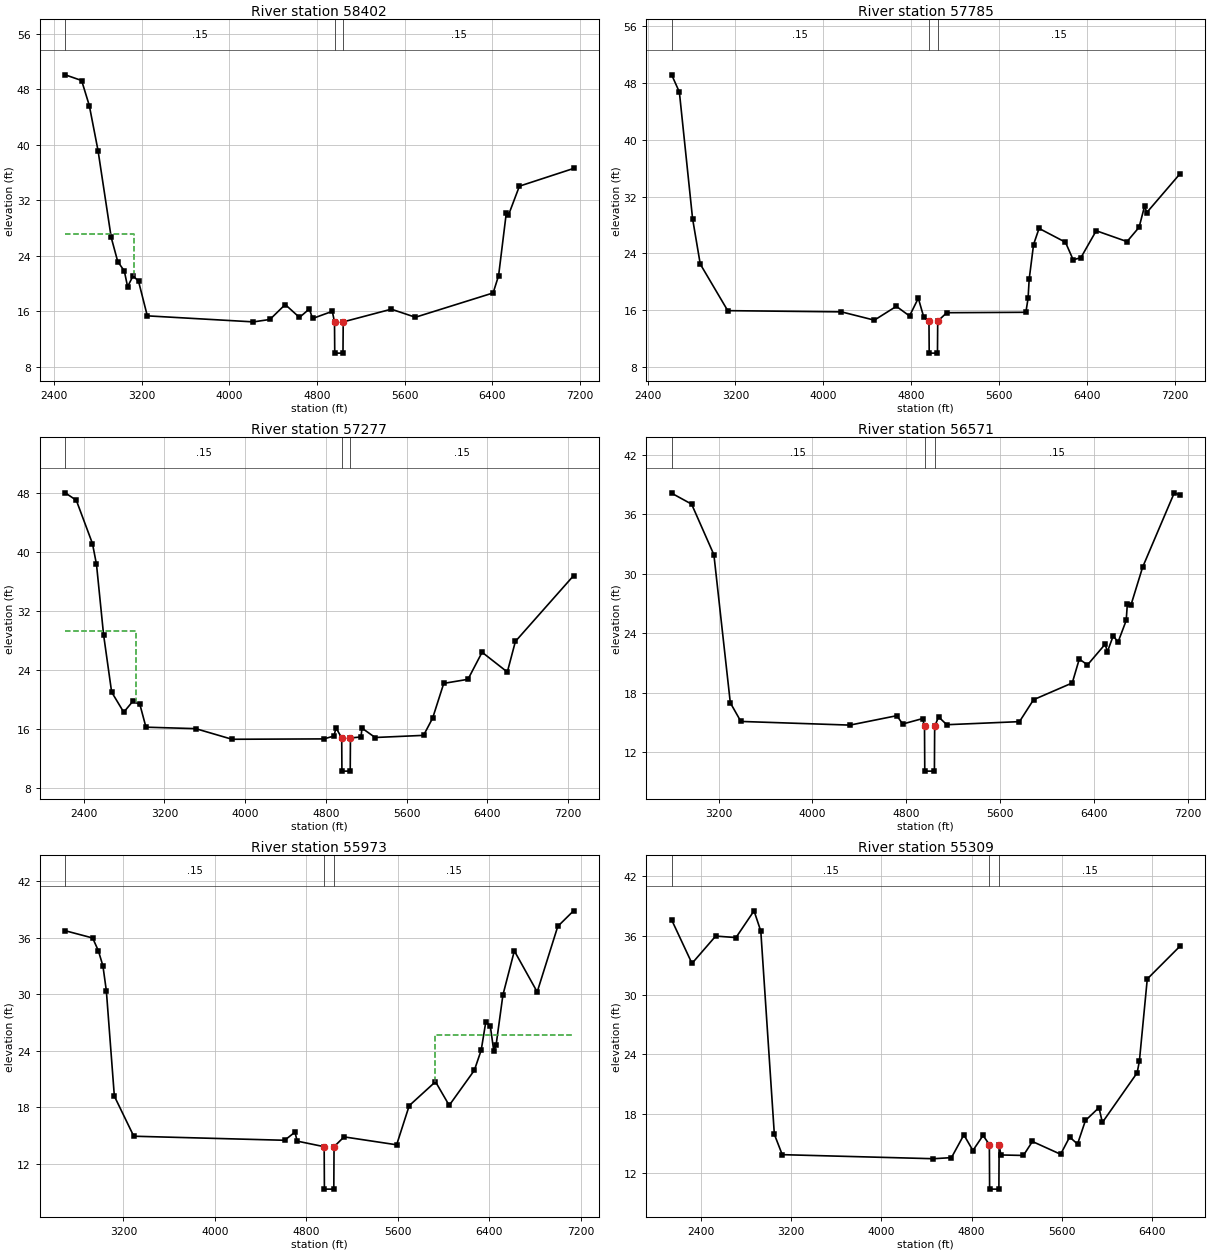
Type RM Length L Ch R = 1 ,58402   ,617,617,617
BEGIN DESCRIPTION:
Black Mingo Creek 118.0
END DESCRIPTION:
XS GIS Cut Line= 3
      2442016.18       686067.89      2440450.62       684107.12
      2439048.81       682497.33
#Sta/Elev= 30
  2500.1   50.06  2650.1   49.24  2720.1   45.64  2800.1   39.14  2920.1   26.65
  2980.1   23.15  3040.1   21.81  3070.1   19.53  3120.1   21.11  3170.1   20.32
  3250.1   15.34  4220.1   14.47  4370.1   14.82  4510.1   16.97  4640.1   15.11
  4730.1   16.33  4760.1   14.96  4940.1   15.99  4960.2   14.47  4962.4    9.97
  5037.6    9.97  5039.8   14.47  5479.2    16.3  5699.2   15.14  6409.2   18.64
  6459.2   21.13  6529.2   30.11  6549.2   29.84  6649.2   34.02  7143.8   36.57
#Mann= 3 ,-1 , 0
  2500.1     .15       0  4960.2     .05       0  5039.8     .15       0
#XS Ineff= 2 , 0
       0  3129.6   27.13               0
Permanent Ineff=
       F       F
Bank Sta=4960.2,5039.8
XS Rating Curve= 0 ,0
Exp/Cntr=0.3,0.1

Type RM Length L Ch R = 1 ,57785   ,508,508,508
BEGIN DESCRIPTION:
Black Mingo Creek 117.0
END DESCRIPTION:
XS GIS Cut Line= 4
      2442091.33       685911.78      2442029.07       685351.44
      2441005.66       683860.44       2439369.9       682312.51
#Sta/Elev= 30
  2619.6   49.18  2689.6   46.75  2809.6   28.91  2879.6   22.49  3129.6   15.92
  4163.4   15.75  4463.4   14.58  4663.4   16.53  4783.4   15.17  4863.4   17.68
  4913.4   14.97  4960.2   14.43  4962.4    9.93  5037.6    9.93  5039.8   14.43
  5121.8   15.63  5841.8   15.69  5861.8   17.66  5871.8   20.34  5911.8   25.25
  5961.8   27.52  6201.8   25.57  6271.8    23.1  6341.8   23.38  6481.8   27.19
  6761.8   25.66  6871.8   27.68  6921.8   30.67  6941.8   29.76  7243.9   35.22
#Mann= 3 ,-1 , 0
  2619.6     .15       0  4960.2     .05       0  5039.8     .15       0
Bank Sta=4960.2,5039.8
XS Rating Curve= 0 ,0
Exp/Cntr=0.3,0.1

Type RM Length L Ch R = 1 ,57277   ,706,706,706
BEGIN DESCRIPTION:
Black Mingo Creek 115.0
END DESCRIPTION:
XS GIS Cut Line= 4
      2442309.22       686145.24        2442317.       684892.31
      2441462.03       683638.42      2440091.35       681833.98
#Sta/Elev= 30
  2217.1   48.05  2327.1   47.04  2487.1   41.17  2527.1   38.34  2597.1   28.83
  2677.1   21.03  2797.1    18.3  2887.1   19.78  2957.1   19.35  3017.1   16.27
  3510.1   16.07  3870.1   14.63  4780.1   14.68  4880.1   15.07  4900.1   16.18
  4956.7   14.81  4958.9   10.31  5041.1   10.31  5043.3   14.81  5147.7   14.94
  5157.7   16.14  5287.7   14.87  5767.7   15.16  5857.7    17.5  5967.7   22.21
  6207.7   22.76  6347.7   26.43  6597.7   23.75  6677.7    27.9  7253.7   36.81
#Mann= 3 ,-1 , 0
  2217.1     .15       0  4956.7     .05       0  5043.3     .15       0
#XS Ineff= 2 , 0
       0  2916.7   29.38               0
Permanent Ineff=
       F       F
Bank Sta=4956.7,5043.3
XS Rating Curve= 0 ,0
Exp/Cntr=0.3,0.1

Type RM Length L Ch R = 1 ,56571   ,598,598,598
BEGIN DESCRIPTION:
Black Mingo Creek 114.0
END DESCRIPTION:
XS GIS Cut Line= 3
      2443657.52       684477.15      2441918.39       683120.39
      2440277.93       681763.61
#Sta/Elev= 30
  2800.7   38.12  2970.7   37.02  3160.7   31.92  3300.7   16.99  3390.7   15.11
  4320.7   14.74  4720.7   15.69  4770.7   14.85  4940.7    15.4  4956.7    14.6
  4958.9    10.1  5041.1    10.1  5043.3    14.6  5076.5   15.57  5146.5   14.78
  5766.5   15.09  5886.5    17.3  6216.5   18.99  6276.5    21.4  6346.5   20.81
  6496.5   22.89  6516.5   22.15  6566.5   23.76  6606.5   23.09  6676.5   25.29
  6686.5   26.99  6716.5   26.82  6816.5   30.66  7086.5   38.16  7135.3   37.93
#Mann= 3 ,-1 , 0
  2800.7     .15       0  4956.7     .05       0  5043.3     .15       0
Bank Sta=4956.7,5043.3
XS Rating Curve= 0 ,0
Exp/Cntr=0.3,0.1

Type RM Length L Ch R = 1 ,55973   ,664,664,664
BEGIN DESCRIPTION:
Black Mingo Creek 113.0
END DESCRIPTION:
XS GIS Cut Line= 3
      2443965.88       684205.81      2442288.41       682676.36
      2440635.66       681257.95
#Sta/Elev= 30
  2690.8   36.74  2930.8   35.97  2980.8   34.62  3020.8   33.01  3050.8   30.37
  3120.8    19.2  3290.8   14.95  4610.8   14.52  4700.8   15.38  4720.8   14.43
  4956.7   13.84  4958.9    9.34  5041.1    9.34  5043.3   13.84  5130.9   14.88
  5590.9   14.04  5700.9   18.19  5930.9   20.73  6050.9   18.22  6270.9   21.94
  6330.9   24.08  6370.9   27.06  6410.9   26.61  6440.9   23.99  6460.9   24.59
  6520.9   29.93  6620.9    34.6  6820.9   30.25  7000.9    37.2  7138.8   38.85
#Mann= 3 ,-1 , 0
  2690.8     .15       0  4956.7     .05       0  5043.3     .15       0
#XS Ineff= 2 , 0
       0                  5926.1       0    25.7
Permanent Ineff=
       F       F
Bank Sta=4956.7,5043.3
XS Rating Curve= 0 ,0
Exp/Cntr=0.3,0.1

Type RM Length L Ch R = 1 ,55309   ,545,545,545
BEGIN DESCRIPTION:
Black Mingo Creek 112.0
END DESCRIPTION:
XS GIS Cut Line= 4
      2445200.97       683513.18       2442688.6       682151.56
      2441670.41       681579.21      2441525.82       681121.35
#Sta/Elev= 30
  2140.7   37.58  2320.7   33.19  2530.7   35.95  2710.7    35.8  2870.7    38.5
  2930.7   36.45  3050.7   15.94  3120.7   13.88  4460.7   13.47  4620.7   13.58
  4730.7   15.88  4810.7    14.3  4900.7   15.82  4956.7    14.9  4958.9    10.4
  5041.1    10.4  5043.3    14.9  5058.3   13.85  5258.3    13.8  5338.3   15.21
  5588.3   13.92  5668.3   15.66  5738.3   14.95  5808.3   17.33  5928.3   18.63
  5958.3   17.13  6266.4   22.14  6286.4   23.31  6356.4   31.62  6646.5   34.93
#Mann= 3 ,-1 , 0
  2140.7     .15       0  4956.7     .05       0  5043.3     .15       0
Bank Sta=4956.7,5043.3
XS Rating Curve= 0 ,0
Exp/Cntr=0.3,0.1

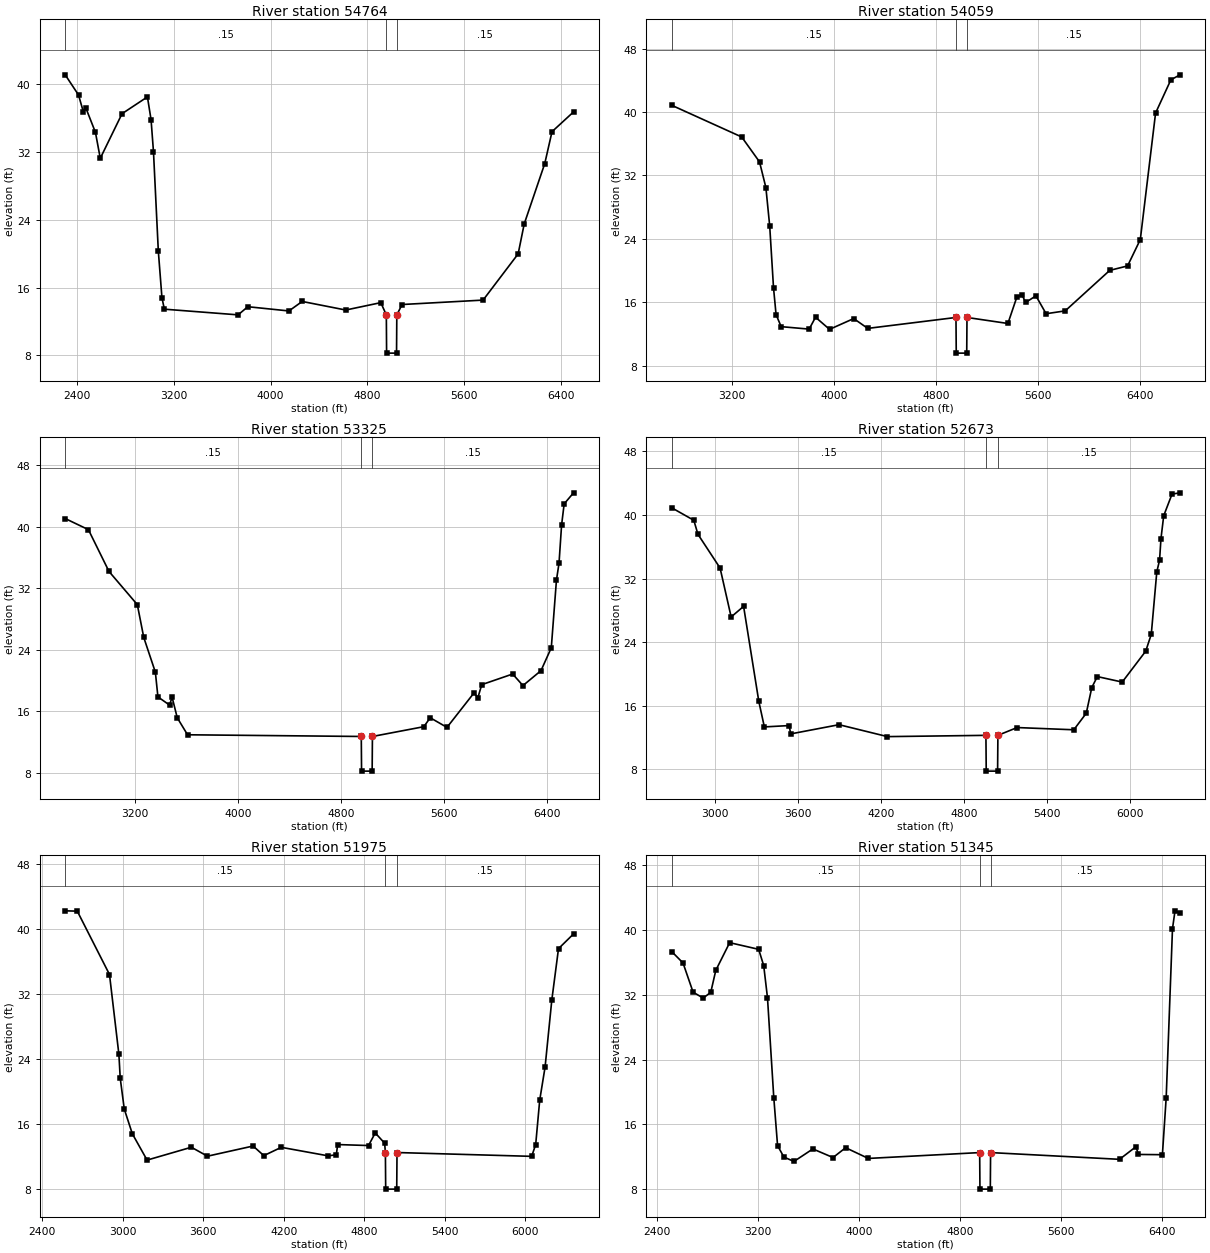
Type RM Length L Ch R = 1 ,54764   ,705,705,705
BEGIN DESCRIPTION:
Black Mingo Creek 111.0
END DESCRIPTION:
XS GIS Cut Line= 3
       2445310.3       682923.04      2442942.13       681677.29
      2441573.02        680998.9
#Sta/Elev= 30
    2301   41.07    2411    38.7    2451   36.71    2471   37.19    2551   34.29
    2591   31.23    2771   36.49    2981   38.47    3011   35.78    3031   32.01
    3071   20.31    3101    14.8    3121   13.45    3731   12.78    3811   13.74
    4151   13.24    4261   14.36    4621   13.35    4911   14.22  4956.7   12.77
  4958.9    8.27  5041.1    8.27  5043.3   12.77  5086.8      14  5756.8   14.52
  6046.8   19.97  6096.8   23.49  6266.8   30.61  6326.8   34.37  6504.8    36.7
#Mann= 3 ,-1 , 0
    2301     .15       0  4956.7     .05       0  5043.3     .15       0
Bank Sta=4956.7,5043.3
XS Rating Curve= 0 ,0
Exp/Cntr=0.3,0.1

Type RM Length L Ch R = 1 ,54059   ,734,734,734
BEGIN DESCRIPTION:
Black Mingo Creek 110.0
END DESCRIPTION:
XS GIS Cut Line= 3
      2445359.65       682096.66      2443315.18       681085.17
      2441808.96       680271.81
#Sta/Elev= 30
  2723.6   40.86  3273.6   36.86  3413.6   33.72  3463.6   30.48  3493.6   25.63
  3523.6   17.83  3543.6   14.45  3583.6   12.93  3803.6   12.62  3853.6   14.12
  3963.6   12.59  4153.6   13.95  4263.6   12.71  4956.7   14.09  4958.9    9.59
  5041.1    9.59  5043.3   14.09  5364.6   13.33  5434.6   16.65  5474.6   16.96
  5504.6   15.98  5584.6   16.82  5664.6   14.56  5814.6   14.92  6164.6   20.03
  6304.6   20.59  6404.6   23.92  6524.6   39.88  6644.6   44.07  6716.4    44.7
#Mann= 3 ,-1 , 0
  2723.6     .15       0  4956.7     .05       0  5043.3     .15       0
Bank Sta=4956.7,5043.3
XS Rating Curve= 0 ,0
Exp/Cntr=0.3,0.1

Type RM Length L Ch R = 1 ,53325   ,652,652,652
BEGIN DESCRIPTION:
Black Mingo Creek 108.0
END DESCRIPTION:
XS GIS Cut Line= 3
      2445520.28       681621.39      2443520.02       680398.35
      2442200.59        679488.6
#Sta/Elev= 30
  2657.7   41.05  2837.7   39.61  2997.7   34.18  3217.7   29.87  3267.7   25.61
  3357.7    21.1  3377.7   17.89  3467.7   16.83  3487.7   17.85  3527.7   15.18
  3607.7   12.97  4956.7   12.75  4958.9    8.25  5041.1    8.25  5043.3   12.75
  5442.2   14.02  5492.2   15.18  5622.2   13.93  5832.2   18.41  5862.2   17.79
  5892.2   19.48  6132.2   20.86  6212.2   19.36  6352.2    21.3  6432.2   24.27
  6472.2   33.05  6492.2   35.25  6512.2   40.22  6532.2   42.96  6604.9   44.39
#Mann= 3 ,-1 , 0
  2657.7     .15       0  4956.7    .045       0  5043.3     .15       0
Bank Sta=4956.7,5043.3
XS Rating Curve= 0 ,0
Exp/Cntr=0.3,0.1

Type RM Length L Ch R = 1 ,52673   ,698,698,698
BEGIN DESCRIPTION:
Black Mingo Creek 107.0
END DESCRIPTION:
XS GIS Cut Line= 3
      2445604.61       681296.05      2443821.26       679832.02
      2442730.74       679006.59
#Sta/Elev= 30
  2684.8   40.91  2844.8   39.34  2874.8   37.57  3034.8   33.33  3114.8   27.18
  3204.8   28.51  3314.8   16.56  3354.8   13.35  3534.8   13.52  3544.8   12.47
  3894.8   13.63  4244.8   12.13  4956.7   12.29  4958.9    7.79  5041.1    7.79
  5043.3   12.29  5182.1   13.27  5592.1   12.99  5682.1   15.07  5722.1    18.3
  5762.1   19.68  5942.1   18.99  6112.1   22.88  6152.1      25  6192.1   32.86
  6212.1   34.32  6222.1   37.02  6242.1   39.91  6302.1   42.63  6359.8   42.79
#Mann= 3 ,-1 , 0
  2684.8     .15       0  4956.7    .045       0  5043.3     .15       0
Bank Sta=4956.7,5043.3
XS Rating Curve= 0 ,0
Exp/Cntr=0.3,0.1

Type RM Length L Ch R = 1 ,51975   ,630,630,630
BEGIN DESCRIPTION:
Black Mingo Creek 105.0
END DESCRIPTION:
XS GIS Cut Line= 3
      2446170.95       680940.59      2444345.42       679374.13
      2443299.83       678470.42
#Sta/Elev= 30
    2571    42.2    2661   42.16    2901   34.37    2971   24.55    2981   21.61
    3011   17.83    3071   14.79    3181   11.55    3511   13.13    3631   12.03
    3971   13.28    4051    12.1    4181   13.12    4531   12.07    4591   12.21
    4601   13.46    4831   13.34    4881   14.89    4951   13.63  4956.7   12.48
  4958.9    7.98  5041.1    7.98  5043.3   12.48  6046.5   12.01  6076.5   13.46
  6106.5   18.92  6146.5   22.99  6196.5   31.21  6246.5   37.55  6358.5   39.36
#Mann= 3 ,-1 , 0
    2571     .15       0  4956.7    .045       0  5043.3     .15       0
Bank Sta=4956.7,5043.3
XS Rating Curve= 0 ,0
Exp/Cntr=0.3,0.1

Type RM Length L Ch R = 1 ,51345   ,718,718,718
BEGIN DESCRIPTION:
Black Mingo Creek 103.0
END DESCRIPTION:
XS GIS Cut Line= 3
      2446701.12       680639.34      2444833.43       678988.54
      2443694.74       677952.28
#Sta/Elev= 30
  2513.5    37.3  2603.5   35.89  2683.5   32.29  2763.5   31.57  2823.5   32.27
  2863.5   34.98  2973.5   38.39  3203.5   37.57  3243.5   35.57  3273.5   31.61
  3323.5   19.31  3353.5    13.4  3403.5   11.99  3483.5   11.45  3633.5   12.99
  3793.5   11.93  3893.5   13.14  4073.5   11.82  4956.7   12.54  4958.9    8.04
  5041.1    8.04  5043.3   12.54  6066.2   11.71  6196.2   13.26  6216.2   12.31
  6406.2   12.28  6436.2   19.28  6486.2   40.11  6506.2   42.31  6545.8   42.02
#Mann= 3 ,-1 , 0
  2513.5     .15       0  4956.7    .045       0  5043.3     .15       0
Bank Sta=4956.7,5043.3
XS Rating Curve= 0 ,0
Exp/Cntr=0.3,0.1

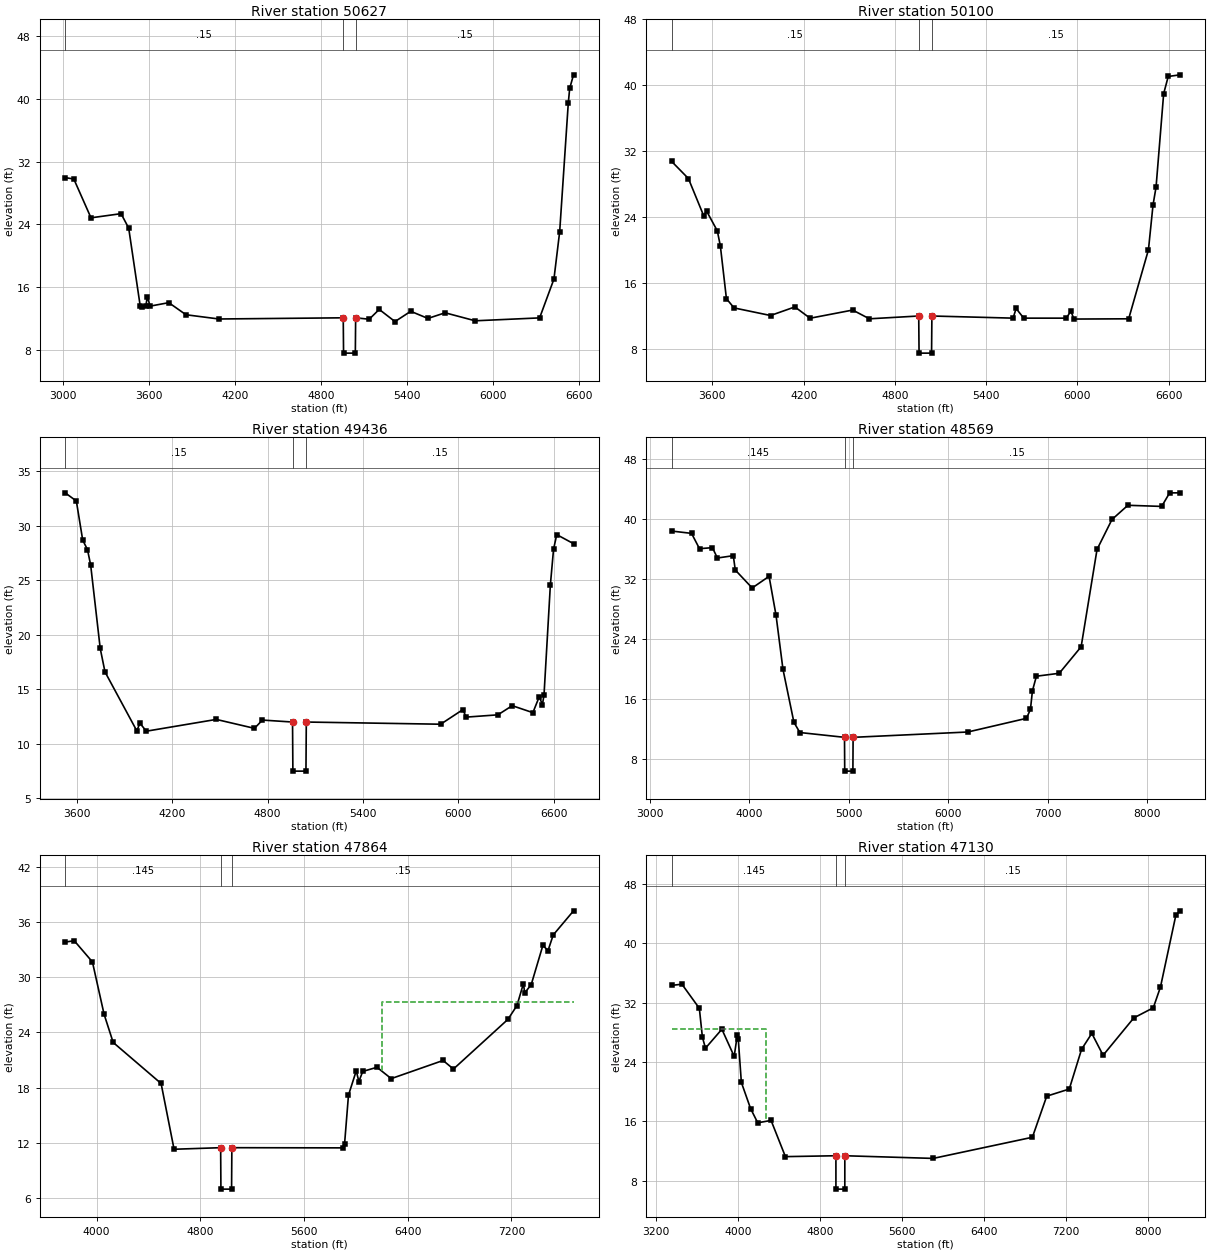
Type RM Length L Ch R = 1 ,50627   ,527,527,527
BEGIN DESCRIPTION:
Black Mingo Creek 102.0
END DESCRIPTION:
XS GIS Cut Line= 4
      2446472.17       679988.71      2446508.32       679597.05
      2445357.59       678500.54       2444100.5       677565.39
#Sta/Elev= 30
  3015.2   29.95  3075.2   29.78  3195.2   24.83  3405.2   25.36  3458.5   23.52
  3538.5   13.65  3548.5   13.49  3578.5   13.65  3588.5   14.77  3608.5   13.58
  3738.5   14.02  3858.5   12.48  4088.5   11.94  4956.7   12.09  4958.9    7.59
  5041.1    7.59  5043.3   12.09    5138   11.91    5208   13.16    5318   11.61
    5428   12.92    5548   12.01    5668   12.73    5878   11.71    6328   12.08
    6428   17.03    6468   23.06    6528   39.41    6538   41.33  6564.8   43.05
#Mann= 3 ,-1 , 0
  3015.2     .15       0  4956.7    .045       0  5043.3     .15       0
Bank Sta=4956.7,5043.3
XS Rating Curve= 0 ,0
Exp/Cntr=0.3,0.1

Type RM Length L Ch R = 1 ,50100   ,664,664,664
BEGIN DESCRIPTION:
Black Mingo Creek 101.0
END DESCRIPTION:
XS GIS Cut Line= 3
      2447146.95       678934.32      2445713.05       678108.92
      2444182.72       677397.98
#Sta/Elev= 30
  3332.5   30.76  3442.5   28.69  3542.5    24.2  3562.5   24.73  3632.5   22.35
  3652.5   20.53  3692.5   14.13  3742.5   13.01  3982.5   12.09  4142.5   13.13
  4242.5   11.76  4522.5   12.75  4632.5   11.69  4956.7   12.03  4958.9    7.53
  5041.1    7.53  5043.3   12.03    5577   11.77    5597   12.94    5647   11.77
    5927   11.77    5957   12.63    5977   11.66    6337   11.69    6467   20.06
    6497   25.48    6517   27.66    6567   38.98    6597   41.06  6674.4   41.26
#Mann= 3 ,-1 , 0
  3332.5     .15       0  4956.7    .045       0  5043.3     .15       0
Bank Sta=4956.7,5043.3
XS Rating Curve= 0 ,0
Exp/Cntr=0.3,0.1

Type RM Length L Ch R = 1 ,49436   ,867,867,867
BEGIN DESCRIPTION:
Black Mingo Creek 100.0
END DESCRIPTION:
XS GIS Cut Line= 3
       2447418.1       678319.81      2446098.64       677693.21
      2444502.11       677012.43
#Sta/Elev= 30
  3527.3   33.01  3597.3   32.26  3637.3   28.68  3667.3    27.8  3687.3    26.4
  3747.3   18.76  3777.3    16.6  3977.3    11.2  3997.3   11.89  4037.3   11.16
  4477.3   12.24  4717.3   11.42  4767.3   12.18  4956.7      12  4958.9     7.5
  5041.1     7.5  5043.3      12    5888    11.8    6028   13.14    6048   12.45
    6248   12.66    6338    13.5    6468   12.86    6508   14.32    6528    13.6
    6538   14.48    6578   24.58    6598   27.84    6618   29.18  6723.6   28.35
#Mann= 3 ,-1 , 0
  3527.3     .15       0  4956.7    .045       0  5043.3     .15       0
Bank Sta=4956.7,5043.3
XS Rating Curve= 0 ,0
Exp/Cntr=0.3,0.1

Type RM Length L Ch R = 1 ,48569   ,705,705,705
BEGIN DESCRIPTION:
Black Mingo Creek 99.0
END DESCRIPTION:
XS GIS Cut Line= 3
      2448417.71       678147.95      2444620.62       676150.58
      2444017.23        675588.8
#Sta/Elev= 30
  3217.7   38.37  3417.7   38.06  3497.7   36.02  3627.7   36.16  3677.7   34.78
  3837.7   35.09  3857.7   33.18  4027.7   30.79  4197.7   32.34  4267.7   27.16
  4337.7   19.95  4447.7    12.9  4507.7   11.54  4956.7    10.9  4958.9     6.4
  5041.1     6.4  5043.3    10.9  6197.7   11.61  6787.7   13.43  6827.7   14.63
  6847.7    17.1  6887.7   19.04  7117.7   19.43  7337.7   22.96  7497.7   35.92
  7648.1   39.91  7808.1    41.8  8148.1   41.65  8228.1   43.45  8332.5   43.46
#Mann= 3 ,-1 , 0
  3217.7    .145       0  4956.7    .045       0  5043.3     .15       0
Bank Sta=4956.7,5043.3
XS Rating Curve= 0 ,0
Exp/Cntr=0.3,0.1

Type RM Length L Ch R = 1 ,47864   ,734,734,734
BEGIN DESCRIPTION:
Black Mingo Creek 97.0
END DESCRIPTION:
XS GIS Cut Line= 3
      2448106.75       677172.57      2446986.19       676627.85
      2444612.69       675390.52
#Sta/Elev= 30
  3757.3    33.8  3827.3   33.94  3967.3   31.64  4057.3   25.96  4127.3    22.9
  4497.3   18.44  4597.3    11.3  4956.7   11.47  4958.9    6.97  5041.1    6.97
  5043.3   11.47  5903.2   11.45  5913.2   11.91  5943.2   17.17  6003.2   19.82
  6023.2   18.65  6053.2   19.75  6163.2    20.2  6273.2   18.97  6673.2   20.94
  6753.2   20.01  7173.2    25.4  7243.2    26.9  7293.2   29.29  7303.2   28.28
  7353.2   29.17  7443.2   33.43  7483.2   32.88  7523.2   34.57  7679.9   37.19
#Mann= 3 ,-1 , 0
  3757.3    .145       0  4956.7    .045       0  5043.3     .15       0
#XS Ineff= 2 , 0
       0                    6202       0   27.26
Permanent Ineff=
       F       F
Bank Sta=4956.7,5043.3
XS Rating Curve= 0 ,0
Exp/Cntr=0.3,0.1

Type RM Length L Ch R = 1 ,47130   ,814,814,814
BEGIN DESCRIPTION:
Black Mingo Creek 94.0
END DESCRIPTION:
XS GIS Cut Line= 4
      2448573.74       676721.25      2447126.26       675904.12
      2445888.93       674845.78      2445157.43       673343.86
#Sta/Elev= 30
  3353.1   34.33  3453.1   34.49  3623.1   31.24  3653.1   27.34  3683.1   25.87
  3843.1   28.42  3963.1   24.76  3993.1   27.59  4003.1    27.1  4033.1   21.26
  4123.1   17.73  4193.1   15.81  4323.1   16.13  4463.1   11.25    4956   11.37
  4956.1    6.87  5042.9    6.87    5043   11.37  5905.3   11.01  6873.5   13.86
  7013.5    19.4  7233.5   20.36  7353.5   25.72  7453.5   27.86  7563.5   24.91
  7863.5   29.95  8053.5   31.31  8123.5   34.11  8273.5   43.78  8314.1   44.38
#Mann= 3 ,-1 , 0
  3353.1    .145       0    4956    .045       0    5043     .15       0
#XS Ineff= 2 , 0
       0  4274.4   28.49               0
Permanent Ineff=
       F       F
Bank Sta=4956,5043
XS Rating Curve= 0 ,0
Exp/Cntr=0.3,0.1

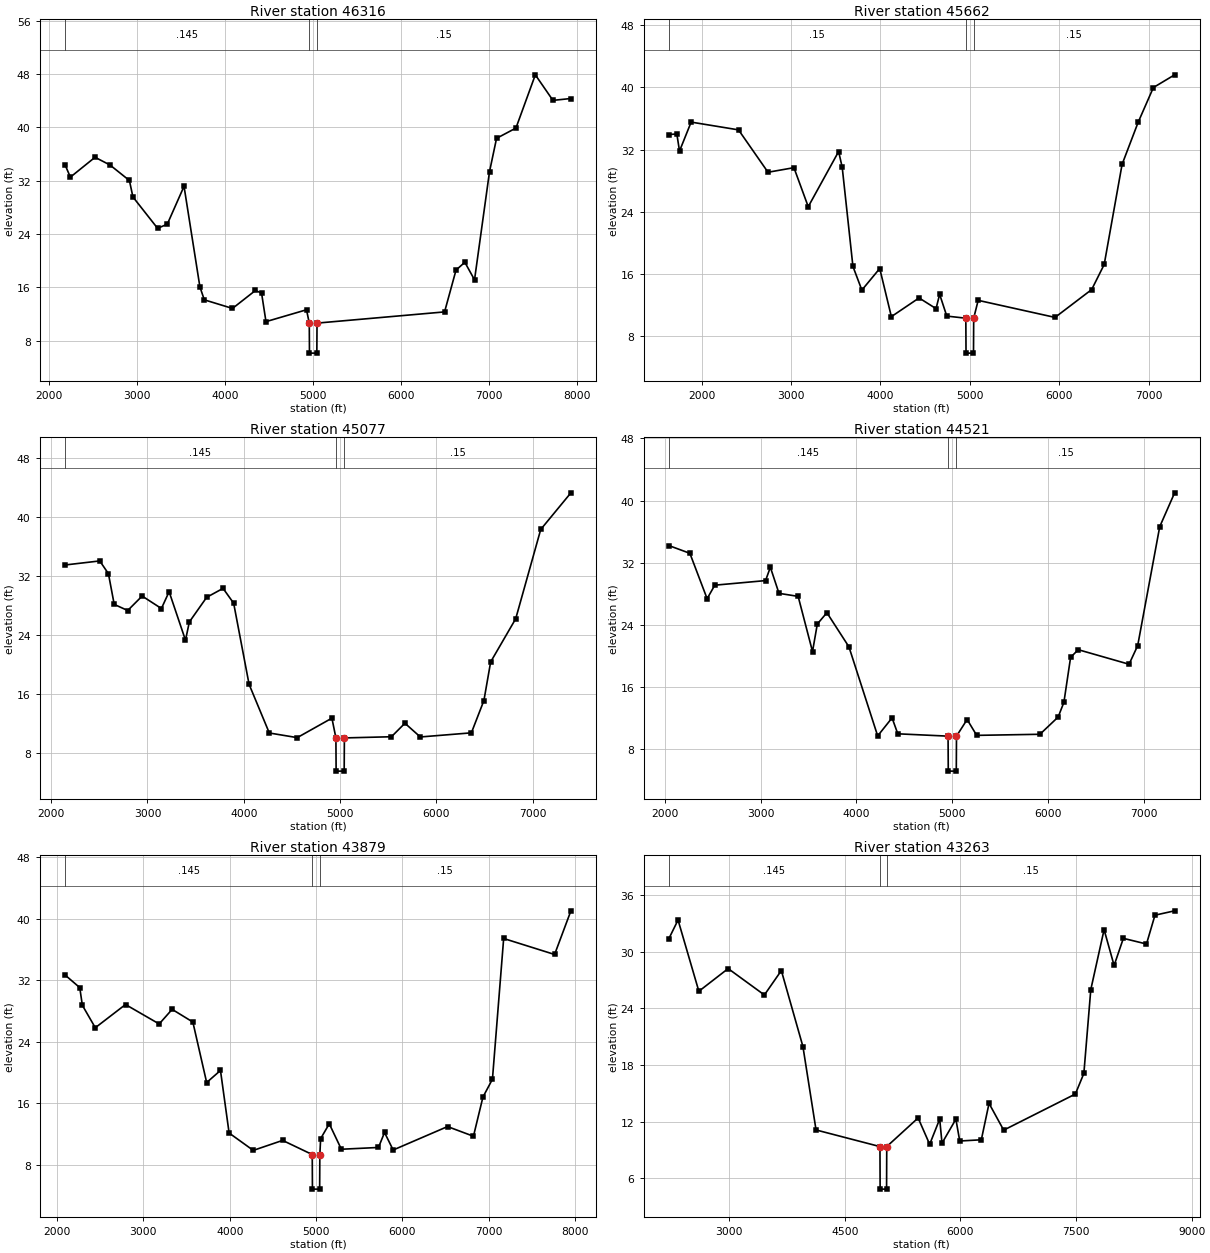
Type RM Length L Ch R = 1 ,46316   ,654,654,654
BEGIN DESCRIPTION:
Black Mingo Creek 93.0
END DESCRIPTION:
XS GIS Cut Line= 3
      2449499.65        676903.7      2447328.92       675124.21
      2445139.86       673170.95
#Sta/Elev= 30
  2184.6   34.38  2244.6   32.54  2524.6   35.52  2694.6   34.36  2914.6   32.04
  2954.6   29.57  3234.6   24.87  3344.6   25.49  3534.6   31.17  3714.6    16.1
  3764.6   14.15  4084.6   12.86  4344.6   15.55  4414.6   15.16  4464.6   10.88
  4924.6   12.66    4956   10.66  4958.2    6.16  5041.8    6.16    5044   10.66
  6491.5   12.34  6621.5   18.61  6721.5   19.78  6831.5   17.15  7001.5   33.36
  7081.5   38.36  7301.5    39.9  7521.5   47.88  7721.5   44.05  7925.3   44.33
#Mann= 3 ,-1 , 0
  2184.6    .145       0    4956    .045       0    5044     .15       0
Bank Sta=4956,5044
XS Rating Curve= 0 ,0
Exp/Cntr=0.3,0.1

Type RM Length L Ch R = 1 ,45662   ,585,585,585
BEGIN DESCRIPTION:
Black Mingo Creek 92.0
END DESCRIPTION:
XS GIS Cut Line= 3
      2449878.27       677181.35       2447813.7       674814.08
      2446117.36       672953.48
#Sta/Elev= 30
  1632.9   33.94  1722.9   34.01  1752.9   31.81  1882.9   35.54  2412.9   34.54
  2742.9   29.08  3032.9   29.67  3192.9   24.64  3532.9   31.75  3572.9   29.73
  3692.9   16.95  3792.9    13.9  3992.9   16.68  4122.9   10.48  4432.9   12.89
  4622.9   11.51  4662.9   13.36  4742.9   10.55    4956   10.28  4958.2    5.78
  5041.8    5.78    5044   10.28    5094   12.58    5954   10.38    6364   13.97
    6504    17.2    6704   30.09    6884   35.52    7054   39.99  7291.8   41.63
#Mann= 3 ,-1 , 0
  1632.9     .15       0    4956    .045       0    5044     .15       0
Bank Sta=4956,5044
XS Rating Curve= 0 ,0
Exp/Cntr=0.3,0.1

Type RM Length L Ch R = 1 ,45077   ,556,556,556
BEGIN DESCRIPTION:
Black Mingo Creek 91.0
END DESCRIPTION:
XS GIS Cut Line= 3
      2449788.36       676780.66      2448163.77       674405.18
      2446680.51       672552.71
#Sta/Elev= 30
  2144.5   33.44  2504.5   33.99  2594.5   32.26  2654.5    28.1  2794.5   27.27
  2944.5   29.23  3144.5   27.54  3224.5   29.82  3394.5   23.24  3434.5   25.72
  3614.5   29.06  3784.5   30.27  3894.5   28.26  4054.5   17.27  4264.5   10.67
  4554.5   10.04  4914.5   12.68    4956      10  4958.2     5.5  5041.8     5.5
    5044      10  5532.4   10.16  5672.4   11.99  5832.4   10.13  6362.4   10.69
  6492.4   15.07  6562.4    20.3  6822.4   26.15  7082.4   38.26  7395.5   43.22
#Mann= 3 ,-1 , 0
  2144.5    .145       0    4956    .045       0    5044     .15       0
Bank Sta=4956,5044
XS Rating Curve= 0 ,0
Exp/Cntr=0.3,0.1

Type RM Length L Ch R = 1 ,44521   ,642,642,642
BEGIN DESCRIPTION:
Black Mingo Creek 90.0
END DESCRIPTION:
XS GIS Cut Line= 3
       2449851.5       676733.39      2448577.26        674113.3
      2447343.13       672095.26
#Sta/Elev= 30
  2041.4   34.21  2261.4   33.21  2441.4   27.37  2521.4   29.11  3051.4    29.7
  3101.4   31.42  3191.4   28.06  3391.4   27.67  3541.4   20.57  3591.4   24.11
  3691.4   25.57  3921.4   21.18  4221.4    9.72  4371.4   12.04  4431.4    9.99
    4956    9.69  4958.2    5.19  5041.8    5.19    5044    9.69  5154.9   11.83
  5254.9    9.79  5914.9    9.93  6104.9   12.15  6164.9   14.04  6234.9   19.83
  6314.9   20.81  6844.9   18.94  6934.9   21.33  7164.9   36.63  7320.4   40.99
#Mann= 3 ,-1 , 0
  2041.4    .145       0    4956    .045       0    5044     .15       0
Bank Sta=4956,5044
XS Rating Curve= 0 ,0
Exp/Cntr=0.3,0.1

Type RM Length L Ch R = 1 ,43879   ,616,616,616
BEGIN DESCRIPTION:
Black Mingo Creek 88.0
END DESCRIPTION:
XS GIS Cut Line= 3
      2450135.44       676591.37      2449075.88       673870.08
      2447843.92       671201.84
#Sta/Elev= 30
    2093   32.67    2263   31.03    2293   28.73    2443   25.81    2793   28.83
    3183    26.3    3333    28.2    3573   26.55    3733   18.68    3893   20.25
    3993   12.11    4273    9.85    4613   11.15    4956    9.31  4958.2    4.81
  5041.8    4.81    5044    9.31  5053.3   11.38  5153.3   13.31  5293.3      10
  5723.3   10.23  5793.3   12.18  5893.3     9.9  6523.3   12.95  6823.3   11.69
  6933.3   16.79  7043.3   19.11  7173.3   37.42  7763.3   35.34  7952.2   41.02
#Mann= 3 ,-1 , 0
    2093    .145       0    4956    .045       0    5044     .15       0
Bank Sta=4956,5044
XS Rating Curve= 0 ,0
Exp/Cntr=0.3,0.1

Type RM Length L Ch R = 1 ,43263   ,683,683,683
BEGIN DESCRIPTION:
Black Mingo Creek 87.0
END DESCRIPTION:
XS GIS Cut Line= 4
      2450217.84       676640.47      2449623.14       673930.88
      2449015.36       671164.47      2449141.56       670217.92
#Sta/Elev= 30
  2216.8   31.35  2336.8   33.34  2606.8    25.8  2986.8    28.2  3456.8   25.41
  3676.8   27.99  3956.8   19.95  4126.8   11.13    4956    9.37  4958.2    4.87
  5041.8    4.87    5044    9.37  5450.9    12.4  5600.9    9.61  5730.9   12.28
  5760.9    9.73  5940.9   12.27  5990.9    9.96  6270.9   10.09  6370.9   13.94
  6560.9   11.11  7490.9   14.93  7600.9   17.11  7690.9   25.98  7863.3   32.32
  7993.3   28.53  8113.3    31.4  8413.3    30.8  8523.3   33.85  8778.2   34.31
#Mann= 3 ,-1 , 0
  2216.8    .145       0    4956    .045       0    5044     .15       0
Bank Sta=4956,5044
XS Rating Curve= 0 ,0
Exp/Cntr=0.3,0.1

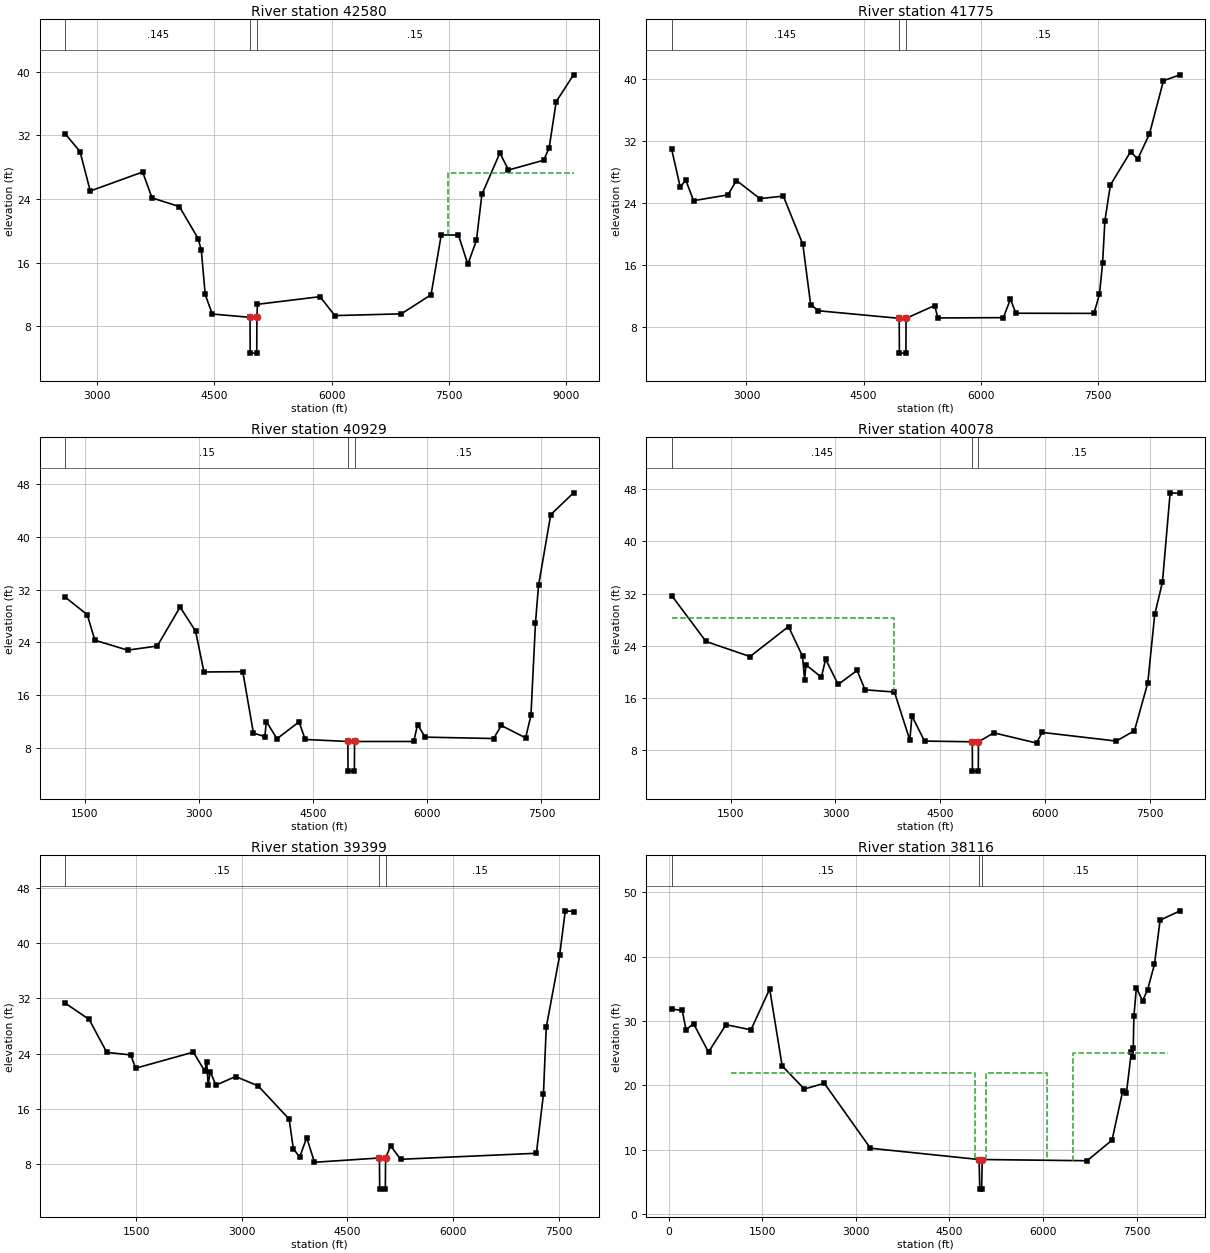
Type RM Length L Ch R = 1 ,42580   ,805,805,805
BEGIN DESCRIPTION:
Black Mingo Creek 86.0
END DESCRIPTION:
XS GIS Cut Line= 3
      2450363.76       676572.31      2450243.37       674137.63
      2449634.08       670121.95
#Sta/Elev= 30
    2593   32.19    2783   29.95    2913      25    3583   27.39    3703   24.13
    4053   23.04    4293   19.01    4333   17.55    4383   11.99    4473    9.53
    4956    9.11  4958.2    4.61  5041.8    4.61    5044    9.11  5050.7   10.75
  5850.7   11.71  6040.7    9.33  6890.7    9.55  7270.7   11.96  7400.7   19.48
  7620.7   19.46  7740.7   15.78  7850.7   18.79  7920.7   24.57  8150.7   29.78
  8260.7   27.64  8710.7   28.87  8780.7   30.43  8870.7   36.24  9092.3   39.61
#Mann= 3 ,-1 , 0
    2593    .145       0    4956    .045       0    5044     .15       0
#XS Ineff= 2 , 0
       0                  7483.3       0   27.21
Permanent Ineff=
       F       F
Bank Sta=4956,5044
XS Rating Curve= 0 ,0
Exp/Cntr=0.3,0.1

Type RM Length L Ch R = 1 ,41775   ,846,846,846
BEGIN DESCRIPTION:
Black Mingo Creek 85.0
END DESCRIPTION:
XS GIS Cut Line= 3
      2450762.66       676533.42      2450693.34       673505.23
      2449955.14       670102.47
#Sta/Elev= 30
  2041.6   30.94  2151.6   26.04  2221.6   26.98  2321.6    24.3  2761.6   25.05
  2871.6   26.91  3171.6   24.57  3471.6   24.89  3721.6   18.65  3821.6   10.87
  3921.6   10.06    4956    9.08  4958.2    4.58  5041.8    4.58    5044    9.08
  5410.6   10.74  5450.6    9.13  6290.6    9.17  6380.6   11.57  6450.6    9.74
  7450.6    9.72  7520.6   12.19  7560.6   16.18  7590.6   21.71  7660.6   26.32
  7920.6   30.65  8010.6   29.68  8160.6   32.91  8340.6   39.82  8552.5   40.58
#Mann= 3 ,-1 , 0
  2041.6    .145       0    4956    .045       0    5044     .15       0
Bank Sta=4956,5044
XS Rating Curve= 0 ,0
Exp/Cntr=0.3,0.1

Type RM Length L Ch R = 1 ,40929   ,851,851,851
BEGIN DESCRIPTION:
Black Mingo Creek 83.0
END DESCRIPTION:
XS GIS Cut Line= 4
      2450898.87       676659.88      2451463.15        675190.8
      2451264.92        672982.3      2450597.26       670170.59
#Sta/Elev= 30
  1241.1   30.88  1531.1   28.21  1631.1   24.34  2061.1   22.84  2451.1   23.46
  2751.1   29.38  2954.8   25.72  3064.8   19.52  3574.8   19.57  3714.8   10.25
  3864.8    9.71  3884.8   11.99  4024.8    9.39  4314.8   11.95  4394.8    9.28
    4956    8.97  4958.2    4.47  5041.8    4.47    5044    8.97  5822.2    8.97
  5872.2   11.53  5972.2    9.63  6872.2    9.42  6972.2    11.4  7292.2    9.52
  7362.2   12.92  7422.2      27  7462.2   32.66  7622.2    43.4  7922.1   46.72
#Mann= 3 ,-1 , 0
  1241.1     .15       0    4956    .045       0    5044     .15       0
Bank Sta=4956,5044
XS Rating Curve= 0 ,0
Exp/Cntr=0.3,0.1

Type RM Length L Ch R = 1 ,40078   ,679,679,679
BEGIN DESCRIPTION:
Black Mingo Creek 81.0
END DESCRIPTION:
XS GIS Cut Line= 4
      2450973.05       676691.52       2452107.7       674203.76
      2451909.48       672605.29      2451300.33       669748.62
#Sta/Elev= 30
     659   31.69    1149   24.65    1779   22.33    2329   26.93    2529   22.39
    2559   18.78    2579   21.07    2799   19.15    2859   21.93    3039   18.05
    3309    20.2  3423.3   17.23  3843.3   16.89  4063.3    9.51  4093.3   13.22
  4273.3    9.37    4956    9.26  4958.2    4.76  5041.8    4.76    5044    9.26
    5264   10.63    5874    9.07    5954    10.7    7014    9.37    7274   10.96
    7464   18.27    7564    28.8    7674   33.74    7784   47.44  7924.9   47.35
#Mann= 3 ,-1 , 0
     659    .145       0    4956    .045       0    5044     .15       0
#XS Ineff= 2 , 0
       0  3830.4   28.32               0
Permanent Ineff=
       F       F
Bank Sta=4956,5044
XS Rating Curve= 0 ,0
Exp/Cntr=0.3,0.1

Type RM Length L Ch R = 1 ,39399   ,1283,1283,1283
BEGIN DESCRIPTION:
Black Mingo Creek 80.0
END DESCRIPTION:
XS GIS Cut Line= 4
      2450989.05       676752.34      2452681.62       673639.57
      2452578.35        672666.1      2452049.35         670021.
#Sta/Elev= 30
   493.6   31.29   833.6   28.94  1083.6   24.18  1423.6   23.81  1493.6   21.89
  2313.6   24.21  2473.6   21.51  2503.6   22.77  2523.6    19.5  2553.6   21.39
  2633.6   19.44  2913.6   20.69  3233.6   19.34  3673.6   14.54  3733.6   10.27
  3823.6    9.04  3923.6   11.85  4033.6     8.3    4956    8.92    4960    4.42
    5040    4.42    5044    8.92  5115.7   10.69  5255.7    8.73  7185.7     9.6
  7285.7   18.11  7325.7   27.79  7515.7   38.19  7595.7   44.63  7713.2   44.53
#Mann= 3 ,-1 , 0
   493.6     .15       0    4956    .045       0    5044     .15       0
Bank Sta=4956,5044
XS Rating Curve= 0 ,0
Exp/Cntr=0.5,0.3

Type RM Length L Ch R = 1 ,38116   ,228,228,228
BEGIN DESCRIPTION:
Railroad at Black Mingo Creek - US
END DESCRIPTION:
XS GIS Cut Line= 4
      2456010.54       676497.17      2454785.12       674947.93
      2454429.51       674334.43      2452358.18       669283.89
#Sta/Elev= 30
    49.9   31.87   219.9   31.66   279.9   28.63   399.9   29.61   639.9   25.19
   919.9   29.44  1319.9   28.65  1619.9   34.98  1819.9   23.04  2175.2   19.45
  2495.2   20.34  3234.3   10.25    4975     8.5    4985     3.9    5015     3.9
    5025     8.5  6704.3    8.31  7104.3   11.51  7274.3    19.1  7334.3   18.77
  7414.3   25.27  7434.3   24.38  7444.3   25.79  7454.3   30.75  7494.3   35.15
  7594.3   33.16  7674.3   34.87  7784.3   38.84  7874.3   45.68  8193.1   47.13
#Mann= 3 ,-1 , 0
    49.9     .15       0    4975    .045       0    5025     .15       0
#XS Ineff= 3 ,-1
    1000    4910      22    5090  6063.5      22  6473.5    8000   24.97
Permanent Ineff=
       F       F       F
Bank Sta=4975,5025
XS Rating Curve= 0 ,0
Exp/Cntr=0.5,0.3