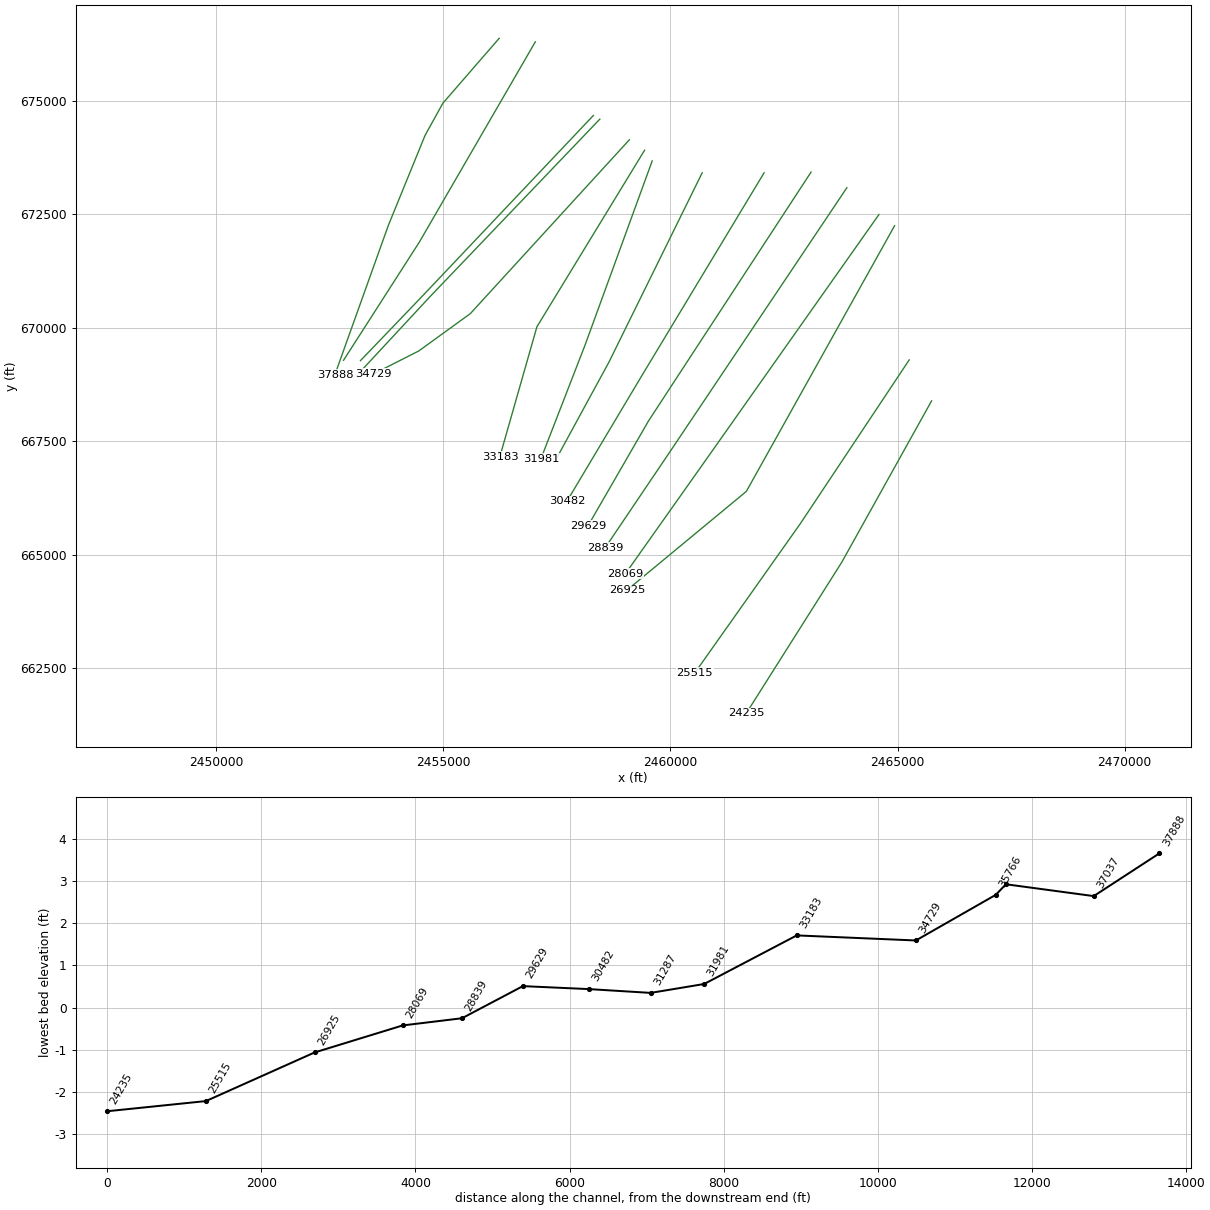
HEC-RAS study Black Mingo Creek.prj: Black Mingo Creek Limited Detail Study

--- Black Mingo Creek.g04 (geometry) --- (continued)

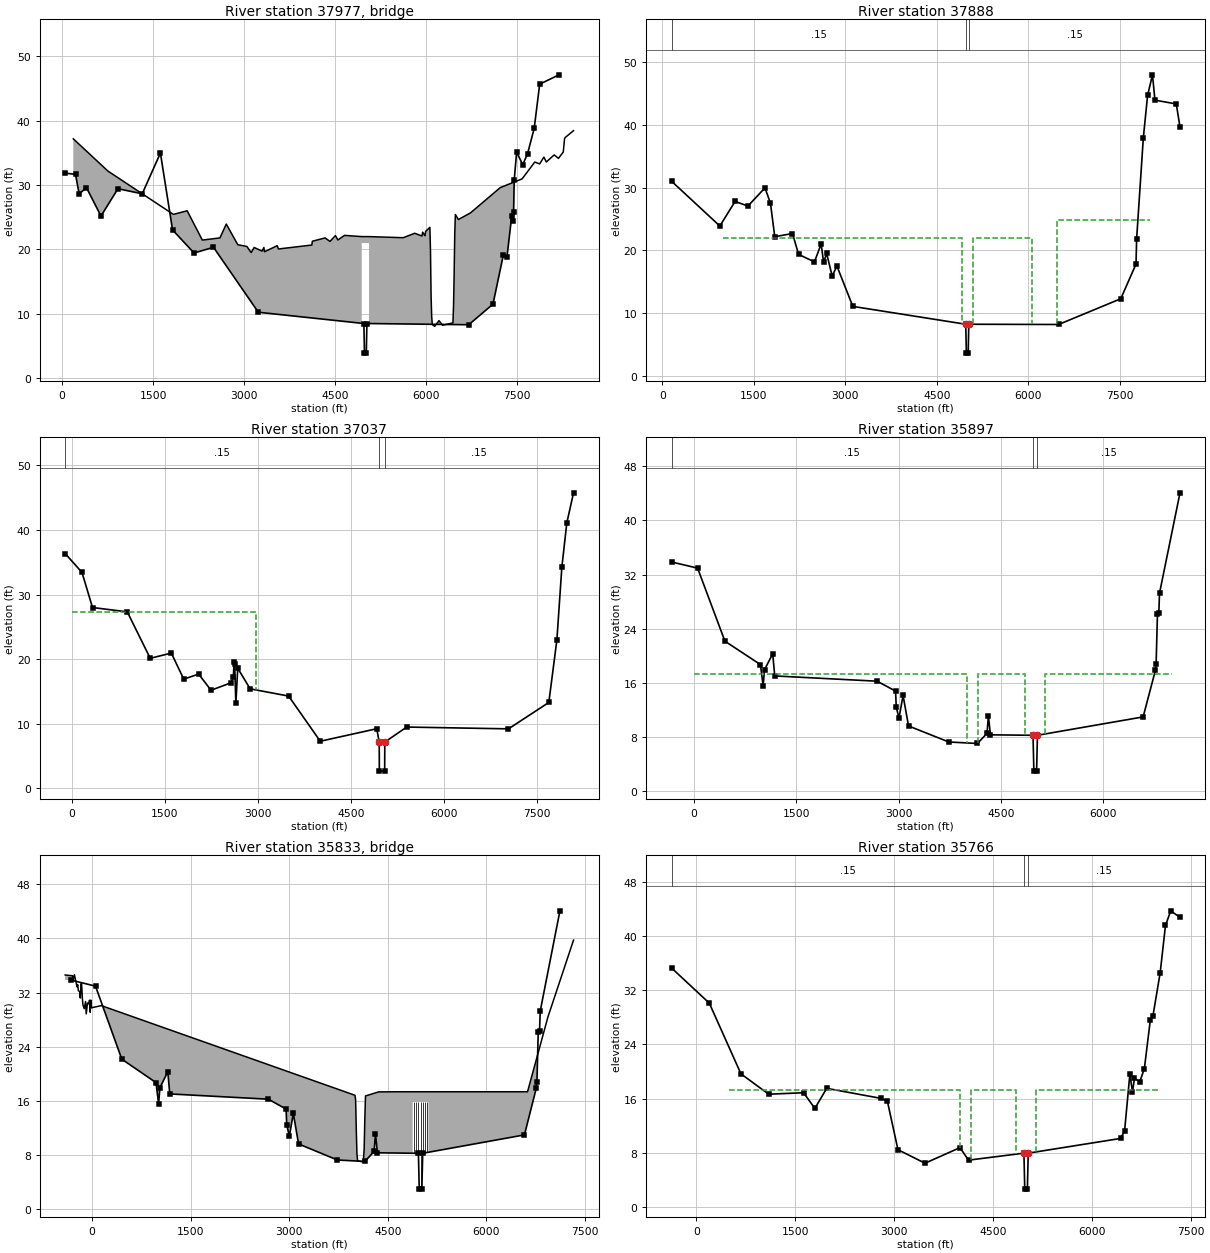
Type RM Length L Ch R = 3 ,37977   ,,,
BEGIN DESCRIPTION:
Railroad at Black Mingo Creek - TOR
Structure ID: LDS_BMC_03
Approximate Survey Structure
END DESCRIPTION:
Bridge Culvert--1,0,-1,-1, 0
Deck Dist Width WeirC Skew NumUp NumDn MinLoCord MaxHiCord MaxSubmerge Is_Ogee
129,20,3,0, 60, 60, , , 0.95, 0, 1,1,,
   183.2   753.2  1833.2  2061.3  2311.3  2601.3  2706.1  2896.1  3046.1  3116.1
  3166.1  3296.1  3326.1  3336.1  3546.1  3566.1  4116.1  4126.1  4336.1  4416.1
  4506.1  4546.1  4656.1    4940    4940    5060    5060  5623.5  5813.5  5933.5
  5943.5  5983.5  5993.5  6063.5  6073.5  6083.5  6093.5  6103.5  6143.5  6213.5
  6273.5  6443.5  6453.5  6463.5  6473.5  6483.5  6533.5  6733.5  7223.5  7583.5
  7793.5  7873.5  7943.5  7983.5  8113.5  8183.5  8263.5  8283.5  8293.5  8432.5
   37.19   32.19   25.45   26.01   21.46    21.8   23.95   20.74   20.47   19.52
   20.31   19.75   20.31   19.65   20.59   20.08   20.69   21.28    21.8   21.25
   22.16   21.48   22.19      22      22      22      22   21.83   22.52   22.09
   22.69   22.14   22.81   23.44   19.84   12.81     9.6    8.34    8.06    8.95
    8.23     8.6   11.15   16.02    22.3   25.44   24.65   25.69   29.61   30.96
   33.58   33.29   34.35   33.59   34.69   34.15   35.14   37.15   37.38   38.46
   -16.1   -16.1   -16.1   -16.1   -16.1   -16.1   -16.1   -16.1   -16.1   -16.1
   -16.1   -16.1   -16.1   -16.1   -16.1   -16.1   -16.1   -16.1   -16.1   -16.1
   -16.1   -16.1   -16.1   -16.1      21      21   -16.1   -16.1   -16.1   -16.1
   -16.1   -16.1   -16.1   -16.1   -16.1   -16.1   -16.1   -16.1   -16.1   -16.1
   -16.1   -16.1   -16.1   -16.1   -16.1   -16.1   -16.1   -16.1   -16.1   -16.1
   -16.1   -16.1   -16.1   -16.1   -16.1   -16.1   -16.1   -16.1   -16.1   -16.1
   183.2   753.2  1833.2  2061.3  2311.3  2601.3  2706.1  2896.1  3046.1  3116.1
  3166.1  3296.1  3326.1  3336.1  3546.1  3566.1  4116.1  4126.1  4336.1  4416.1
  4506.1  4546.1  4656.1    4940    4940    5060    5060  5623.5  5813.5  5933.5
  5943.5  5983.5  5993.5  6063.5  6073.5  6083.5  6093.5  6103.5  6143.5  6213.5
  6273.5  6443.5  6453.5  6463.5  6473.5  6483.5  6533.5  6733.5  7223.5  7583.5
  7793.5  7873.5  7943.5  7983.5  8113.5  8183.5  8263.5  8283.5  8293.5  8432.5
   37.19   32.19   25.45   26.01   21.46    21.8   23.95   20.74   20.47   19.52
   20.31   19.75   20.31   19.65   20.59   20.08   20.69   21.28    21.8   21.25
   22.16   21.48   22.19      22      22      22      22   21.83   22.52   22.09
   22.69   22.14   22.81   23.44   19.84   12.81     9.6    8.34    8.06    8.95
    8.23     8.6   11.15   16.02    22.3   25.44   24.65   25.69   29.61   30.96
   33.58   33.29   34.35   33.59   34.69   34.15   35.14   37.15   37.38   38.46
   -16.1   -16.1   -16.1   -16.1   -16.1   -16.1   -16.1   -16.1   -16.1   -16.1
   -16.1   -16.1   -16.1   -16.1   -16.1   -16.1   -16.1   -16.1   -16.1   -16.1
   -16.1   -16.1   -16.1   -16.1      21      21   -16.1   -16.1   -16.1   -16.1
   -16.1   -16.1   -16.1   -16.1   -16.1   -16.1   -16.1   -16.1   -16.1   -16.1
   -16.1   -16.1   -16.1   -16.1   -16.1   -16.1   -16.1   -16.1   -16.1   -16.1
   -16.1   -16.1   -16.1   -16.1   -16.1   -16.1   -16.1   -16.1   -16.1   -16.1
Abutment Skew #Up #Dn= , 2 , 2
    4940    4950
      21    8.31
    4940    4950
      21    8.03
Abutment Skew #Up #Dn= , 2 , 2
    5050    5060
    8.98      21
    5050    5060
    8.04      21
BR Coef= 1 , 1 , 0 ,1.25, 0 ,,,0.8,0,2,0,
WSPro=,,,, 1 ,,,, 0 ,,,, 0 ,,,,-1 ,-1 ,-1 , 0 , 0 , 0 , 0 , 0
BC Design=,, 0 ,, 0 ,,,,,,
BC HTab HWMax=47.49
BC Use User HTab Curves=0
BC User HTab FreeFlow(D)= 0

Type RM Length L Ch R = 1 ,37888   ,851,851,851
BEGIN DESCRIPTION:
Railroad at Black Mingo Creek - DS
END DESCRIPTION:
XS GIS Cut Line= 5
      2456229.74       676371.81      2454990.78       674943.22
      2454598.87       674235.25      2453789.77       672250.41
      2452614.02       668963.38
#Sta/Elev= 30
   153.3   31.01   943.3   23.89  1193.3   27.81  1403.3   27.07  1683.3   29.97
  1773.3   27.51  1843.3   22.19  2134.3    22.7  2234.3   19.38  2494.3   18.17
  2604.3   21.05  2644.3   18.11  2694.3   19.52  2784.3   15.94  2863.5    17.5
  3123.5   11.09    4975    8.25    4985    3.65    5015    3.65    5025    8.25
  6496.9    8.21  7516.9   12.31  7766.9   17.84  7776.9   21.87  7886.9   37.97
  7956.9   44.71  8036.9   47.97  8076.9   43.94  8426.9   43.33  8487.9   39.66
#Mann= 3 ,-1 , 0
   153.3     .15       0    4975    .045       0    5025     .15       0
#XS Ineff= 3 ,-1
    1000    4910      22    5090  6063.5      22  6473.5    8000    24.9
Permanent Ineff=
       F       F       F
Bank Sta=4975,5025
XS Rating Curve= 0 ,0
Exp/Cntr=0.5,0.3

Type RM Length L Ch R = 1 ,37037   ,1140,1140,1140
BEGIN DESCRIPTION:
Black Mingo Creek 69.0
END DESCRIPTION:
XS GIS Cut Line= 3
      2457026.18       676295.92      2454475.52       671887.77
      2452803.67       669279.48
#Sta/Elev= 30
  -104.8   36.35   165.2   33.43   335.2   27.99   895.2   27.32  1265.2   20.12
  1605.2   20.93  1805.2   16.89  2045.2   17.68  2245.2   15.17  2565.2   16.32
  2605.2   17.17  2615.2   19.52  2625.2   19.19  2645.2   13.17  2675.2   18.58
  2875.2   15.39  3495.2   14.27  4005.2    7.27  4915.2    9.21    4955    7.14
  4957.2    2.64  5042.8    2.64    5045    7.14  5398.1    9.47  7038.1    9.19
  7688.1   13.28  7818.1   22.98  7898.1   34.25  7978.1   41.11  8086.2   45.76
#Mann= 3 ,-1 , 0
  -104.8     .15       0    4955    .045       0    5045     .15       0
#XS Ineff= 2 , 0
       0  2963.7   27.32               0
Permanent Ineff=
       F       F
Bank Sta=4955,5045
XS Rating Curve= 0 ,0
Exp/Cntr=0.5,0.3

Type RM Length L Ch R = 1 ,35897   ,131,131,131
BEGIN DESCRIPTION:
State Road 121 - US
END DESCRIPTION:
XS GIS Cut Line= 3
      2458304.35        674672.7      2454572.32       670728.28
      2453176.64       669271.92
#Sta/Elev= 30
  -326.4   33.85    53.7   32.94   453.7   22.14   973.7   18.68  1013.7   15.56
  1033.7   17.91  1153.7   20.28  1183.7      17  2683.7   16.22  2953.7   14.76
  2963.7   12.41  3003.7   10.76  3063.7   14.11  3143.7     9.6  3733.7    7.23
  4153.7    7.01  4293.7    8.51  4313.7   11.09  4343.7    8.29  4967.5    8.22
    4980    2.92    5020    2.92  5032.5    8.22  6580.9   10.94  6760.9   17.84
  6770.9   18.72  6790.9   26.23  6810.9   26.38  6820.9   29.24  7120.9   44.08
#Mann= 3 ,-1 , 0
  -326.4     .15       0  4967.5    .045       0  5032.5     .15       0
#XS Ineff= 3 ,-1
       0  4003.6   17.32  4163.6    4850   17.32    5150    7000   17.32
Permanent Ineff=
       F       F       F
Bank Sta=4967.5,5032.5
XS Rating Curve= 0 ,0
Exp/Cntr=0.5,0.3

Type RM Length L Ch R = 3 ,35833   ,,,
BEGIN DESCRIPTION:
State Road 121 - TOR
Structure ID: LDS_BMC_02
Approximate Survey Structure
END DESCRIPTION:
Bridge Culvert--1,0,-1,-1, 0
Deck Dist Width WeirC Skew NumUp NumDn MinLoCord MaxHiCord MaxSubmerge Is_Ogee
49,34,3,0, 42, 42, , , 0.95, 0, 1,1,,
  -407.4  -297.4  -287.4  -267.4  -227.4  -217.4  -207.4  -187.4  -177.4  -167.4
  -157.4  -147.4  -137.4  -117.4   -97.4   -87.4   -67.4   -47.4   -37.4   -27.4
   -17.4    -7.4   143.2  4002.1  4012.1  4022.1  4032.1  4042.1  4122.1  4132.1
  4142.1  4152.1  4162.1  4362.1  4639.1    4880    4880    5120    5120  6627.9
    6939  7327.9
   34.59   34.48   33.95   34.62   32.84   33.17   32.28   32.12   31.18   33.31
   33.22    31.3   30.15   29.61   30.66   28.84   30.45   30.31   30.86   29.08
   30.88   29.74   30.06    16.8   16.11   11.66    8.13     7.1    6.96    7.45
     8.9    13.4    16.7    17.3   17.32   17.32   17.32   17.32   17.32   17.32
    28.4   39.75
  -16.14  -16.14  -16.14  -16.14  -16.14  -16.14  -16.14  -16.14  -16.14  -16.14
  -16.14  -16.14  -16.14  -16.14  -16.14  -16.14  -16.14  -16.14  -16.14  -16.14
  -16.14  -16.14  -16.14  -16.14  -16.14  -16.14  -16.14  -16.14  -16.14  -16.14
  -16.14  -16.14  -16.14  -16.14  -16.14  -16.14   15.82   15.82  -16.14  -16.14
  -16.14  -16.14
  -407.4  -297.4  -287.4  -267.4  -227.4  -217.4  -207.4  -187.4  -177.4  -167.4
  -157.4  -147.4  -137.4  -117.4   -97.4   -87.4   -67.4   -47.4   -37.4   -27.4
   -17.4    -7.4   143.2  4002.1  4012.1  4022.1  4032.1  4042.1  4122.1  4132.1
  4142.1  4152.1  4162.1  4362.1  4639.1    4880    4880    5120    5120  6627.9
    6939  7327.9
   34.59   34.48   33.95   34.62   32.84   33.17   32.28   32.12   31.18   33.31
   33.22    31.3   30.15   29.61   30.66   28.84   30.45   30.31   30.86   29.08
   30.88   29.74   30.06    16.8   16.11   11.66    8.13     7.1    6.96    7.45
     8.9    13.4    16.7    17.3   17.32   17.32   17.32   17.32   17.32   17.32
    28.4   39.75
  -16.14  -16.14  -16.14  -16.14  -16.14  -16.14  -16.14  -16.14  -16.14  -16.14
  -16.14  -16.14  -16.14  -16.14  -16.14  -16.14  -16.14  -16.14  -16.14  -16.14
  -16.14  -16.14  -16.14  -16.14  -16.14  -16.14  -16.14  -16.14  -16.14  -16.14
  -16.14  -16.14  -16.14  -16.14  -16.14  -16.14   15.82   15.82  -16.14  -16.14
  -16.14  -16.14
Pier Skew, UpSta & Num, DnSta & Num=  ,4897.1, 2 ,4897.1, 2 , 0 , 0 , 0 ,0,0
       1       1
    8.17   15.82
       1       1
    8.42   15.82
Pier Skew, UpSta & Num, DnSta & Num=  ,4931.4, 2 ,4931.4, 2 , 0 , 0 , 0 ,0,0
       1       1
    8.44   15.82
       1       1
     8.3   15.82
Pier Skew, UpSta & Num, DnSta & Num=  ,4965.7, 2 ,4965.7, 2 , 0 , 0 , 0 ,0,0
       1       1
    8.23   15.82
       1       1
    7.99   15.82
Pier Skew, UpSta & Num, DnSta & Num=  ,5000, 2 ,5000, 2 , 0 , 0 , 0 ,0,0
       1       1
    2.92   15.82
       1       1
    2.67   15.82
Pier Skew, UpSta & Num, DnSta & Num=  ,5034.3, 2 ,5034.3, 2 , 0 , 0 , 0 ,0,0
       1       1
    8.22   15.82
       1       1
       8   15.82
Pier Skew, UpSta & Num, DnSta & Num=  ,5068.6, 2 ,5068.6, 2 , 0 , 0 , 0 ,0,0
       1       1
    8.31   15.82
       1       1
    8.51   15.82
Pier Skew, UpSta & Num, DnSta & Num=  ,5102.9, 2 ,5102.9, 2 , 0 , 0 , 0 ,0,0
       1       1
    8.39   15.82
       1       1
    8.46   15.82
Abutment Skew #Up #Dn= , 2 , 2
    4880  4894.5
   15.82    8.08
    4880  4894.5
   15.82    8.33
Abutment Skew #Up #Dn= , 2 , 2
  5105.5    5120
    8.39   15.82
  5105.5    5120
    8.35   15.82
BR Coef= 1 , 1 , 0 ,1.25, 0 ,,,0.8,0,2,0,
WSPro=,,,, 1 ,,,, 0 ,,,, 0 ,,,,-1 ,-1 ,-1 , 0 , 0 , 0 , 0 , 0
BC Design=,, 0 ,, 0 ,,,,,,
BC HTab HWMax=44.08
BC Use User HTab Curves=0
BC User HTab FreeFlow(D)= 0

Type RM Length L Ch R = 1 ,35766   ,1037,1037,1037
BEGIN DESCRIPTION:
State Road 121 - DS
END DESCRIPTION:
XS GIS Cut Line= 3
      2458445.93       674591.77       2454703.8       670677.71
      2453146.28       668998.83
#Sta/Elev= 30
    -372   35.24     198   30.08     678   19.66    1098   16.66    1628   16.87
    1798   14.56    1978   17.52    2808   16.03    2898   15.62    3058    8.48
    3468    6.49    3998    8.78    4128    6.94  4967.5    7.97    4980    2.67
    5020    2.67  5032.5    7.97  6433.1   10.14  6493.1   11.24  6573.1   19.61
  6613.1   17.01  6643.1   19.02  6723.1   18.47  6793.1   20.44  6883.1   27.56
  6923.1    28.2  7033.1   34.58  7113.1   41.53  7193.1   43.68  7333.2   42.71
#Mann= 3 ,-1 , 0
    -372     .15       0  4967.5    .045       0  5032.5     .15       0
#XS Ineff= 3 ,-1
     500  4003.6   17.32  4163.6    4850   17.32    5150    7000   17.32
Permanent Ineff=
       F       F       F
Bank Sta=4967.5,5032.5
XS Rating Curve= 0 ,0
Exp/Cntr=0.5,0.3

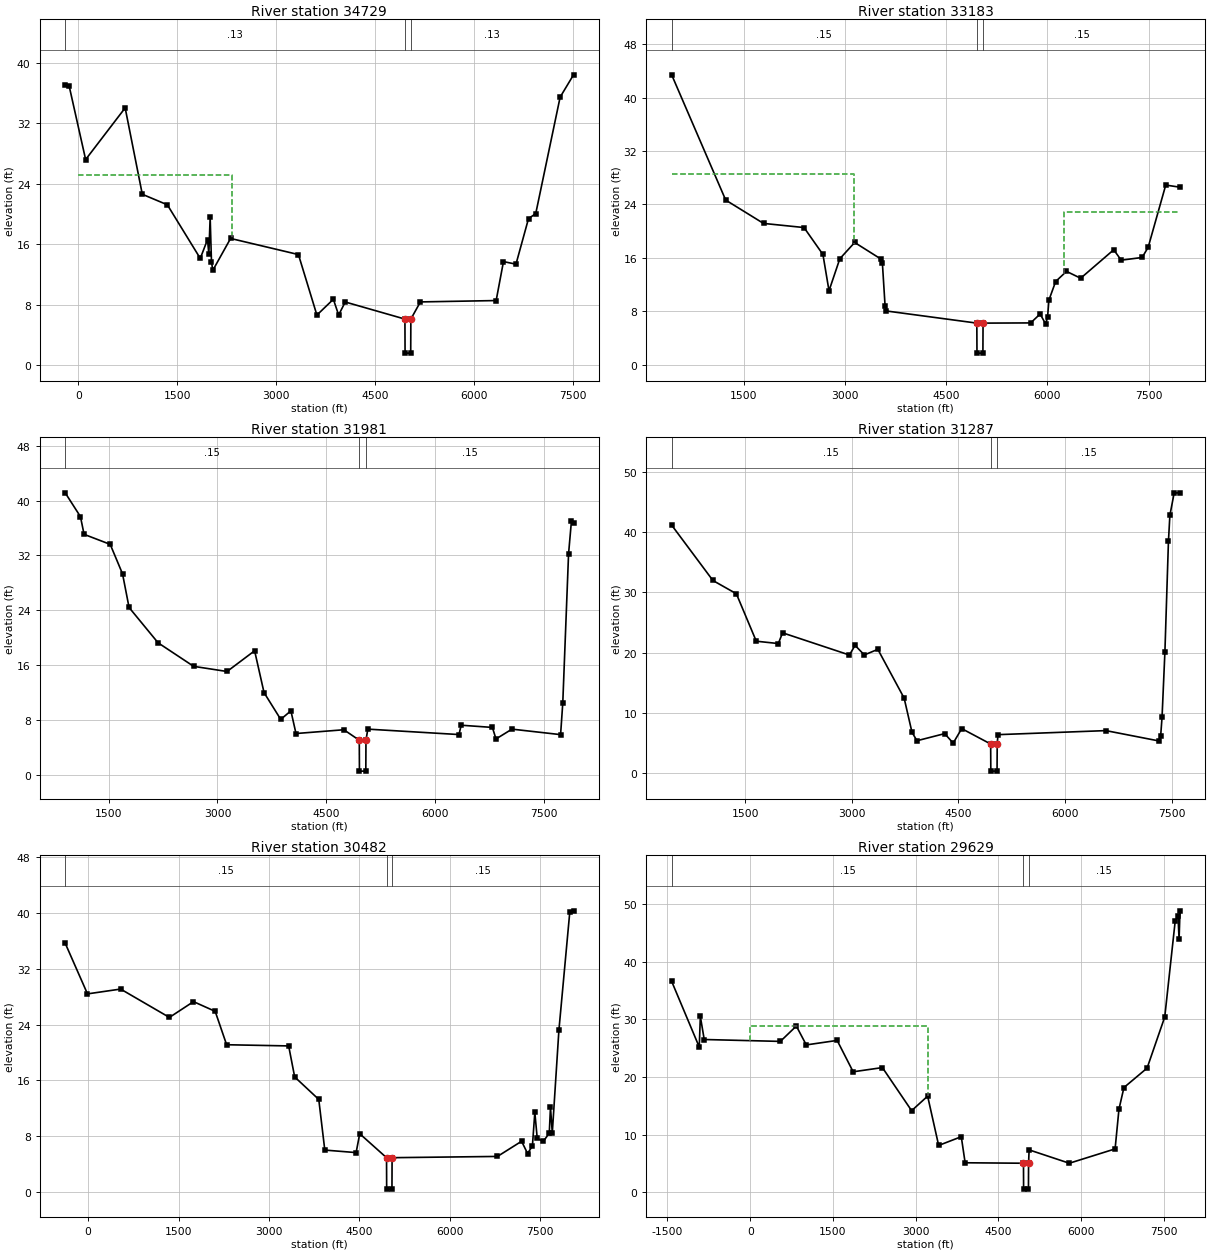
Type RM Length L Ch R = 1 ,34729   ,1546,1546,1546
BEGIN DESCRIPTION:
Black Mingo Creek 66.0
END DESCRIPTION:
XS GIS Cut Line= 4
      2459096.87       674137.66      2455594.37       670306.79
      2454459.78       669484.77      2453458.24       668975.79
#Sta/Elev= 30
  -201.1   37.08  -141.1    36.9   108.9   27.18   708.9   34.01   968.9   22.59
  1348.9    21.2  1848.9   14.11  1958.9    16.6  1978.9   14.69  1998.9   19.55
  2018.9   13.67  2038.9   12.53  2308.9   16.75  3338.9   14.62  3618.9    6.62
  3868.9    8.71  3948.9    6.63  4048.9    8.35    4955    6.09  4957.2    1.59
  5042.8    1.59    5045    6.09  5189.6    8.36  6339.6    8.54  6450.6   13.69
  6640.6   13.35  6830.6   19.37  6940.6   20.04  7310.6   35.43  7514.1   38.38
#Mann= 3 ,-1 , 0
  -201.1     .13       0    4955    .045       0    5045     .13       0
#XS Ineff= 2 , 0
       0    2328   25.11               0
Permanent Ineff=
       F       F
Bank Sta=4955,5045
XS Rating Curve= 0 ,0
Exp/Cntr=0.3,0.1

Type RM Length L Ch R = 1 ,33183   ,1202,1202,1202
BEGIN DESCRIPTION:
Black Mingo Creek 65.0
END DESCRIPTION:
XS GIS Cut Line= 3
      2459431.26       673907.05       2457060.2       670016.09
      2456245.52       667158.64
#Sta/Elev= 30
   434.9   43.44  1234.9   24.66  1794.9   21.16  2394.9   20.54  2674.9    16.5
  2764.9   11.06  2924.9   15.86  3144.9    18.3  3534.9   15.81  3554.9   15.28
  3594.9    8.84  3614.9    8.03  4953.9    6.21  4956.1    1.71  5043.9    1.71
  5046.1    6.21  5751.4    6.24  5891.4    7.58  5971.4    6.11  6001.4    7.08
  6021.4    9.66  6121.4   12.45  6281.4   13.97  6491.4   12.94  6981.4   17.21
  7091.4   15.65  7401.4   16.05  7491.4   17.58  7751.4   26.91  7962.7   26.59
#Mann= 3 ,-1 , 0
   434.9     .15       0  4953.9    .045       0  5046.1     .15       0
#XS Ineff= 2 , 0
       0  3129.1    28.5  6237.5       0    22.9
Permanent Ineff=
       F       F
Bank Sta=4953.9,5046.1
XS Rating Curve= 0 ,0
Exp/Cntr=0.3,0.1

Type RM Length L Ch R = 1 ,31981   ,694,694,694
BEGIN DESCRIPTION:
Black Mingo Creek 61.0
END DESCRIPTION:
XS GIS Cut Line= 3
      2459598.82       673671.55      2458121.13       669616.12
      2457149.08       667109.57
#Sta/Elev= 30
   901.6   41.12  1111.6   37.65  1161.6   35.07  1521.6   33.61  1691.6   29.31
  1781.6   24.41  2181.6   19.26  2671.6   15.83  3131.6   15.08  3511.6    18.1
  3641.6      12  3871.6     8.1  4011.6    9.35  4081.6    6.04  4741.6    6.59
  4953.9    5.06  4956.1     .56  5043.9     .56  5046.1    5.06  5071.6    6.68
  6327.9    5.89  6357.9    7.25  6787.9    6.93  6837.9    5.25  7057.9    6.68
  7727.9    5.88  7757.9   10.46  7837.9   32.24  7877.9   37.08  7906.3   36.67
#Mann= 3 ,-1 , 0
   901.6     .15       0  4953.9    .045       0  5046.1     .15       0
Bank Sta=4953.9,5046.1
XS Rating Curve= 0 ,0
Exp/Cntr=0.3,0.1

Type RM Length L Ch R = 1 ,31287   ,805,805,805
BEGIN DESCRIPTION:
Black Mingo Creek 59.0
END DESCRIPTION:
XS GIS Cut Line= 3
      2460698.87       673408.85      2458646.53       669238.49
      2457450.36       667040.51
#Sta/Elev= 30
   466.9   41.15  1046.9   31.97  1376.9   29.77  1656.9    21.9  1966.9   21.51
  2026.9   23.29  2966.9   19.61  3046.9   21.21  3176.9   19.62  3366.9   20.55
  3736.9   12.46  3846.9    6.81  3916.9    5.39  4306.9    6.57  4426.9       5
  4546.9     7.4  4953.9    4.85  4956.1     .35  5043.9     .35  5046.1    4.85
  5056.9     6.4  6574.9    7.07  7314.9    5.37  7344.9    6.11  7364.9    9.32
  7404.9   20.09  7454.9    38.5  7474.9   42.77  7534.9   46.48  7617.3   46.51
#Mann= 3 ,-1 , 0
   466.9     .15       0  4953.9    .045       0  5046.1     .15       0
Bank Sta=4953.9,5046.1
XS Rating Curve= 0 ,0
Exp/Cntr=0.3,0.1

Type RM Length L Ch R = 1 ,30482   ,853,853,853
BEGIN DESCRIPTION:
Black Mingo Creek 57.0
END DESCRIPTION:
XS GIS Cut Line= 3
       2462061.6       673408.82      2459303.27       668828.03
      2457720.24       666171.13
#Sta/Elev= 30
  -381.2   35.64   -11.2   28.39   538.8   29.08  1348.8   25.02  1748.8   27.28
  2108.8   25.89  2298.8   21.11  3328.8   20.94  3428.8    16.5  3828.8   13.28
  3928.8    6.03  4448.8    5.67  4508.8    8.37  4953.9    4.94  4956.1     .44
  5043.9     .44  5046.1    4.94    6796    5.12    7196    7.29    7296    5.54
    7376    6.63    7416   11.43    7456    7.71    7556    7.26    7656    8.46
    7676   12.17    7706    8.48    7816   23.21    7996   40.07  8058.7   40.28
#Mann= 3 ,-1 , 0
  -381.2     .15       0  4953.9    .045       0  5046.1     .15       0
Bank Sta=4953.9,5046.1
XS Rating Curve= 0 ,0
Exp/Cntr=0.3,0.1

Type RM Length L Ch R = 1 ,29629   ,790,790,790
BEGIN DESCRIPTION:
Black Mingo Creek 55.0
END DESCRIPTION:
XS GIS Cut Line= 3
      2463095.97       673425.23      2459516.71       667941.42
      2458184.74       665631.34
#Sta/Elev= 30
 -1423.8   36.61  -923.8    25.2  -903.8   30.51  -833.8   26.51   546.2   26.18
   836.2   28.85  1016.2   25.57  1576.2   26.35  1866.2    20.9  2396.2   21.63
  2926.2   14.14  3216.2   16.67  3416.2     8.1  3826.2    9.62  3896.2    5.09
  4953.9    5.01  4956.1     .51  5043.9     .51  5046.1    5.01  5056.2    7.33
  5784.7    5.01  6614.7     7.5  6684.7   14.39  6774.7   18.16  7194.7   21.54
  7514.7   30.42  7704.7   47.12  7754.7   47.99  7774.7    43.9  7791.3   48.87
#Mann= 3 ,-1 , 0
 -1423.8     .15       0  4953.9    .045       0  5046.1     .15       0
#XS Ineff= 2 , 0
       0  3214.6   28.83               0
Permanent Ineff=
       F       F
Bank Sta=4953.9,5046.1
XS Rating Curve= 0 ,0
Exp/Cntr=0.3,0.1

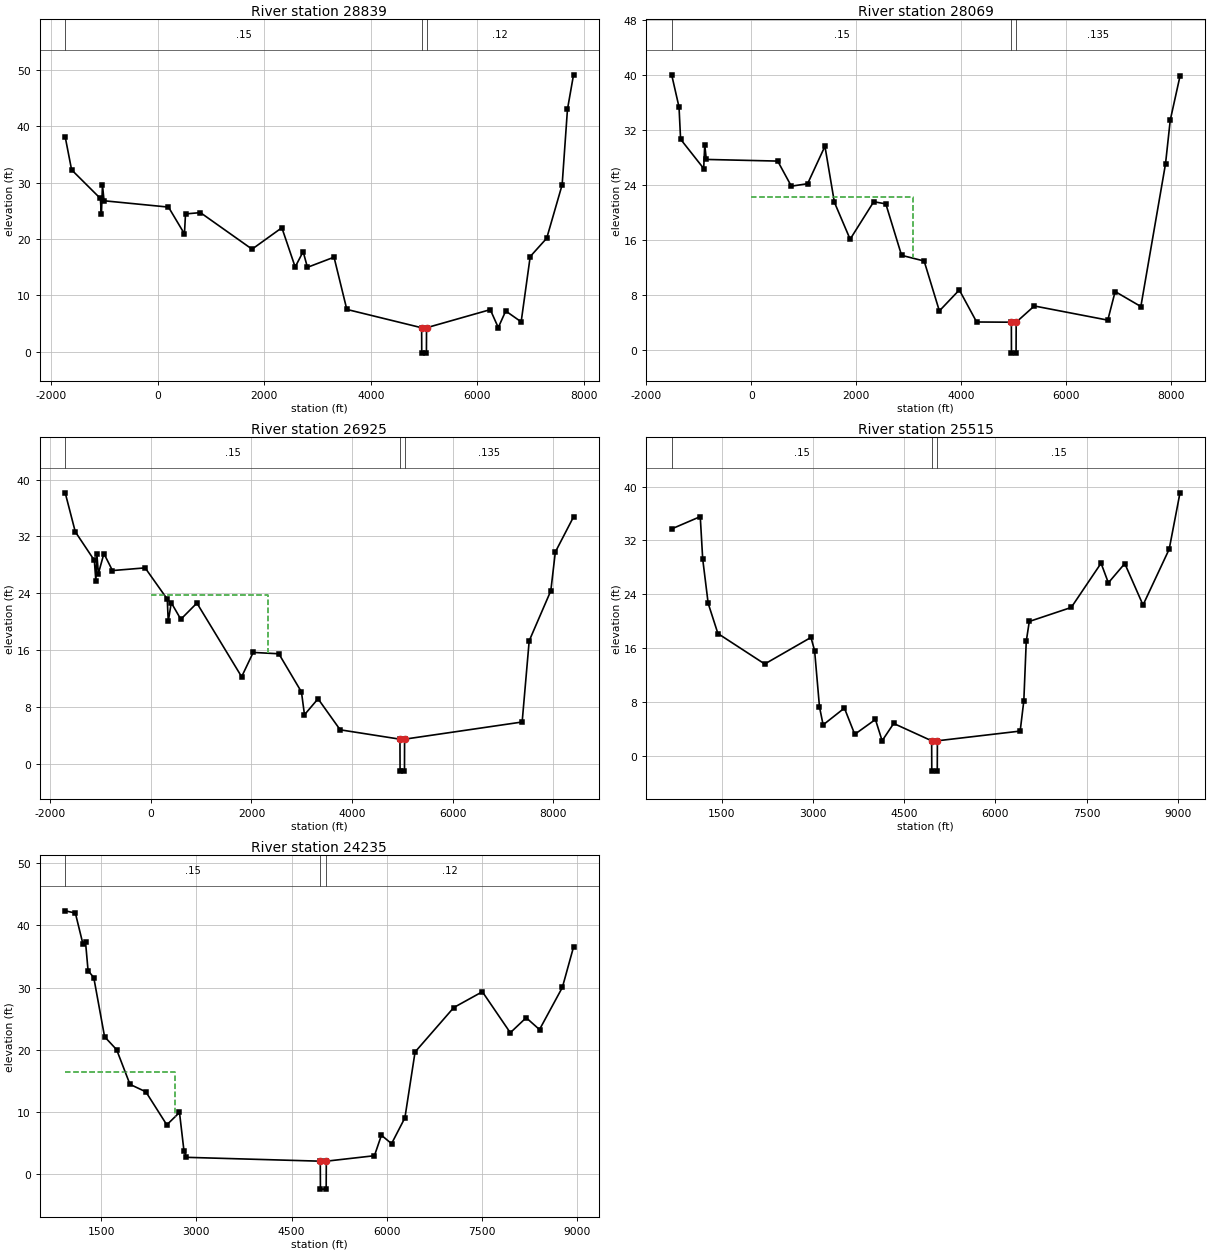
Type RM Length L Ch R = 1 ,28839   ,770,770,770
BEGIN DESCRIPTION:
Black Mingo Creek 53.0
END DESCRIPTION:
XS GIS Cut Line= 3
      2463884.07       673080.46      2460025.69       667317.52
      2458564.42       665150.24
#Sta/Elev= 30
 -1741.7   38.08 -1621.7   32.25 -1081.7   27.18 -1061.7   24.41 -1041.7   29.55
 -1011.7   26.76   198.3   25.64   498.3   20.89   518.3   24.43   798.3   24.66
  1768.3   18.18  2328.3   21.98  2578.3   15.02  2728.3   17.75  2808.3   14.96
  3308.3   16.76  3548.3     7.5  4953.9    4.25  4956.1    -.25  5043.9    -.25
  5046.1    4.25  6243.6    7.46  6393.6    4.28  6533.6    7.22  6823.6     5.3
  6993.6   16.87  7303.6   20.12  7593.6    29.6  7693.6   42.99  7807.5   49.09
#Mann= 3 ,-1 , 0
 -1741.7     .15       0  4953.9    .045       0  5046.1     .12       0
Bank Sta=4953.9,5046.1
XS Rating Curve= 0 ,0
Exp/Cntr=0.3,0.1

Type RM Length L Ch R = 1 ,28069   ,1144,1144,1144
BEGIN DESCRIPTION:
Black Mingo Creek 51.0
END DESCRIPTION:
XS GIS Cut Line= 3
      2464590.08        672489.4      2460748.11        667038.4
      2459007.71       664575.58
#Sta/Elev= 30
 -1517.5   40.07 -1377.5   35.38 -1347.5    30.7  -907.5   26.44  -887.5   29.89
  -857.5   27.76   502.5   27.52   762.5   23.87  1072.5   24.23  1402.5   29.68
  1582.5   21.53  1882.5   16.15  2332.5   21.61  2562.5   21.29  2862.5   13.81
  3292.5   12.98  3582.5    5.72  3962.5    8.77  4292.5    4.11  4953.9    4.08
  4956.1    -.42  5043.9    -.42  5046.1    4.08  5391.4    6.44  6791.4    4.38
  6931.4    8.54  7421.4    6.36  7891.4   27.13  7981.4   33.48  8167.1   39.88
#Mann= 3 ,-1 , 0
 -1517.5     .15       0  4953.9    .045       0  5046.1    .135       0
#XS Ineff= 2 , 0
       0  3071.7   22.32               0
Permanent Ineff=
       F       F
Bank Sta=4953.9,5046.1
XS Rating Curve= 0 ,0
Exp/Cntr=0.3,0.1

Type RM Length L Ch R = 1 ,26925   ,1410,1410,1410
BEGIN DESCRIPTION:
Black Mingo Creek 49.0
END DESCRIPTION:
XS GIS Cut Line= 3
      2464934.83       672243.07      2461671.47       666390.83
      2459043.33       664214.77
#Sta/Elev= 30
 -1705.6   38.14 -1505.6   32.66 -1125.6   28.62 -1095.6   25.69 -1075.6   29.49
 -1045.6   26.77  -935.6   29.59  -765.6   27.19  -115.6   27.57   324.4   23.17
   344.4   20.04   404.4   22.66   594.4   20.33   914.4   22.61  1804.4   12.23
  2034.4   15.66  2544.4   15.47  2994.4   10.09  3054.4    6.88  3324.4    9.13
  3764.4    4.76  4953.9    3.44  4956.1   -1.06  5043.9   -1.06  5046.1    3.44
    7385    5.86    7525   17.29    7955   24.34    8045    29.8  8407.1   34.75
#Mann= 3 ,-1 , 0
 -1705.6     .15       0  4953.9    .045       0  5046.1    .135       0
#XS Ineff= 2 , 0
       0  2336.4   23.81               0
Permanent Ineff=
       F       F
Bank Sta=4953.9,5046.1
XS Rating Curve= 0 ,0
Exp/Cntr=0.3,0.1

Type RM Length L Ch R = 1 ,25515   ,1280,1280,1280
BEGIN DESCRIPTION:
Black Mingo Creek 47.0
END DESCRIPTION:
XS GIS Cut Line= 3
      2465257.05       669287.73      2462860.78       665681.62
      2460536.72       662391.93
#Sta/Elev= 30
   678.5   33.72  1148.5   35.54  1188.5   29.26  1278.5   22.68  1438.5    18.2
  2208.5   13.68  2968.5   17.62  3028.5   15.66  3108.5    7.33  3168.5    4.65
  3518.5    7.14  3688.5    3.25  4028.5    5.45  4138.5    2.29  4328.5    4.86
  4952.7    2.29    4955   -2.21    5045   -2.21  5047.3    2.29  6408.2    3.73
  6468.2    8.21  6508.2   17.04  6558.2   19.99  7248.2   22.07  7738.2   28.63
  7858.2   25.72  8128.2   28.58  8428.2   22.43  8858.2   30.71    9036   39.07
#Mann= 3 ,-1 , 0
   678.5     .15       0  4952.7    .045       0  5047.3     .15       0
Bank Sta=4952.7,5047.3
XS Rating Curve= 0 ,0
Exp/Cntr=0.3,0.1

Type RM Length L Ch R = 1 ,24235   ,788,788,788
BEGIN DESCRIPTION:
Black Mingo Creek 45.0
END DESCRIPTION:
XS GIS Cut Line= 3
      2465749.62       668384.72       2463770.9       664827.76
      2461668.55       661500.38
#Sta/Elev= 30
     935   42.36    1095      42    1215   36.98    1255   37.34    1295   32.73
    1385   31.61    1555   22.09    1745      20    1955   14.42    2205   13.22
    2535     7.9    2735    9.89    2805    3.75    2845    2.67  4952.5    2.05
  4954.8   -2.45  5045.2   -2.45  5047.5    2.05  5805.3    2.93  5915.3    6.23
  6075.3    4.87  6285.3    9.03  6445.3   19.63  7055.3   26.79  7505.3   29.33
  7945.3   22.73  8195.3   25.15  8405.3   23.24  8765.3   30.03  8941.2   36.53
#Mann= 3 ,-1 , 0
     935     .15       0  4952.5    .045       0  5047.5     .12       0
#XS Ineff= 2 , 0
       0  2662.8   16.47               0
Permanent Ineff=
       F       F
Bank Sta=4952.5,5047.5
XS Rating Curve= 0 ,0
Exp/Cntr=0.3,0.1