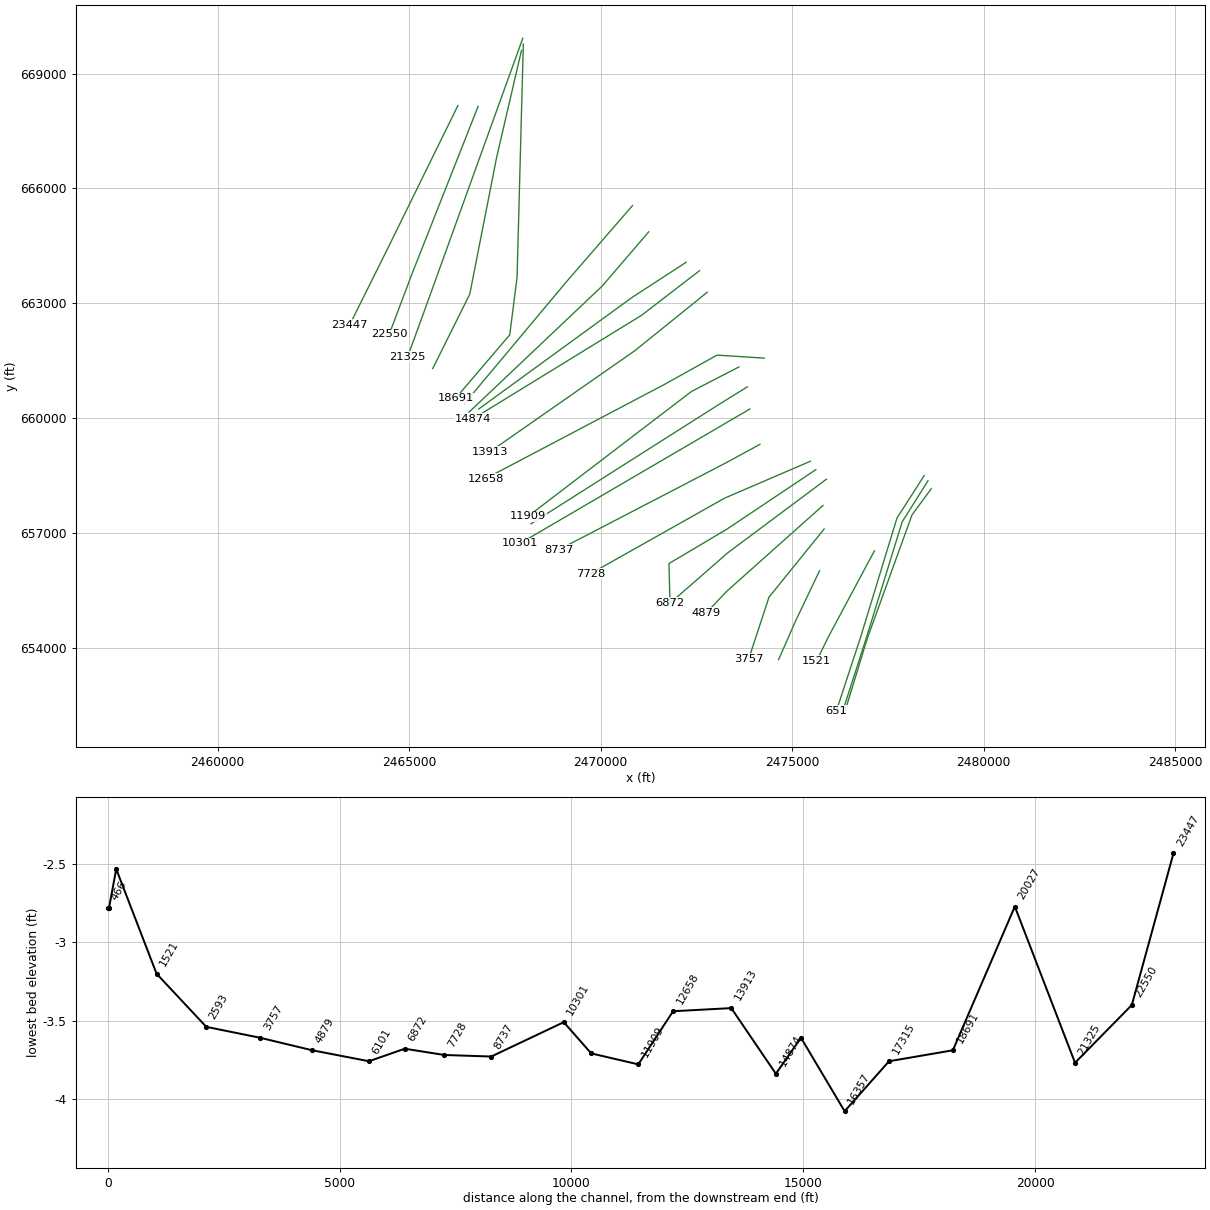
HEC-RAS study Black Mingo Creek.prj: Black Mingo Creek Limited Detail Study

--- Black Mingo Creek.g04 (geometry) --- (continued)

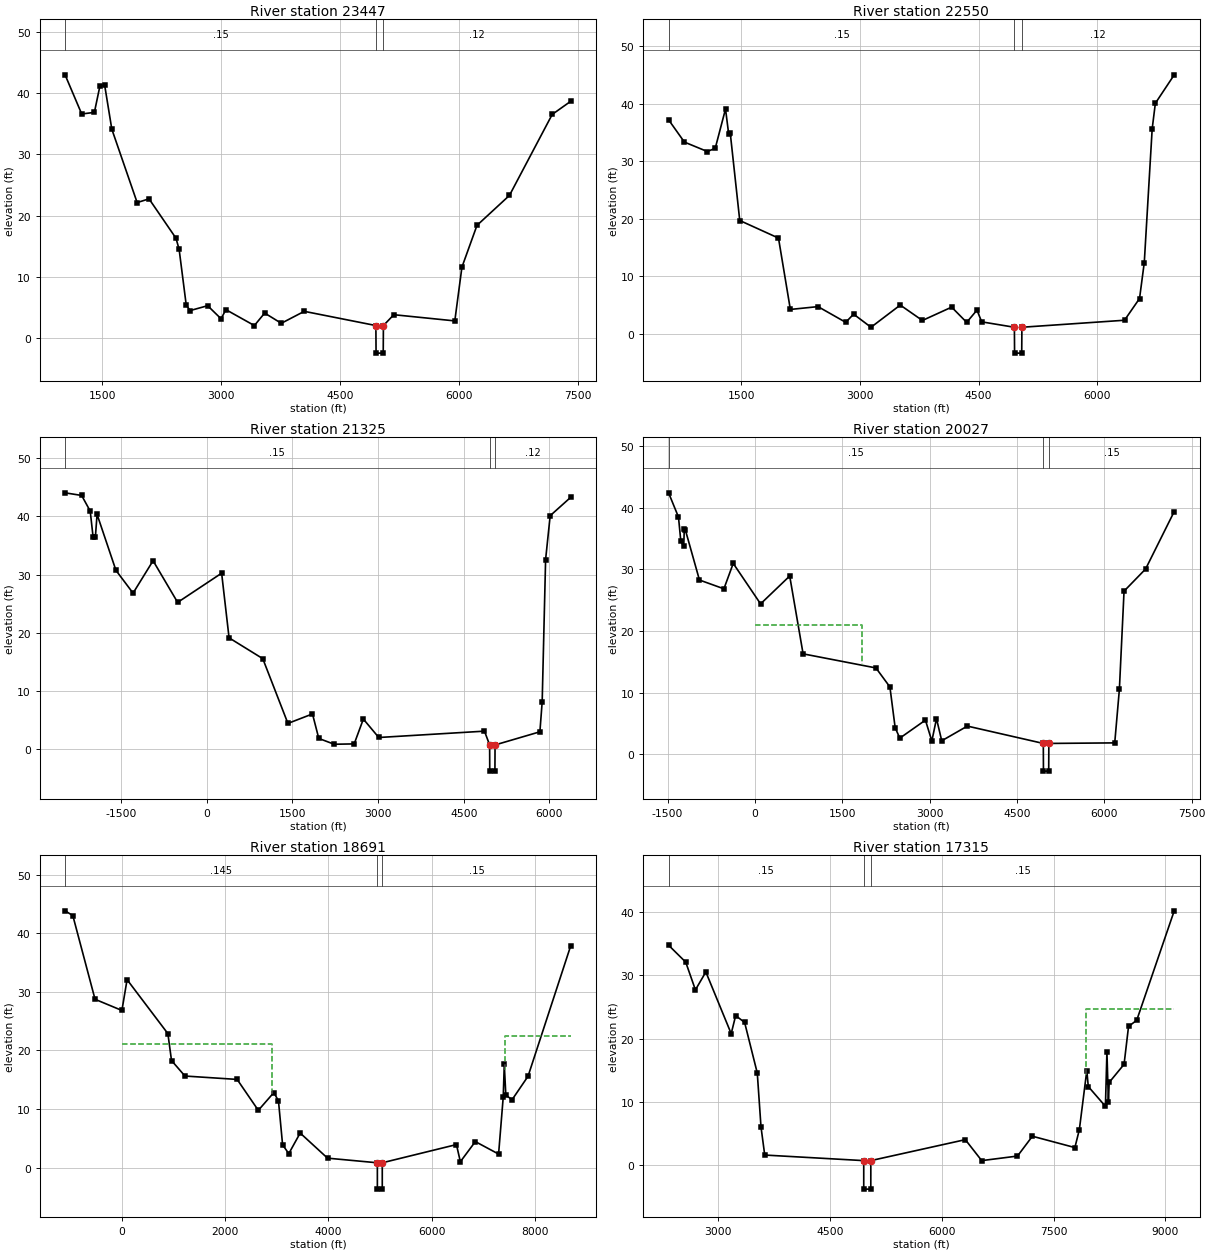
Type RM Length L Ch R = 1 ,23447   ,897,897,897
BEGIN DESCRIPTION:
Black Mingo Creek 43.0
END DESCRIPTION:
XS GIS Cut Line= 3
      2466271.88       668166.54      2464465.25       664485.39
      2463448.51       662440.71
#Sta/Elev= 30
  1028.3   42.99  1238.3    36.6  1398.3   36.86  1468.3   41.17  1528.3   41.29
  1618.3   34.13  1938.3   22.14  2088.3   22.75  2428.3   16.33  2468.3   14.51
  2558.3    5.38  2608.3    4.52  2828.3    5.31  2998.3    3.17  3058.3    4.67
  3418.3    2.07  3548.3    4.11  3758.3    2.44  4048.3    4.39  4952.5    2.07
  4954.8   -2.43  5045.2   -2.43  5047.5    2.07  5178.9    3.84  5948.9    2.83
  6038.9    11.6  6228.9   18.42  6638.9   23.31  7178.9   36.53  7412.4   38.67
#Mann= 3 ,-1 , 0
  1028.3     .15       0  4952.5    .045       0  5047.5     .12       0
Bank Sta=4952.5,5047.5
XS Rating Curve= 0 ,0
Exp/Cntr=0.3,0.1

Type RM Length L Ch R = 1 ,22550   ,1225,1225,1225
BEGIN DESCRIPTION:
Black Mingo Creek 41.0
END DESCRIPTION:
XS GIS Cut Line= 3
      2466799.59       668144.67      2465072.36       663766.99
      2464477.17       662186.66
#Sta/Elev= 30
   579.1   37.19   779.1   33.31  1069.1   31.67  1169.1   32.23  1299.1   39.07
  1339.1   34.73  1359.1   34.87  1479.1   19.67  1969.1   16.61  2119.1     4.2
  2469.1    4.69  2819.1    1.96  2919.1    3.38  3139.1     1.1  3509.1    4.96
  3789.1    2.28  4159.1     4.6  4349.1    1.95  4479.1    4.08  4539.1    2.04
  4952.5     1.1  4954.8    -3.4  5045.2    -3.4  5047.5     1.1  6345.2    2.32
  6535.2     6.1  6595.2   12.36  6695.2   35.63  6735.2   40.06  6973.9   45.01
#Mann= 3 ,-1 , 0
   579.1     .15       0  4952.5    .045       0  5047.5     .12       0
Bank Sta=4952.5,5047.5
XS Rating Curve= 0 ,0
Exp/Cntr=0.3,0.1

Type RM Length L Ch R = 1 ,21325   ,1298,1298,1298
BEGIN DESCRIPTION:
Black Mingo Creek 39.0
END DESCRIPTION:
XS GIS Cut Line= 3
      2467966.15         669924.      2465441.77       662925.54
      2464959.82       661601.13
#Sta/Elev= 30
 -2477.6   44.06 -2187.6   43.61 -2037.6   40.92 -1987.6    36.5 -1947.6   36.41
 -1917.6   40.36 -1587.6   30.74 -1287.6   26.82  -937.6   32.39  -507.6   25.23
   262.4   30.25   392.4   19.14   982.4   15.56  1422.4    4.43  1852.4    6.06
  1962.4    1.85  2232.4     .85  2582.4     .91  2742.4    5.18  3012.4    2.01
  4862.4     3.1  4952.5     .73  4954.8   -3.77  5045.2   -3.77  5047.5     .73
  5832.2    2.99  5872.2    8.13  5932.2    32.6  6012.2   40.13  6371.6   43.29
#Mann= 3 ,-1 , 0
 -2477.6     .15       0  4952.5    .045       0  5047.5     .12       0
Bank Sta=4952.5,5047.5
XS Rating Curve= 0 ,0
Exp/Cntr=0.3,0.1

Type RM Length L Ch R = 1 ,20027   ,1336,1336,1336
BEGIN DESCRIPTION:
Black Mingo Creek 37.0
END DESCRIPTION:
XS GIS Cut Line= 4
      2467932.41       669607.05      2467281.12       666800.76
      2466581.95       663237.86      2465614.58       661293.55
#Sta/Elev= 30
 -1482.7   42.46 -1312.7   38.52 -1272.7    34.6 -1222.7   33.76 -1212.7   36.65
 -1192.7   36.37  -952.7   28.29  -532.7   26.86  -372.7   30.99    97.3   24.41
   597.3   28.94   827.3   16.29  2078.2      14  2318.2   10.91  2408.2    4.29
  2488.2    2.59  2928.2    5.52  3038.2    2.12  3118.2    5.76  3208.2    2.16
  3648.2    4.55  4952.5    1.73  4954.8   -2.77  5045.2   -2.77  5047.5    1.73
    6179    1.82    6259   10.53    6339   26.48    6709   30.08  7200.7   39.42
#Mann= 3 ,-1 , 0
 -1482.7     .15       0  4952.5     .04       0  5047.5     .15       0
#XS Ineff= 2 , 0
       0  1842.9   21.03               0
Permanent Ineff=
       F       F
Bank Sta=4952.5,5047.5
XS Rating Curve= 0 ,0
Exp/Cntr=0.3,0.1

Type RM Length L Ch R = 1 ,18691   ,1376,1376,1376
BEGIN DESCRIPTION:
Black Mingo Creek 35.0
END DESCRIPTION:
XS GIS Cut Line= 4
       2467980.9       669773.39      2467817.47       663678.43
      2467625.92       662174.74      2466215.87       660521.08
#Sta/Elev= 30
 -1092.1   43.85  -942.1   43.04  -512.1   28.74     7.9   26.83   107.9   32.09
   897.9   22.87   967.9   18.28  1227.9   15.63  2237.9   15.05  2647.9    9.77
  2947.9    12.8  3037.9    11.4  3117.9    3.87  3237.9    2.38  3457.9    5.89
  3987.9     1.6    4952     .81  4952.1   -3.69  5046.9   -3.69    5047     .81
  6482.4    3.92  6558.2     .99  6848.2    4.43  7298.2     2.3  7388.2   12.06
  7408.2    17.6  7438.2   12.39  7558.2   11.57  7868.2   15.59  8694.1   37.88
#Mann= 3 ,-1 , 0
 -1092.1    .145       0    4952     .04       0    5047     .15       0
#XS Ineff= 2 , 0
       0    2908   21.16  7413.9       0    22.5
Permanent Ineff=
       F       F
Bank Sta=4952,5047
XS Rating Curve= 0 ,0
Exp/Cntr=0.3,0.1

Type RM Length L Ch R = 1 ,17315   ,958,958,958
BEGIN DESCRIPTION:
Black Mingo Creek 33.0
END DESCRIPTION:
XS GIS Cut Line= 3
      2470834.42       665555.64       2469091.3       663544.34
      2466447.43       660380.68
#Sta/Elev= 30
  2333.5   34.74  2563.5   32.07  2693.5   27.69  2833.5   30.52  3173.5   20.78
  3233.5   23.63  3353.5   22.56  3523.5   14.57  3573.5    6.06  3623.5    1.62
    4952     .74  4952.1   -3.76  5046.9   -3.76    5047     .74    6315    4.05
    6535     .74    7015    1.46    7215    4.59    7785     2.8    7845    5.63
    7945   14.96    7965   12.43    8195    9.31    8215   17.94    8235    9.93
    8245   13.08    8445   15.94    8505   21.92    8615    22.9    9118   40.17
#Mann= 3 ,-1 , 0
  2333.5     .15       0    4952     .04       0    5047     .15       0
#XS Ineff= 2 , 0
       0                  7937.4       0   24.66
Permanent Ineff=
       F       F
Bank Sta=4952,5047
XS Rating Curve= 0 ,0
Exp/Cntr=0.3,0.1

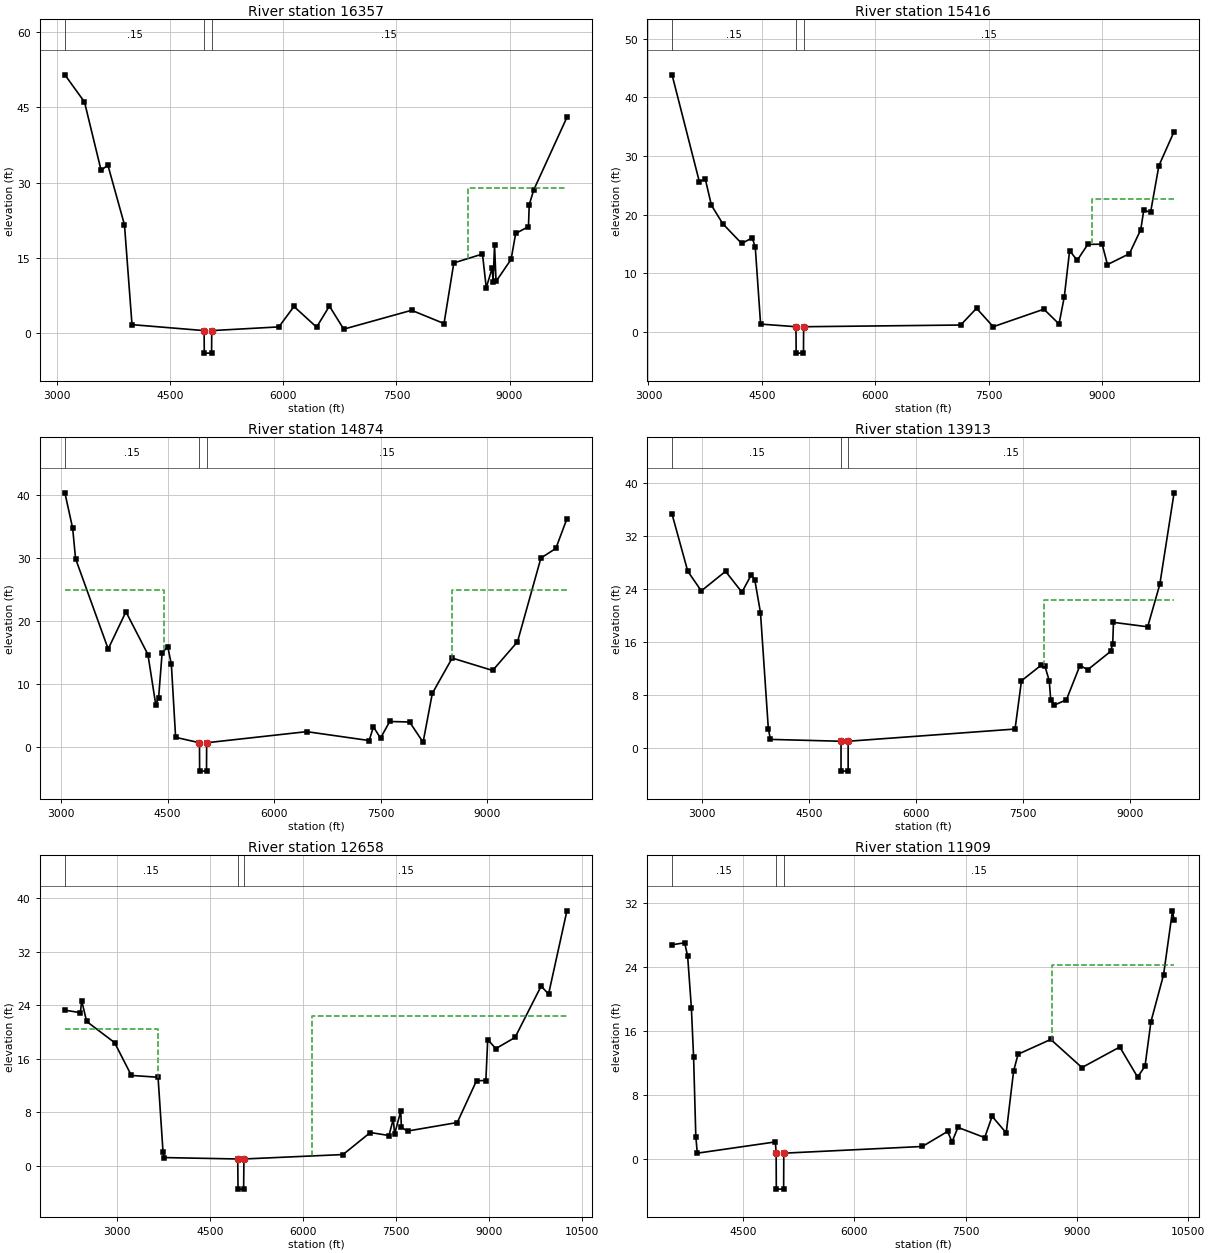
Type RM Length L Ch R = 1 ,16357   ,941,941,941
BEGIN DESCRIPTION:
Black Mingo Creek 29.0
END DESCRIPTION:
XS GIS Cut Line= 3
      2471255.87       664866.08      2470039.49       663448.57
       2466562.8       660153.85
#Sta/Elev= 30
    3103   51.52    3363   46.09    3583   32.44    3673   33.49    3893   21.56
    3993    1.61  4949.4     .42  4951.6   -4.08  5048.4   -4.08  5050.6     .42
  5940.9    1.16  6140.9    5.24  6440.9    1.11  6610.9    5.32  6800.9     .71
  7700.9    4.48  8130.9    1.83  8260.9   13.94  8640.9   15.72  8690.9    8.99
  8770.9   12.96  8780.9    10.1  8800.9   17.43  8820.9   10.25  9020.9   14.66
  9080.9   19.82  9250.9    21.2  9260.9   25.56  9320.9   28.53  9760.7   43.02
#Mann= 3 ,-1 , 0
    3103     .15       0  4949.4     .04       0  5050.6     .15       0
#XS Ineff= 2 , 0
       0                  8445.6       0   28.87
Permanent Ineff=
       F       F
Bank Sta=4949.4,5050.6
XS Rating Curve= 0 ,0
Exp/Cntr=0.3,0.1

Type RM Length L Ch R = 1 ,15416   ,542,542,542
BEGIN DESCRIPTION:
Black Mingo Creek 28.0
END DESCRIPTION:
XS GIS Cut Line= 3
      2472230.83       664069.55      2470818.87        663151.3
      2466816.83       660236.99
#Sta/Elev= 30
  3311.7   43.83  3671.7   25.64  3751.7   26.02  3831.7    21.6  3981.7   18.45
  4231.7   15.08  4371.7   16.04  4411.7   14.41  4481.7    1.34  4949.4     .89
  4951.6   -3.61  5048.4   -3.61  5050.6     .89    7126    1.18    7336    4.03
    7556     .89    8226    3.88    8426    1.36    8496    6.02    8566   13.87
    8666    12.2    8806   14.93    8996   14.96    9066   11.48    9356   13.34
    9506   17.43    9546   20.76    9636    20.4    9746   28.34  9946.7   34.16
#Mann= 3 ,-1 , 0
  3311.7     .15       0  4949.4     .04       0  5050.6     .15       0
#XS Ineff= 2 , 0
       0                  8857.7       0    22.7
Permanent Ineff=
       F       F
Bank Sta=4949.4,5050.6
XS Rating Curve= 0 ,0
Exp/Cntr=0.3,0.1

Type RM Length L Ch R = 1 ,14874   ,961,961,961
BEGIN DESCRIPTION:
Black Mingo Creek 27.0
END DESCRIPTION:
XS GIS Cut Line= 3
       2472583.5       663851.27      2471064.31       662682.35
      2466671.04       659982.69
#Sta/Elev= 30
  3053.1   40.29  3163.1   34.64  3203.1   29.86  3663.1   15.53  3913.1   21.43
  4223.1   14.65  4333.1    6.71  4373.1    7.73  4423.1   14.92  4503.1   15.87
  4553.1   13.09  4613.1    1.52  4949.4     .66  4951.6   -3.84  5048.4   -3.84
  5050.6     .66    6460    2.42    7340    1.01    7400    3.18    7500    1.39
    7630    4.03    7910    3.95    8100     .74    8230    8.49    8510   14.09
    9080   12.12    9430   16.67    9760   29.95    9970   31.47 10126.4   36.17
#Mann= 3 ,-1 , 0
  3053.1     .15       0  4949.4     .04       0  5050.6     .15       0
#XS Ineff= 2 , 0
       0  4449.5   24.93  8505.3       0   24.82
Permanent Ineff=
       F       F
Bank Sta=4949.4,5050.6
XS Rating Curve= 0 ,0
Exp/Cntr=0.3,0.1

Type RM Length L Ch R = 1 ,13913   ,1255,1255,1255
BEGIN DESCRIPTION:
Black Mingo Creek 25.0
END DESCRIPTION:
XS GIS Cut Line= 3
      2472784.36       663288.14       2470895.4       661761.92
      2467113.45       659122.66
#Sta/Elev= 30
  2580.6   35.28  2800.6   26.69  2990.6   23.73  3330.6   26.67  3560.6   23.53
  3690.6   26.13  3740.6    25.4  3820.6   20.44  3930.6    2.97  3960.6    1.36
    4950    1.08  4950.1   -3.42  5049.9   -3.42    5050    1.08  7390.6    2.92
  7480.6   10.19  7760.6   12.57  7810.6   12.35  7870.6   10.17  7890.6    7.36
  7940.6    6.52  8110.6    7.32  8300.6   12.49  8410.6   11.86  8730.6   14.61
  8760.6   15.75  8770.6   18.99  9250.6   18.32  9420.6   24.71  9620.9    38.5
#Mann= 3 ,-1 , 0
  2580.6     .15       0    4950     .04       0    5050     .15       0
#XS Ineff= 2 , 0
       0                  7795.6       0   22.43
Permanent Ineff=
       F       F
Bank Sta=4950,5050
XS Rating Curve= 0 ,0
Exp/Cntr=0.3,0.1

Type RM Length L Ch R = 1 ,12658   ,749,749,749
BEGIN DESCRIPTION:
Black Mingo Creek 22.0
END DESCRIPTION:
XS GIS Cut Line= 4
      2474271.67        661565.9      2473040.38       661644.64
      2471644.55        660867.1      2466998.93       658418.75
#Sta/Elev= 30
  2167.3   23.27  2417.3    22.9  2437.3    24.7  2517.3   21.59  2967.3   18.43
  3237.3   13.53  3667.3   13.26  3747.3    2.11  3767.3    1.27    4950    1.06
    4955   -3.44    5045   -3.44    5050    1.06    6645    1.72    7085    5.01
    7385    4.56    7455    7.04    7475    4.77    7575    8.19    7585    5.76
    7685    5.23    8485     6.5    8795   12.75    8945   12.76    8975   18.89
    9105   17.53    9415    19.2    9835   26.86    9955   25.68 10250.2    38.1
#Mann= 3 ,-1 , 0
  2167.3     .15       0    4950     .04       0    5050     .15       0
#XS Ineff= 2 , 0
       0  3668.4   20.51    6150       0   22.47
Permanent Ineff=
       F       F
Bank Sta=4950,5050
XS Rating Curve= 0 ,0
Exp/Cntr=0.3,0.1

Type RM Length L Ch R = 1 ,11909   ,1016,1016,1016
BEGIN DESCRIPTION:
Black Mingo Creek 21.0
END DESCRIPTION:
XS GIS Cut Line= 3
      2473611.07       661335.32      2472374.36       660696.25
      2468106.92       657433.51
#Sta/Elev= 30
  3546.2   26.81  3716.2   27.06  3756.2   25.37  3806.2   18.95  3836.2   12.76
  3866.2     2.8  3886.2     .72  4938.3    2.13  4948.4     .72  4950.6   -3.78
  5049.4   -3.78  5051.6     .72  6918.3    1.56  7258.3    3.44  7318.3    2.14
  7398.3    3.95  7758.3    2.67  7858.3    5.33  8048.3    3.26  8148.3   11.03
  8208.3   13.11  8648.3   14.96  9068.3   11.44  9578.3   14.01  9818.3   10.25
  9918.3   11.61  9998.3   17.18 10168.3   23.05 10288.3   31.06 10310.1   29.88
#Mann= 3 ,-1 , 0
  3546.2     .15       0  4948.4     .04       0  5051.6     .15       0
#XS Ineff= 2 , 0
       0                  8670.8       0   24.29
Permanent Ineff=
       F       F
Bank Sta=4948.4,5051.6
XS Rating Curve= 0 ,0
Exp/Cntr=0.3,0.1

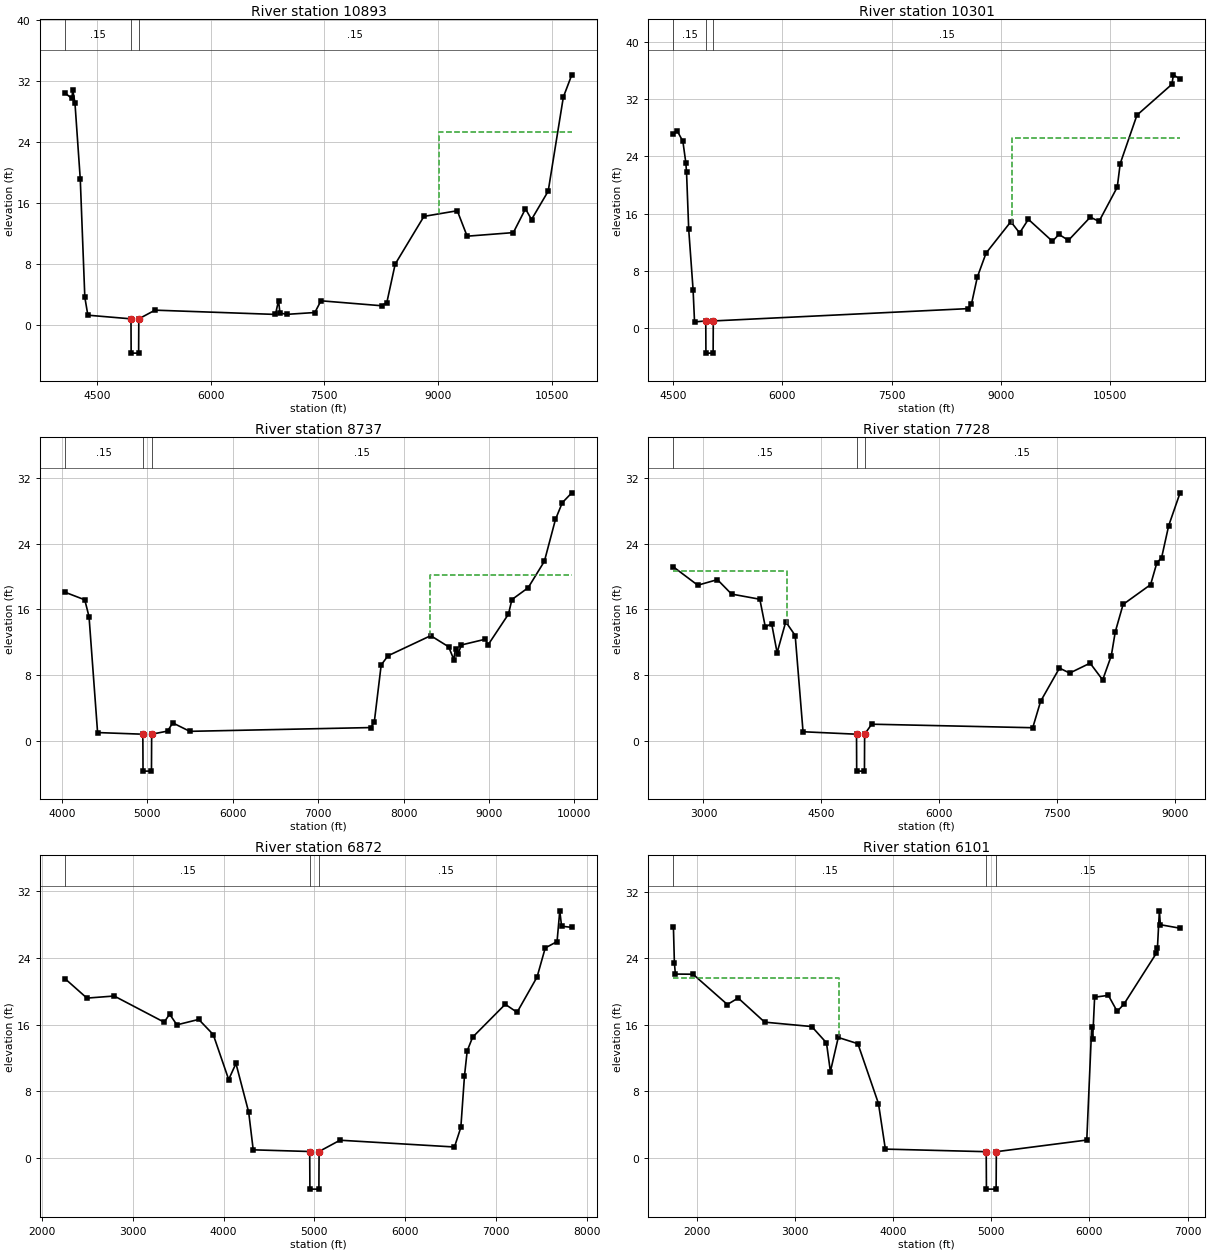
Type RM Length L Ch R = 1 ,10893   ,592,592,592
BEGIN DESCRIPTION:
Black Mingo Creek 19.0
END DESCRIPTION:
XS GIS Cut Line= 3
      2473829.56       660815.06      2473059.62       660336.45
      2468179.74        657235.8
#Sta/Elev= 30
  4079.1   30.41  4169.1   29.72  4179.1   30.89  4209.1    29.1  4279.1   19.11
  4339.1    3.63  4379.1    1.27  4948.4     .79  4950.6   -3.71  5049.4   -3.71
  5051.6     .79  5265.7    1.93  6855.7    1.37  6895.7    3.18  6915.7    1.55
  7005.7    1.38  7375.7    1.62  7455.7    3.16  8255.7    2.51  8325.7    2.93
  8435.7    7.97  8815.7   14.24  9255.7   14.98  9385.7   11.64  9995.7   12.11
 10155.7   15.23 10235.7   13.83 10455.7   17.55 10655.7    29.9 10767.3   32.82
#Mann= 3 ,-1 , 0
  4079.1     .15       0  4948.4     .04       0  5051.6     .15       0
#XS Ineff= 2 , 0
       0                    9012       0   25.26
Permanent Ineff=
       F       F
Bank Sta=4948.4,5051.6
XS Rating Curve= 0 ,0
Exp/Cntr=0.3,0.1

Type RM Length L Ch R = 1 ,10301   ,1564,1564,1564
BEGIN DESCRIPTION:
Black Mingo Creek 17.0
END DESCRIPTION:
XS GIS Cut Line= 2
      2473898.76       660237.25      2467898.79       656725.95
#Sta/Elev= 30
  4504.4   27.09  4554.4    27.6  4634.4    26.1  4674.4   23.13  4684.4   21.81
  4714.4   13.79  4774.4    5.36  4794.4     .85  4948.4     .99  4950.6   -3.51
  5049.4   -3.51  5051.6     .99  8544.4    2.71  8594.4    3.37  8674.4    7.12
  8794.4   10.48  9134.4   14.87  9254.4   13.29  9374.4    15.2  9704.4   12.13
  9794.4   13.09  9924.4   12.26 10224.4    15.5 10344.4   14.91 10594.4    19.7
 10634.4   22.97 10864.4   29.76 11344.4   34.08 11364.4    35.4 11456.3   34.79
#Mann= 3 ,-1 , 0
  4504.4     .15       0  4948.4     .04       0  5051.6     .15       0
#XS Ineff= 2 , 0
       0                  9155.9       0   26.54
Permanent Ineff=
       F       F
Bank Sta=4948.4,5051.6
XS Rating Curve= 0 ,0
Exp/Cntr=0.3,0.1

Type RM Length L Ch R = 1 ,8737    ,1009,1009,1009
BEGIN DESCRIPTION:
Black Mingo Creek 15.0
END DESCRIPTION:
XS GIS Cut Line= 3
      2474160.69       659312.21      2473256.34       658820.65
      2468908.04       656559.46
#Sta/Elev= 30
  4038.8   18.07  4268.8   17.15  4318.8   15.08  4418.8     .97  4948.4     .77
  4950.6   -3.73  5049.4   -3.73  5051.6     .77  5238.1    1.15  5298.1    2.15
  5498.1    1.12  7618.1    1.58  7658.1    2.31  7738.1    9.21  7818.1   10.33
  8318.1   12.78  8528.1   11.42  8588.1    9.87  8608.1    11.2  8638.1    10.6
  8678.1   11.65  8958.1   12.35  8988.1   11.64  9228.1   15.41  9268.1   17.18
  9458.1   18.62  9648.1   21.84  9778.1   26.95  9858.1   28.99  9969.2   30.19
#Mann= 3 ,-1 , 0
  4038.8     .15       0  4948.4     .04       0  5051.6     .15       0
#XS Ineff= 2 , 0
       0                  8312.7       0   20.15
Permanent Ineff=
       F       F
Bank Sta=4948.4,5051.6
XS Rating Curve= 0 ,0
Exp/Cntr=0.3,0.1

Type RM Length L Ch R = 1 ,7728    ,856,856,856
BEGIN DESCRIPTION:
Black Mingo Creek 13.0
END DESCRIPTION:
XS GIS Cut Line= 3
      2475473.52       658869.35      2473238.39        657906.8
      2469740.46       655935.18
#Sta/Elev= 30
  2617.8   21.17  2927.8   18.94  3177.8   19.62  3357.8   17.86  3717.8   17.23
  3787.8   13.84  3867.8   14.27  3937.8   10.71  4047.8   14.48  4167.8   12.81
  4267.8    1.08  4948.4     .78  4950.6   -3.72  5049.4   -3.72  5051.6     .78
  5141.4       2  7191.4    1.57  7291.4    4.79  7531.4    8.84  7661.4    8.23
  7921.4    9.44  8081.4     7.4  8191.4   10.35  8241.4   13.24  8341.4    16.6
  8691.4   19.01  8771.4   21.68  8831.4   22.29  8921.4   26.19  9066.7    30.2
#Mann= 3 ,-1 , 0
  2617.8     .15       0  4948.4     .04       0  5051.6     .15       0
#XS Ineff= 2 , 0
       0  4063.4   20.65               0
Permanent Ineff=
       F       F
Bank Sta=4948.4,5051.6
XS Rating Curve= 0 ,0
Exp/Cntr=0.3,0.1

Type RM Length L Ch R = 1 ,6872    ,771,771,771
BEGIN DESCRIPTION:
Black Mingo Creek 11.0
END DESCRIPTION:
XS GIS Cut Line= 4
      2475619.25       658650.88      2473305.56       657100.77
      2471784.67       656197.55      2471811.03       655175.62
#Sta/Elev= 30
  2256.7   21.48  2496.7   19.17  2796.7   19.42  3346.7   16.29  3406.7   17.25
  3486.7   15.97  3726.7   16.62  3886.7   14.81  4056.7    9.43  4136.7   11.35
  4276.7    5.53  4326.7    1.02  4948.4     .82  4950.6   -3.68  5049.4   -3.68
  5051.6     .82  5281.7    2.17  6541.7    1.36  6611.7    3.71  6651.7    9.86
  6681.7   12.86  6741.7    14.5  7100.5   18.43  7230.5   17.47  7450.5   21.69
  7540.5   25.17  7670.5   25.93  7700.5   29.61  7720.5   27.77  7832.8   27.63
#Mann= 3 ,-1 , 0
  2256.7     .15       0  4948.4     .04       0  5051.6     .15       0
Bank Sta=4948.4,5051.6
XS Rating Curve= 0 ,0
Exp/Cntr=0.3,0.1

Type RM Length L Ch R = 1 ,6101    ,1222,1222,1222
BEGIN DESCRIPTION:
Black Mingo Creek 9.0
END DESCRIPTION:
XS GIS Cut Line= 3
      2475896.74       658401.53      2473322.35       656479.46
      2471852.65       655196.44
#Sta/Elev= 30
  1760.5   27.79  1770.5   23.46  1780.5   22.09  1960.5   22.07  2310.5   18.43
  2420.5   19.21  2690.5   16.31  3170.5   15.78  3320.5   13.82  3360.5   10.37
  3440.5   14.47  3640.5   13.72  3850.5    6.52  3920.5    1.05  4948.4     .74
  4950.6   -3.76  5049.4   -3.76  5051.6     .74  5973.3    2.14  6023.3    15.7
  6033.3   14.27  6053.3   19.31  6193.3   19.53  6283.3    17.6  6353.3    18.5
  6683.3   24.61  6693.3    25.2  6713.3   29.69  6723.3   28.02  6924.2    27.6
#Mann= 3 ,-1 , 0
  1760.5     .15       0  4948.4     .04       0  5051.6     .15       0
#XS Ineff= 2 , 0
       0  3453.2   21.62               0
Permanent Ineff=
       F       F
Bank Sta=4948.4,5051.6
XS Rating Curve= 0 ,0
Exp/Cntr=0.3,0.1

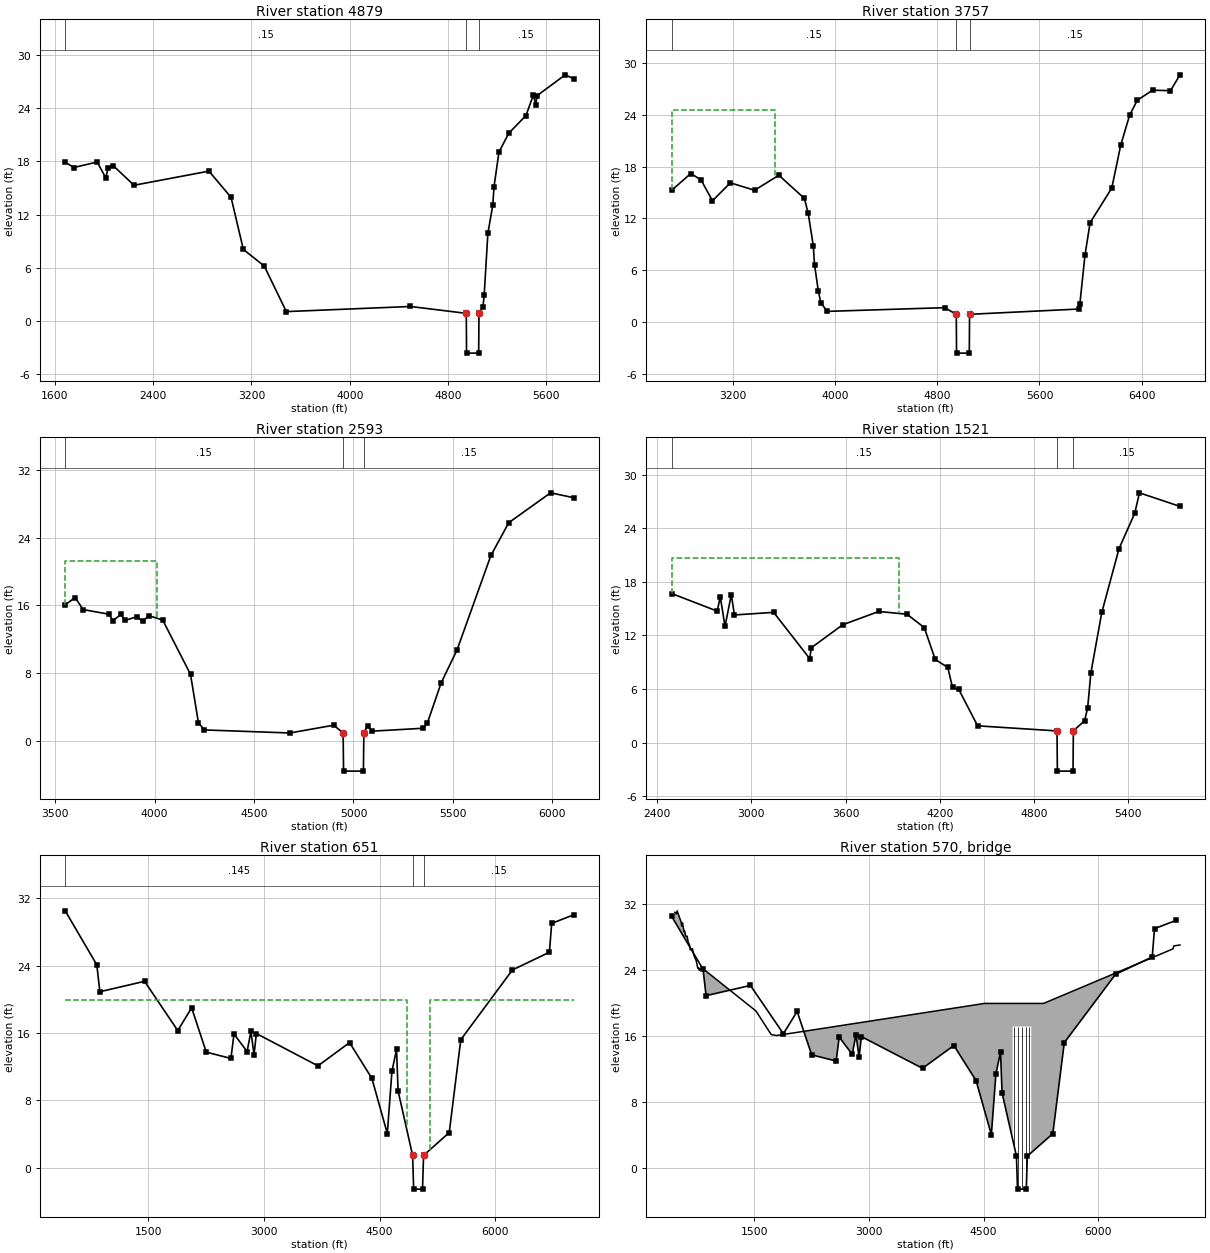
Type RM Length L Ch R = 1 ,4879    ,1122,1122,1122
BEGIN DESCRIPTION:
Black Mingo Creek 7.0
END DESCRIPTION:
XS GIS Cut Line= 3
       2475806.5       657714.41      2473298.93       655477.37
       2472763.7       654913.69
#Sta/Elev= 30
  1683.7   17.92  1753.7   17.32  1943.7   17.94  2013.7   16.15  2033.7   17.32
  2073.7   17.54  2243.7   15.31  2853.7   16.91  3033.7   13.94  3133.7    8.05
  3303.7    6.17  3483.7    1.01  4493.7    1.59  4948.4     .81  4950.6   -3.69
  5049.4   -3.69  5051.6     .81  5084.1    1.56  5094.1    2.87  5124.1    9.86
  5164.1   13.06  5174.1   15.14  5214.1   19.05  5294.1    21.2  5434.1    23.2
  5494.1   25.51  5514.1   24.43  5524.1   25.45  5754.1   27.81  5821.4   27.37
#Mann= 3 ,-1 , 0
  1683.7     .15       0  4948.4     .04       0  5051.6     .15       0
Bank Sta=4948.4,5051.6
XS Rating Curve= 0 ,0
Exp/Cntr=0.3,0.1

Type RM Length L Ch R = 1 ,3757    ,1164,1164,1164
BEGIN DESCRIPTION:
Black Mingo Creek 5.0
END DESCRIPTION:
XS GIS Cut Line= 3
      2475837.73       657100.49      2474397.75       655320.09
      2473869.01       653709.92
#Sta/Elev= 30
    2717   15.27    2867   17.21    2947   16.47    3037   14.05    3177   16.13
    3367   15.27    3557   17.01    3757   14.33    3787   12.62    3827    8.85
    3837    6.63    3867    3.54    3887     2.2    3937    1.23    4857    1.66
  4947.9     .89  4950.1   -3.61  5049.9   -3.61  5052.1     .89  5906.8     1.5
  5916.8    2.13  5956.8    7.75  5996.8   11.51  6166.8   15.52  6236.8   20.49
  6306.8   23.98  6366.8    25.7  6486.8   26.87  6626.8   26.81  6701.6   28.65
#Mann= 3 ,-1 , 0
    2717     .15       0  4947.9     .04       0  5052.1     .15       0
#XS Ineff= 2 , 0
       0  3530.3   24.63               0
Permanent Ineff=
       F       F
Bank Sta=4947.9,5052.1
XS Rating Curve= 0 ,0
Exp/Cntr=0.3,0.1

Type RM Length L Ch R = 1 ,2593    ,1072,1072,1072
BEGIN DESCRIPTION:
Black Mingo Creek 3.0
END DESCRIPTION:
XS GIS Cut Line= 3
      2475716.17       656006.72      2475096.41       654706.44
      2474646.76       653685.61
#Sta/Elev= 30
  3550.5   16.08  3600.5   16.94  3640.5   15.52  3770.5   14.97  3790.5   14.21
  3830.5   14.94  3850.5   14.23  3910.5   14.68  3940.5   14.12  3970.5    14.8
  4040.5   14.29  4180.5    7.88  4220.5    2.16  4250.5    1.32  4680.5     .96
  4900.5    1.88  4947.9     .96  4950.1   -3.54  5049.9   -3.54  5052.1     .96
  5070.9    1.81  5090.9    1.17  5350.9    1.52  5370.9    2.09  5440.9    6.88
  5520.9   10.77  5690.9    21.9  5780.9   25.77  5990.9   29.29  6106.4   28.72
#Mann= 3 ,-1 , 0
  3550.5     .15       0  4947.9     .04       0  5052.1     .15       0
#XS Ineff= 2 , 0
       0  4011.7   21.29               0
Permanent Ineff=
       F       F
Bank Sta=4947.9,5052.1
XS Rating Curve= 0 ,0
Exp/Cntr=0.3,0.1

Type RM Length L Ch R = 1 ,1521    ,870,870,870
BEGIN DESCRIPTION:
Black Mingo Creek 2.0
END DESCRIPTION:
XS GIS Cut Line= 3
      2477150.15       656529.26      2475970.49       654323.33
      2475643.27       653661.33
#Sta/Elev= 30
  2491.8   16.68  2781.8   14.71  2801.8    16.3  2831.8   12.99  2871.8   16.56
  2891.8   14.28  3141.8   14.57  3371.8    9.39  3381.8   10.61  3581.8   13.18
  3811.8   14.67  3991.8   14.36  4101.8   12.87  4171.8     9.3  4251.8     8.4
  4281.8    6.17  4321.8    5.94  4441.8    1.87  4947.9     1.3  4950.1    -3.2
  5049.9    -3.2  5052.1     1.3  5123.3    2.44  5143.3    3.88  5163.3    7.75
  5233.3   14.56  5343.3   21.71  5443.3   25.66  5473.3   27.95  5731.8   26.43
#Mann= 3 ,-1 , 0
  2491.8     .15       0  4947.9     .04       0  5052.1     .15       0
#XS Ineff= 2 , 0
       0  3938.5    20.7               0
Permanent Ineff=
       F       F
Bank Sta=4947.9,5052.1
XS Rating Curve= 0 ,0
Exp/Cntr=0.5,0.3

Type RM Length L Ch R = 1 ,651     ,156,156,156
BEGIN DESCRIPTION:
US Hwy 513 - US
END DESCRIPTION:
XS GIS Cut Line= 4
      2478451.24       658496.92      2477738.96       657384.58
      2476792.51       654281.81       2476158.3       652349.91
#Sta/Elev= 30
   419.6   30.52   829.6   24.11   869.6   20.91  1449.6   22.15  1880.5    16.3
  2060.5      19  2250.5   13.74  2570.5   12.99  2610.5   15.89  2780.5   13.81
  2830.5    16.2  2870.5   13.42  2900.5   15.95  3700.5   12.11  4110.5   14.87
  4400.5   10.62  4600.5    4.07  4660.5   11.46  4720.5   14.07  4740.5    9.13
    4929    1.47  4942.5   -2.53  5057.5   -2.53    5071    1.47  5404.4    4.19
  5554.4   15.22  6224.4    23.5  6704.4    25.6  6734.4   29.03  7017.7   30.04
#Mann= 3 ,-1 , 0
   419.6    .145       0    4929     .04       0    5071     .15       0
#XS Ineff= 2 , 0
       0    4850   19.97    5150       0   19.97
Permanent Ineff=
       F       F
Bank Sta=4929,5071
XS Rating Curve= 0 ,0
Exp/Cntr=0.5,0.3

Type RM Length L Ch R = 3 ,570     ,,,
BEGIN DESCRIPTION:
US Hwy 513 - TOR
Structure ID: LDS_BMC_01
Approximate Survey Structure
END DESCRIPTION:
Bridge Culvert--1,0,-1,-1, 0
Deck Dist Width WeirC Skew NumUp NumDn MinLoCord MaxHiCord MaxSubmerge Is_Ogee
68.5,25,3,0, 33, 33, , , 0.95, 0, 1,1,,
     461     481     491     541     551     561     581     591     601     621
     641     651     661     691     711     741     761     771     781     791
     861    1521    1721    1791  4510.5  4877.5  4877.5  5122.5  5122.5  5282.7
  6976.2  6986.2  7067.7
   31.02   30.81   31.19   29.89   29.34   29.74   28.68   28.71   28.13   28.12
   27.18   27.15   26.47    26.6   25.77   25.13   24.23   24.32   23.99   24.14
   23.94   19.06    16.2   16.08   19.97   19.97   19.97   19.97   19.97   19.97
   26.58   26.94   27.05
  -22.53  -22.53  -22.53  -22.53  -22.53  -22.53  -22.53  -22.53  -22.53  -22.53
  -22.53  -22.53  -22.53  -22.53  -22.53  -22.53  -22.53  -22.53  -22.53  -22.53
  -22.53  -22.53  -22.53  -22.53  -22.53  -22.53   17.17   17.17  -22.53  -22.53
  -22.53  -22.53  -22.53
     461     481     491     541     551     561     581     591     601     621
     641     651     661     691     711     741     761     771     781     791
     861    1521    1721    1791  4510.5  4877.5  4877.5  5122.5  5122.5  5282.7
  6976.2  6986.2  7067.7
   31.02   30.81   31.19   29.89   29.34   29.74   28.68   28.71   28.13   28.12
   27.18   27.15   26.47    26.6   25.77   25.13   24.23   24.32   23.99   24.14
   23.94   19.06    16.2   16.08   19.97   19.97   19.97   19.97   19.97   19.97
   26.58   26.94   27.05
  -22.53  -22.53  -22.53  -22.53  -22.53  -22.53  -22.53  -22.53  -22.53  -22.53
  -22.53  -22.53  -22.53  -22.53  -22.53  -22.53  -22.53  -22.53  -22.53  -22.53
  -22.53  -22.53  -22.53  -22.53  -22.53  -22.53   17.17   17.17  -22.53  -22.53
  -22.53  -22.53  -22.53
Pier Skew, UpSta & Num, DnSta & Num=  ,4902, 2 ,4902, 2 , 0 , 0 , 0 ,0,0
       1       1
    2.91   17.17
       1       1
    3.03   17.17
Pier Skew, UpSta & Num, DnSta & Num=  ,4951, 2 ,4951, 2 , 0 , 0 , 0 ,0,0
       1       1
   -2.53   17.17
       1       1
   -2.78   17.17
Pier Skew, UpSta & Num, DnSta & Num=  ,5000, 2 ,5000, 2 , 0 , 0 , 0 ,0,0
       1       1
   -2.53   17.17
       1       1
   -2.78   17.17
Pier Skew, UpSta & Num, DnSta & Num=  ,5049, 2 ,5049, 2 , 0 , 0 , 0 ,0,0
       1       1
   -2.53   17.17
       1       1
   -2.78   17.17
Pier Skew, UpSta & Num, DnSta & Num=  ,5098, 2 ,5098, 2 , 0 , 0 , 0 ,0,0
       1       1
    1.59   17.17
       1       1
     4.5   17.17
Abutment Skew #Up #Dn= , 2 , 2
  4877.5    4907
   17.17    2.64
  4877.5    4907
   17.17    2.69
Abutment Skew #Up #Dn= , 2 , 2
    5093  5122.5
    1.49   17.17
    5093  5122.5
    4.43   17.17
BR Coef= 1 , 1 , 0 ,1.25, 0 ,,,0.8,0,2,0,
WSPro=,,,, 1 ,,,, 0 ,,,, 0 ,,,,-1 ,-1 ,-1 , 0 , 0 , 0 , 0 , 0
BC Design=,, 0 ,, 0 ,,,,,,
BC HTab HWMax=30.65
BC Use User HTab Curves=0
BC User HTab FreeFlow(D)= 0

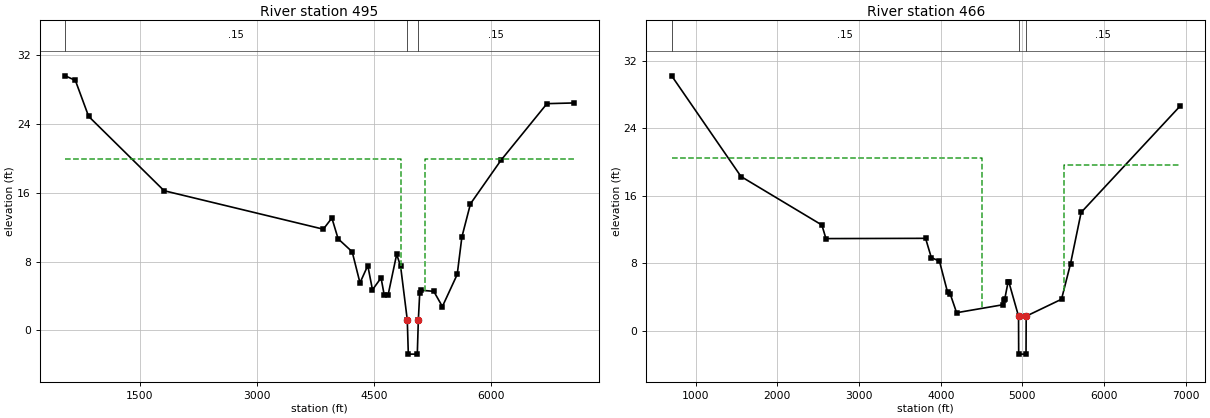
Type RM Length L Ch R = 1 ,495     ,29,29,29
BEGIN DESCRIPTION:
US Hwy 513 - DS
END DESCRIPTION:
XS GIS Cut Line= 4
      2478548.77       658360.25      2477875.55       657287.01
      2476938.87       654252.54      2476304.67       652281.63
#Sta/Elev= 30
   546.2   29.63   676.2    29.1   846.2   24.91  1813.1   16.25  3853.1   11.77
  3963.1   13.07  4043.1   10.65  4223.1    9.14  4323.1    5.52  4423.1    7.53
  4483.1    4.71  4593.1     6.1  4633.1    4.13  4683.1     4.1  4793.1    8.84
  4843.1    7.48    4929    1.22  4942.5   -2.78  5057.5   -2.78    5071    1.22
  5088.9    4.37  5108.9    4.66  5268.9    4.53  5378.9    2.76  5568.9     6.5
  5628.9   10.87  5738.9   14.73  6128.9   19.79  6718.9   26.39  7059.3   26.47
#Mann= 3 ,-1 , 0
   546.2     .15       0    4929     .04       0    5071     .15       0
#XS Ineff= 2 , 0
       0    4850   19.97    5150       0   19.97
Permanent Ineff=
       F       F
Bank Sta=4929,5071
XS Rating Curve= 0 ,0
Exp/Cntr=0.5,0.3

Type RM Length L Ch R = 1 ,466     ,0,0,0
BEGIN DESCRIPTION:
Black Mingo Creek 1.0
END DESCRIPTION:
XS GIS Cut Line= 4
      2478635.96       658153.35      2478132.37       657469.97
      2476961.11       654230.72      2476397.25       652384.19
#Sta/Elev= 23
   706.1   30.22    1555   18.28    2545   12.53    2595   10.92    3815   10.95
    3885    8.67    3985    8.24    4085    4.53    4115     4.4    4195    2.13
    4765    3.08    4775    3.62    4785    3.79    4825    5.76    4835    5.76
  4953.1    1.72  4955.1   -2.78  5044.9   -2.78  5046.9    1.72  5479.5    3.73
  5589.5    7.93  5719.5   14.02  6930.2   26.62
#Mann= 3 ,-1 , 0
   706.1     .15       0  4953.1     .04       0  5046.9     .15       0
#XS Ineff= 2 , 0
       0    4500   20.47  5503.8       0   19.69
Permanent Ineff=
       F       F
Bank Sta=4953.1,5046.9
XS Rating Curve= 0 ,0
Exp/Cntr=0.3,0.1

Chan Stop Cuts=-1
Use User Specified Reach Order=0
Composite Channel Slope=5

--- Black Mingo Creek.g01 (geometry) ---

Geom Title=Duplicate Effective
Program Version=4.10

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
River Reach=Black Mingo Cree,Reach-1