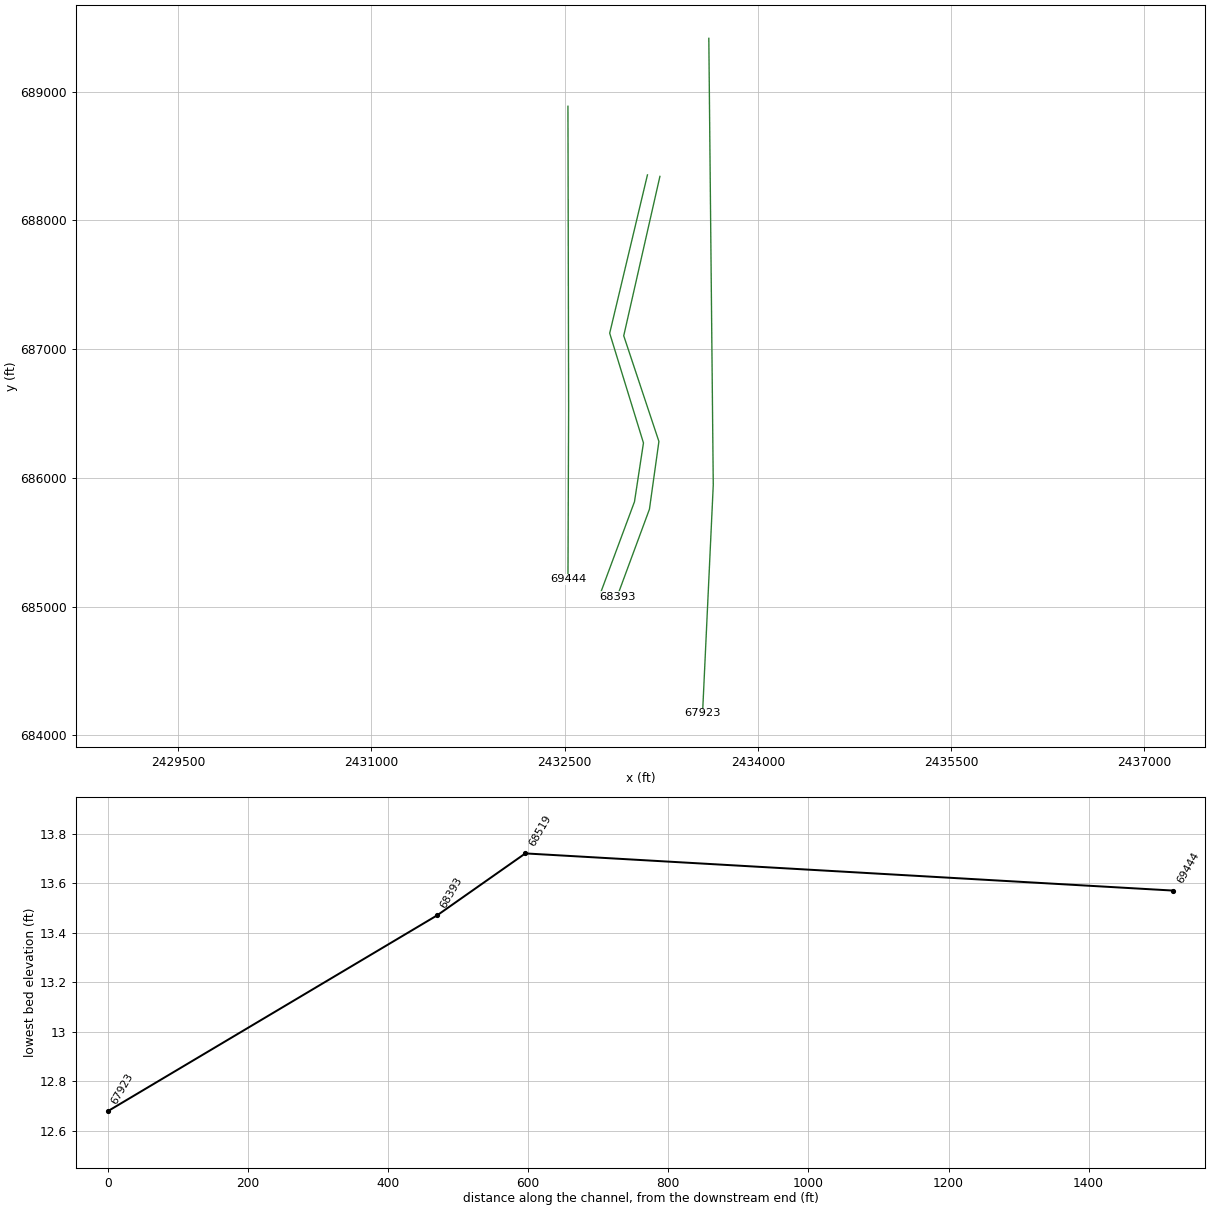
HEC-RAS study Black Mingo Creek.prj: Black Mingo Creek Limited Detail Study

--- Black Mingo Creek.g01 (geometry) --- (continued)

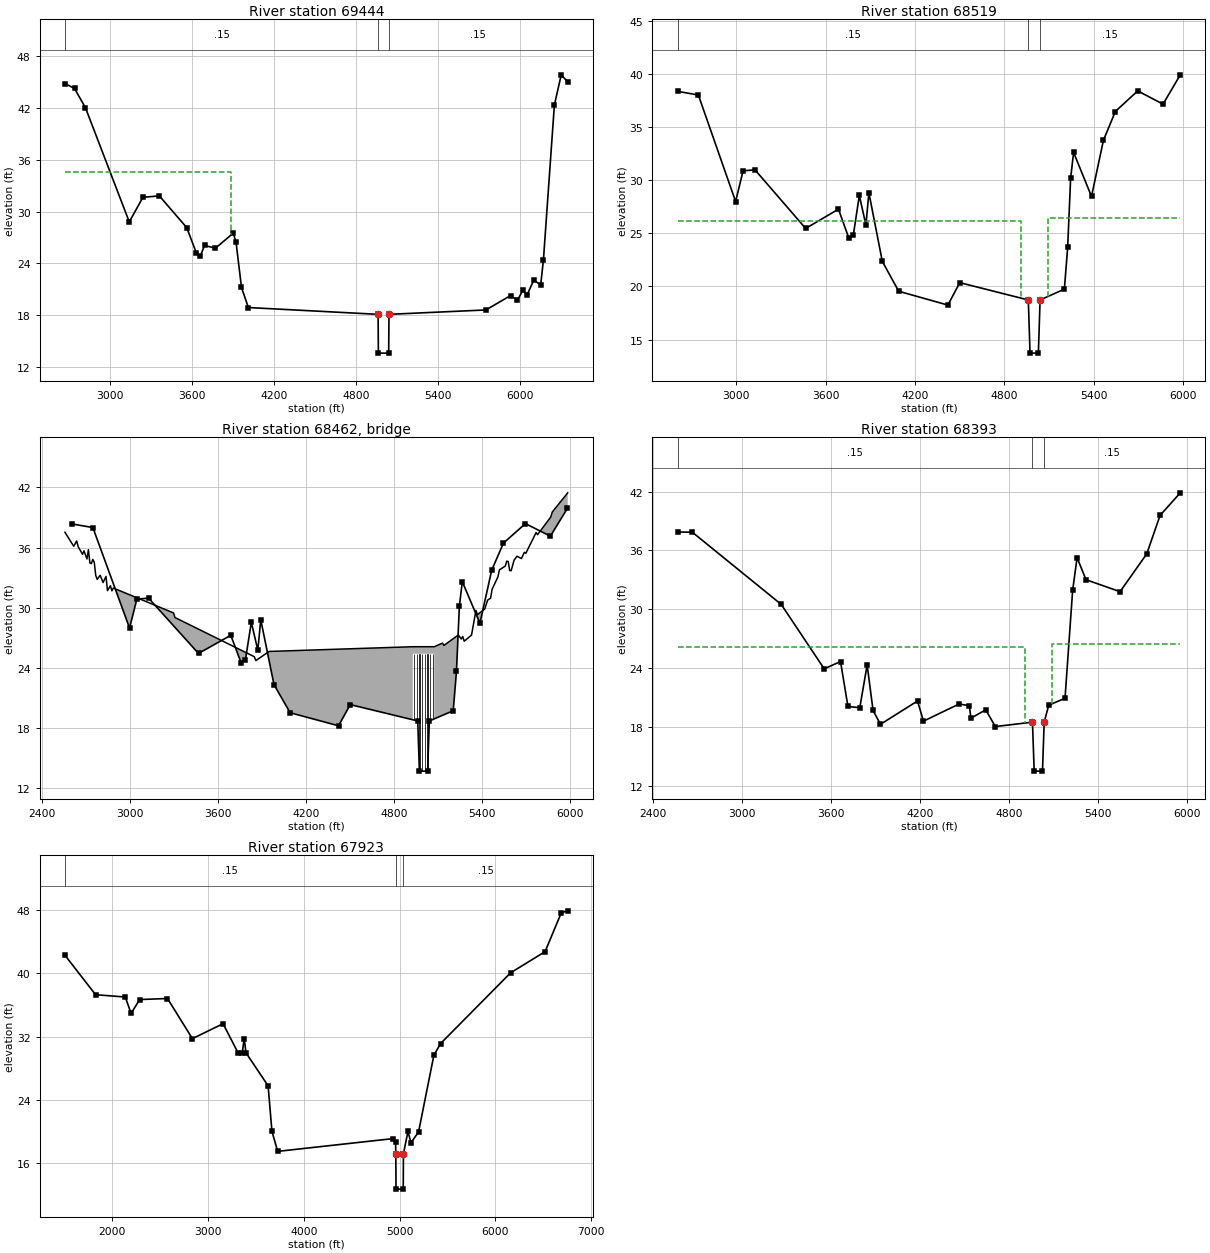
Type RM Length L Ch R = 1 ,69444   ,925,925,925
BEGIN DESCRIPTION:
Black Mingo Creek 140.0
END DESCRIPTION:
XS GIS Cut Line= 3
      2432526.37       688887.18      2432531.63       686551.21
      2432526.53       685213.79
#Sta/Elev= 30
  2672.2   44.85  2742.2   44.28  2822.2   42.04  3142.2    28.8  3242.2   31.65
  3362.2   31.81  3562.2   28.13  3632.2    25.2  3662.2   24.85  3692.2   26.06
  3772.2   25.75  3902.2   27.49  3922.2   26.46  3962.2   21.19  4012.2   18.86
  4960.2   18.07  4962.4   13.57  5037.6   13.57  5039.8   18.07  5748.2   18.58
  5928.2   20.25  5978.2   19.71  6018.2   20.86  6048.2   20.31  6098.2   22.05
  6148.2   21.48  6168.2   24.38  6248.2   42.35  6298.2   45.86  6345.6   45.05
#Mann= 3 ,-1 , 0
  2672.2     .15       0  4960.2     .05       0  5039.8     .15       0
#XS Ineff= 2 , 0
       0  3888.7   34.62               0
Permanent Ineff=
       F       F
Bank Sta=4960.2,5039.8
XS Rating Curve= 0 ,0
Exp/Cntr=0.5,0.3

Type RM Length L Ch R = 1 ,68519   ,126,126,126
BEGIN DESCRIPTION:
Battery Park Rd - US
END DESCRIPTION:
XS GIS Cut Line= 5
      2433143.53        688353.8      2432850.46       687123.91
      2433112.57       686271.48       2433042.9       685814.76
      2432779.69       685106.43
#Sta/Elev= 30
  2606.4   38.35  2746.4      38  2996.4   27.98  3046.4   30.87  3126.4   30.96
  3466.4   25.45  3686.4   27.26  3756.4   24.53  3786.4   24.83  3826.4   28.55
  3870.7   25.78  3890.7   28.81  3980.7   22.35  4090.7   19.54  4420.7   18.24
  4500.7   20.35  4960.5   18.72    4972   13.72    5028   13.72  5039.5   18.72
  5202.5   19.74  5224.5   23.66  5244.5    30.2  5264.5    32.6  5384.5   28.46
  5464.5   33.74  5544.5   36.45  5694.5   38.39  5864.5   37.14  5980.2    39.9
#Mann= 3 ,-1 , 0
  2606.4     .15       0  4960.5     .05       0  5039.5     .15       0
#XS Ineff= 2 , 0
       0    4910   26.12    5090       0   26.44
Permanent Ineff=
       F       F
Bank Sta=4960.5,5039.5
XS Rating Curve= 0 ,0
Exp/Cntr=0.5,0.3

Type RM Length L Ch R = 3 ,68462   ,,,
BEGIN DESCRIPTION:
Battery Park Rd - TOR
Structure ID: LDS_BMC_04
Approximate Survey Structure
END DESCRIPTION:
Bridge Culvert--1,0,-1,-1, 0
Deck Dist Width WeirC Skew NumUp NumDn MinLoCord MaxHiCord MaxSubmerge Is_Ogee
43.5,27,3,0, 60, 60, , , 0.95, 0, 1,1,,
    2556    2616    2636    2646    2676    2686    2706    2716    2726    2736
    2746    2756    2766    2776    2796    2816    2836    2846    2866    2876
    2886    3296    3306    3846  3857.6  3947.6  4926.8  4926.8  5073.3  5073.3
  5129.2  5139.2  5237.2  5257.2  5267.2  5277.2  5327.2  5357.2  5367.2  5417.2
  5437.2  5457.2  5467.2  5507.2  5517.2  5557.2  5567.2  5577.2  5587.2  5597.2
  5617.2  5637.2  5667.2  5687.2  5697.2  5767.2  5777.2  5867.2  5877.2  5982.7
   37.53   36.13   36.67    36.1   35.33   35.68   34.87   35.79   34.47    34.4
   34.82   34.53   33.23   32.83   33.24   32.52   33.13   31.71    32.2   31.69
   31.97   29.49   29.03   25.13   24.74   25.65   26.12   26.12   26.12   26.12
   26.48   26.25   27.29   26.89   27.14   26.67   27.28   29.74   29.32   29.88
   30.77   30.96   31.84   33.09   33.78   34.16   34.65   34.61   33.72   33.69
   34.75   35.14   34.91   35.53   35.43    37.5   37.29   39.05   39.54   41.46
   -6.28   -6.28   -6.28   -6.28   -6.28   -6.28   -6.28   -6.28   -6.28   -6.28
   -6.28   -6.28   -6.28   -6.28   -6.28   -6.28   -6.28   -6.28   -6.28   -6.28
   -6.28   -6.28   -6.28   -6.28   -6.28   -6.28   -6.28   25.42   25.42   -6.28
   -6.28   -6.28   -6.28   -6.28   -6.28   -6.28   -6.28   -6.28   -6.28   -6.28
   -6.28   -6.28   -6.28   -6.28   -6.28   -6.28   -6.28   -6.28   -6.28   -6.28
   -6.28   -6.28   -6.28   -6.28   -6.28   -6.28   -6.28   -6.28   -6.28   -6.28
    2556    2616    2636    2646    2676    2686    2706    2716    2726    2736
    2746    2756    2766    2776    2796    2816    2836    2846    2866    2876
    2886    3296    3306    3846  3857.6  3947.6  4926.8  4926.8  5073.3  5073.3
  5129.2  5139.2  5237.2  5257.2  5267.2  5277.2  5327.2  5357.2  5367.2  5417.2
  5437.2  5457.2  5467.2  5507.2  5517.2  5557.2  5567.2  5577.2  5587.2  5597.2
  5617.2  5637.2  5667.2  5687.2  5697.2  5767.2  5777.2  5867.2  5877.2  5982.7
   37.53   36.13   36.67    36.1   35.33   35.68   34.87   35.79   34.47    34.4
   34.82   34.53   33.23   32.83   33.24   32.52   33.13   31.71    32.2   31.69
   31.97   29.49   29.03   25.13   24.74   25.65   26.12   26.12   26.12   26.12
   26.48   26.25   27.29   26.89   27.14   26.67   27.28   29.74   29.32   29.88
   30.77   30.96   31.84   33.09   33.78   34.16   34.65   34.61   33.72   33.69
   34.75   35.14   34.91   35.53   35.43    37.5   37.29   39.05   39.54   41.46
   -6.28   -6.28   -6.28   -6.28   -6.28   -6.28   -6.28   -6.28   -6.28   -6.28
   -6.28   -6.28   -6.28   -6.28   -6.28   -6.28   -6.28   -6.28   -6.28   -6.28
   -6.28   -6.28   -6.28   -6.28   -6.28   -6.28   -6.28   25.42   25.42   -6.28
   -6.28   -6.28   -6.28   -6.28   -6.28   -6.28   -6.28   -6.28   -6.28   -6.28
   -6.28   -6.28   -6.28   -6.28   -6.28   -6.28   -6.28   -6.28   -6.28   -6.28
   -6.28   -6.28   -6.28   -6.28   -6.28   -6.28   -6.28   -6.28   -6.28   -6.28
Pier Skew, UpSta & Num, DnSta & Num=  ,4935.9, 2 ,4935.9, 2 , 0 , 0 , 0 ,0,0
       1       1
   18.32   25.42
       1       1
   18.61   25.42
Pier Skew, UpSta & Num, DnSta & Num=  ,4954.2, 2 ,4954.2, 2 , 0 , 0 , 0 ,0,0
       1       1
   18.62   25.42
       1       1
   18.51   25.42
Pier Skew, UpSta & Num, DnSta & Num=  ,4972.5, 2 ,4972.5, 2 , 0 , 0 , 0 ,0,0
       1       1
   13.72   25.42
       1       1
   13.47   25.42
Pier Skew, UpSta & Num, DnSta & Num=  ,4990.8, 2 ,4990.8, 2 , 0 , 0 , 0 ,0,0
       1       1
   13.72   25.42
       1       1
   13.47   25.42
Pier Skew, UpSta & Num, DnSta & Num=  ,5009.2, 2 ,5009.2, 2 , 0 , 0 , 0 ,0,0
       1       1
   13.72   25.42
       1       1
   13.47   25.42
Pier Skew, UpSta & Num, DnSta & Num=  ,5027.5, 2 ,5027.5, 2 , 0 , 0 , 0 ,0,0
       1       1
   13.72   25.42
       1       1
   13.47   25.42
Pier Skew, UpSta & Num, DnSta & Num=  ,5045.8, 2 ,5045.8, 2 , 0 , 0 , 0 ,0,0
       1       1
    18.7   25.42
       1       1
   18.76   25.42
Pier Skew, UpSta & Num, DnSta & Num=  ,5064.1, 2 ,5064.1, 2 , 0 , 0 , 0 ,0,0
       1       1
   18.63   25.42
       1       1
   19.83   25.42
Abutment Skew #Up #Dn= , 2 , 2
  4926.8    4945
   25.42   18.47
  4926.8    4945
   25.42   18.56
Abutment Skew #Up #Dn= , 2 , 2
    5055  5073.3
   18.66   25.42
    5055  5073.3
   19.26   25.42
BR Coef= 1 , 1 , 0 ,1.25, 0 ,,,0.8,0,2,0,
WSPro=,,,, 1 ,,,, 0 ,,,, 0 ,,,,-1 ,-1 ,-1 , 0 , 0 , 0 , 0 , 0
BC Design=,, 0 ,, 0 ,,,,,,
BC HTab HWMax=39.9
BC Use User HTab Curves=0
BC User HTab FreeFlow(D)= 0

Type RM Length L Ch R = 1 ,68393   ,470,470,470
BEGIN DESCRIPTION:
Battery Park Rd - DS
END DESCRIPTION:
XS GIS Cut Line= 5
       2433240.3       688342.21      2432959.45       687104.09
      2433232.55       686283.09      2433159.01        685756.7
      2432907.43       685075.48
#Sta/Elev= 30
  2565.3   37.88  2665.3   37.86  3265.3   30.49  3555.3   23.91  3665.3   24.66
  3715.3   20.07  3795.3   19.94  3844.9   24.31  3884.9   19.66  3934.9   18.25
  4184.9   20.63  4224.9   18.57  4464.9   20.32  4534.9   20.15  4544.9   18.87
  4644.9   19.73  4710.1   18.02  4960.5   18.47    4972   13.47    5028   13.47
  5039.5   18.47  5070.1    20.2  5180.1   20.91  5231.6   31.94  5261.6   35.26
  5321.6   33.01  5551.6   31.79  5731.6   35.65  5821.6   39.58  5957.8   41.88
#Mann= 3 ,-1 , 0
  2565.3     .15       0  4960.5     .05       0  5039.5     .15       0
#XS Ineff= 2 , 0
       0    4910   26.12    5090       0   26.48
Permanent Ineff=
       F       F
Bank Sta=4960.5,5039.5
XS Rating Curve= 0 ,0
Exp/Cntr=0.5,0.3

Type RM Length L Ch R = 1 ,67923   ,1384,1384,1384
BEGIN DESCRIPTION:
Black Mingo Creek 136.0
END DESCRIPTION:
XS GIS Cut Line= 3
        2433620.       689414.69       2433654.5       685944.91
      2433571.35       684170.71
#Sta/Elev= 30
  1507.7   42.29  1827.7   37.29  2137.7      37  2197.7   34.92  2287.7   36.68
  2577.7   36.81  2837.7   31.73  3157.7   33.62  3317.7   29.85  3357.7   29.89
  3377.7   31.73  3397.7   29.92  3627.7   25.76  3667.7      20  3727.7   17.46
  4927.7   19.07  4957.7   18.69  4960.2   17.18  4962.4   12.68  5037.6   12.68
  5039.8   17.18  5087.6      20  5117.6   18.54  5197.6   19.92  5357.6   29.64
  5427.6   31.11  6157.6   40.06  6517.6   42.74  6687.6   47.68  6753.8   47.91
#Mann= 3 ,-1 , 0
  1507.7     .15       0  4960.2     .05       0  5039.8     .15       0
Bank Sta=4960.2,5039.8
XS Rating Curve= 0 ,0
Exp/Cntr=0.3,0.1

--- Black Mingo Creek.g02 (geometry) ---

Geom Title=Corrected Effective
Program Version=4.10

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
River Reach=Black Mingo Cree,Reach-1

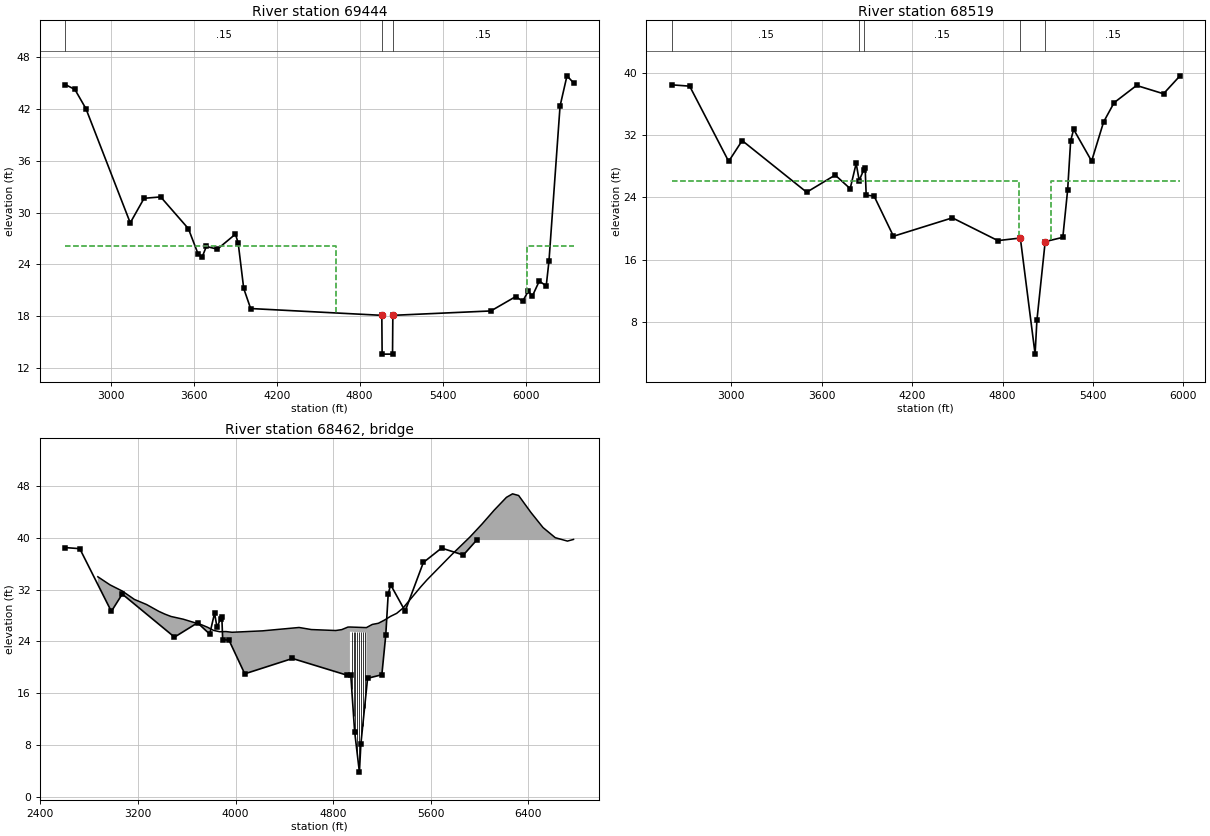
Type RM Length L Ch R = 1 ,69444   ,925,925,925
BEGIN DESCRIPTION:
Black Mingo Creek 140.0
END DESCRIPTION:
XS GIS Cut Line= 3
      2432526.37       688887.18      2432531.63       686551.21
      2432526.53       685213.79
#Sta/Elev= 30
  2672.2   44.85  2742.2   44.28  2822.2   42.04  3142.2    28.8  3242.2   31.65
  3362.2   31.81  3562.2   28.13  3632.2    25.2  3662.2   24.85  3692.2   26.06
  3772.2   25.75  3902.2   27.49  3922.2   26.46  3962.2   21.19  4012.2   18.86
  4960.2   18.07  4962.4   13.57  5037.6   13.57  5039.8   18.07  5748.2   18.58
  5928.2   20.25  5978.2   19.71  6018.2   20.86  6048.2   20.31  6098.2   22.05
  6148.2   21.48  6168.2   24.38  6248.2   42.35  6298.2   45.86  6345.6   45.05
#Mann= 3 ,-1 , 0
  2672.2     .15       0  4960.2     .05       0  5039.8     .15       0
#XS Ineff= 2 , 0
       0    4626    26.1    6010       0    26.1
Permanent Ineff=
       T       T
Bank Sta=4960.2,5039.8
XS Rating Curve= 0 ,0
Exp/Cntr=0.5,0.3

Type RM Length L Ch R = 1 ,68519   ,126,126,126
BEGIN DESCRIPTION:
Battery Park Rd - US
END DESCRIPTION:
XS GIS Cut Line= 5
      2433143.53        688353.8      2432850.46       687123.91
      2433112.57       686271.48       2433042.9       685814.76
      2432779.69       685106.43
#Sta/Elev= 30
  2603.5    38.5 2722.96   38.33  2981.8   28.64  3071.4   31.32 3499.48   24.67
 3688.64   26.88 3788.19   25.13 3828.01   28.38 3847.92   26.18 3877.74   27.53
 3887.65   27.75  3894.5   24.28  3946.5   24.19  4075.5      19  4466.5   21.37
  4768.5   18.44  4917.5   18.77  5015.5    3.82  5027.5    8.17  5082.5   18.31
  5199.5   18.86 5231.59   24.98 5251.47   31.29 5271.35   32.76 5390.66   28.68
 5470.19   33.72 5539.78    36.2 5688.91   38.42 5867.86   37.35 5977.22   39.66
#Mann= 5 ,-1 , 0
  2603.5     .15       0 3847.92     .05       0 3877.74     .15       0
  4917.5     .05       0  5082.5     .15       0
#XS Ineff= 2 , 0
       0    4911    26.1    5119       0    26.1
Permanent Ineff=
       T       T
Bank Sta=4917.5,5082.5
XS Rating Curve= 0 ,0
Exp/Cntr=0.5,0.3

Type RM Length L Ch R = 3 ,68462   ,,,
BEGIN DESCRIPTION:
Battery Park Rd - TOR
Structure ID: LDS_BMC_04
Approximate Survey Structure
END DESCRIPTION:
Bridge Culvert--1,0,-1,-1, 0
Deck Dist Width WeirC Skew NumUp NumDn MinLoCord MaxHiCord MaxSubmerge Is_Ogee
47.75,28.2,3,0, 45, 44, , , 0.95, 0, 2,2,,
    2871    2971    3071    3171    3271    3371    3421    3471    3571    3721
    3771    3821    3871    3921    3971    4221    4521    4621    4821    4871
    4921 4937.75 4937.75 5072.75 5072.75    5121    5171    5221    5271    5321
    5371    5521    5571    5771    5921    6021    6121    6221    6271    6321
    6421    6521    6621    6721    6771
   33.99   32.74   31.79   30.49    29.7   28.65   28.22   27.86   27.44   26.58
   26.19    25.7    25.5   25.53   25.42   25.64   26.16   25.84   25.69   25.83
   26.22   26.23   26.23   26.14   26.14   26.63   26.81    27.3   27.88   28.34
   29.12   32.49   33.54   37.38   40.12   42.14   44.29   46.26    46.8   46.54
   43.94   41.59   40.03    39.5   39.76
   -6.28   -6.28   -6.28   -6.28   -6.28   -6.28   -6.28   -6.28   -6.28   -6.28
   -6.28   -6.28   -6.28   -6.28   -6.28   -6.28   -6.28   -6.28   -6.28   -6.28
   -6.28   -6.28   25.51   25.37   -6.28   -6.28   -6.28   -6.28   -6.28   -6.28
   -6.28   -6.28   -6.28   -6.28   -6.28   -6.28   -6.28   -6.28   -6.28   -6.28
   -6.28   -6.28   -6.28   -6.28   -6.28
    2844    2944    3044    3144    3244    3344    3394    3444    3544    3694
    3744    3794    3844    3894    3944    4194    4494    4594    4794    4844
    4894  4929.5  4929.5  5064.5  5064.5    5094    5144    5244    5294    5344
    5494    5544    5744    5894    5994    6094    6194    6244    6294    6394
    6494    6594    6694    6744
   33.99   32.74   31.79   30.49    29.7   28.65   28.22   27.86   27.44   26.58
   26.19    25.7    25.5   25.53   25.42   25.64   26.16   25.84   25.69   25.83
   26.22   26.23   26.23   26.14   26.14   26.63   26.81   27.88   28.34   29.12
   32.49   33.54   37.38   40.12   42.14   44.29   46.26    46.8   46.54   43.94
   41.59   40.03    39.5   39.76
   -6.28   -6.28   -6.28   -6.28   -6.28   -6.28   -6.28   -6.28   -6.28   -6.28
   -6.28   -6.28   -6.28   -6.28   -6.28   -6.28   -6.28   -6.28   -6.28   -6.28
   -6.28   -6.28   25.51   25.37   -6.28   -6.28   -6.28   -6.28   -6.28   -6.28
   -6.28   -6.28   -6.28   -6.28   -6.28   -6.28   -6.28   -6.28   -6.28   -6.28
   -6.28   -6.28   -6.28   -6.28
Pier Skew, UpSta & Num, DnSta & Num=  ,4952.75, 2 ,4944.5, 2 , 0 , 0 , 0 ,,
       1       1
    3.82      26
       1       1
    3.82   25.42
Pier Skew, UpSta & Num, DnSta & Num=  ,4967.75, 2 ,4959.5, 2 , 0 , 0 , 0 ,,
       1       1
    3.82      26
       1       1
    3.82   25.42
Pier Skew, UpSta & Num, DnSta & Num=  ,4982.75, 2 ,4974.5, 2 , 0 , 0 , 0 ,,
       1       1
    3.82      26
       1       1
    3.82   25.42
Pier Skew, UpSta & Num, DnSta & Num=  ,4997.75, 2 ,4989.5, 2 , 0 , 0 , 0 ,,
       1       1
    3.82      26
       1       1
    3.82   25.42
Pier Skew, UpSta & Num, DnSta & Num=  ,5012.75, 2 ,5004.5, 2 , 0 , 0 , 0 ,,
       1       1
    3.82      26
       1       1
    3.82   25.42
Pier Skew, UpSta & Num, DnSta & Num=  ,5027.75, 2 ,5019.5, 2 , 0 , 0 , 0 ,,
       1       1
    3.82      26
       1       1
    3.82   25.42
Pier Skew, UpSta & Num, DnSta & Num=  ,5042.75, 2 ,5034.5, 2 , 0 , 0 , 0 ,,
       1       1
    3.82      26
       1       1
    3.82   25.42
Pier Skew, UpSta & Num, DnSta & Num=  ,5057.75, 2 ,5049.5, 2 , 0 , 0 , 0 ,,
       1       1
    3.82      26
       1       1
    3.82   25.42
BR Coef= 1 , 1 , 0 ,1.25, 0 ,,,0.8,0,1.2,0,
WSPro=,,,, 1 ,,,, 0 ,,,, 0 ,,,,-1 ,-1 ,-1 , 0 , 0 , 0 , 0 , 0
BR U #Sta/Elev= 30
  2603.5    38.5 2722.96   38.33  2981.8   28.64  3071.4   31.32 3499.48   24.67
 3688.64   26.88 3788.19   25.13 3828.01   28.38 3847.92   26.18 3877.74   27.53
 3887.65   27.75  3894.5   24.28  3946.5   24.19  4075.5      19  4466.5   21.37
  4917.5   18.77  4944.5   18.87  4976.5   10.05  5015.5    3.82  5027.5    8.17
  5082.5   18.31  5199.5   18.86 5231.59   24.98 5251.47   31.29 5271.35   32.76
 5390.66   28.68 5539.78    36.2 5688.91   38.42 5867.86   37.35 5977.22   39.66
BR U #Mann= 5
  2603.5     .15 3847.92     .05 3877.74     .15  4917.5     .05  5082.5     .15
BR U Banks=4944.5,
BR D #Sta/Elev= 30
    2557   37.83 2646.97   37.95 2906.88   33.63 3266.75   30.37 3546.65   23.86
  3666.6   24.49 3706.59    20.2 3716.59   20.05 3786.56   20.36 3836.49   24.11
    3931   17.95    4163   20.34    4640   19.93    4755   17.83  4929.5   18.51
    4952   18.46    4960    7.74    4998    7.03    5042    8.12    5048   18.98
    5069   19.86  5174.1   20.55 5203.63   28.25 5243.21   33.87  5263.1    34.7
 5432.21   31.47 5551.58   31.89 5720.69   35.45 5830.12   40.16 5949.49      42
BR D #Mann= 3
    2557     .15  4929.5     .05    5069     .15
BC Design=,, 0 ,, 0 ,,8,4952.75,4944.5,15,1
BC HTab HWMax=39.9
BC Use User HTab Curves=0
BC User HTab FreeFlow(D)= 0