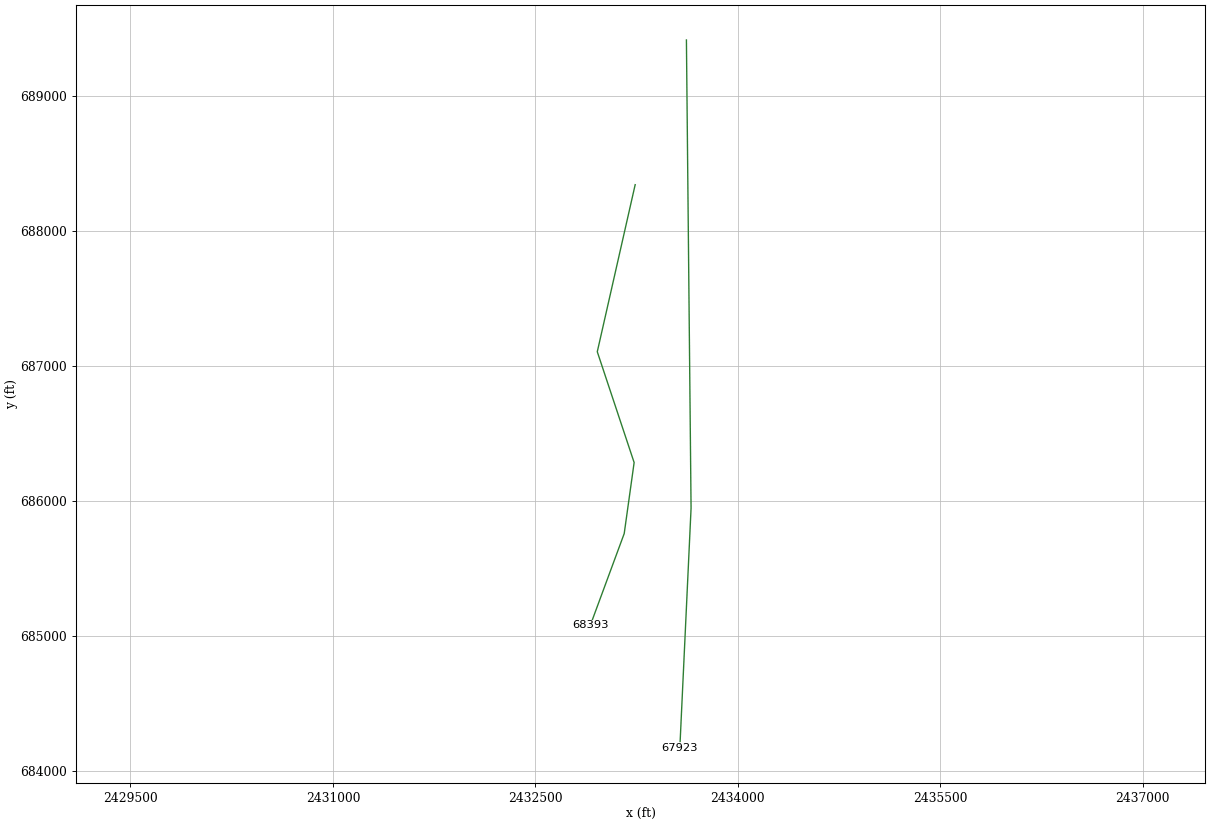
HEC-RAS study Black Mingo Creek.prj: Black Mingo Creek Limited Detail Study

--- Black Mingo Creek.g02 (geometry) --- (continued)

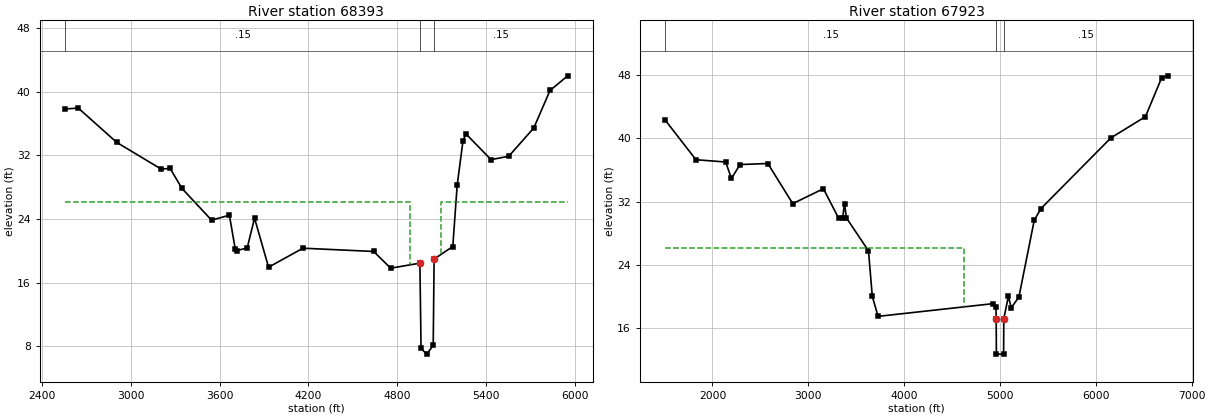
Type RM Length L Ch R = 1 ,68393   ,470,470,470
BEGIN DESCRIPTION:
Battery Park Rd - DS
END DESCRIPTION:
XS GIS Cut Line= 5
       2433240.3       688342.21      2432959.45       687104.09
      2433232.55       686283.09      2433159.01        685756.7
      2432907.43       685075.48
#Sta/Elev= 30
    2557   37.83 2646.97   37.95 2906.88   33.63 3206.77   30.28 3266.75   30.37
 3346.72   27.85 3546.65   23.86  3666.6   24.49 3706.59    20.2 3716.59   20.05
 3786.56   20.36 3836.49   24.11    3931   17.95    4163   20.34    4640   19.93
    4755   17.83    4952   18.46    4960    7.74    4998    7.03    5042    8.12
    5048   18.98  5174.1   20.55 5203.63   28.25 5243.21   33.87  5263.1    34.7
 5432.21   31.47 5551.58   31.89 5720.69   35.45 5830.12   40.16 5949.49      42
#Mann= 3 ,-1 , 0
    2557     .15       0    4952     .05       0    5048     .15       0
#XS Ineff= 2 , 0
       0    4884    26.1    5095       0    26.1
Permanent Ineff=
       F       F
Bank Sta=4952,5048
XS Rating Curve= 0 ,0
Exp/Cntr=0.5,0.3

Type RM Length L Ch R = 1 ,67923   ,1384,1384,1384
BEGIN DESCRIPTION:
Black Mingo Creek 136.0
END DESCRIPTION:
XS GIS Cut Line= 3
        2433620.       689414.69       2433654.5       685944.91
      2433571.35       684170.71
#Sta/Elev= 30
  1507.7   42.29  1827.7   37.29  2137.7      37  2197.7   34.92  2287.7   36.68
  2577.7   36.81  2837.7   31.73  3157.7   33.62  3317.7   29.85  3357.7   29.89
  3377.7   31.73  3397.7   29.92  3627.7   25.76  3667.7      20  3727.7   17.46
  4927.7   19.07  4957.7   18.69  4960.2   17.18  4962.4   12.68  5037.6   12.68
  5039.8   17.18  5087.6      20  5117.6   18.54  5197.6   19.92  5357.6   29.64
  5427.6   31.11  6157.6   40.06  6517.6   42.74  6687.6   47.68  6753.8   47.91
#Mann= 3 ,-1 , 0
  1507.7     .15       0  4960.2     .05       0  5039.8     .15       0
#XS Ineff= 2 , 0
       0    4627    26.1               0
Permanent Ineff=
       T       F
Bank Sta=4960.2,5039.8
XS Rating Curve= 0 ,0
Exp/Cntr=0.3,0.1

--- Black Mingo Creek.g03 (geometry) ---

Geom Title=Natural SCDOT
Program Version=4.10

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
River Reach=Black Mingo Cree,Reach-1

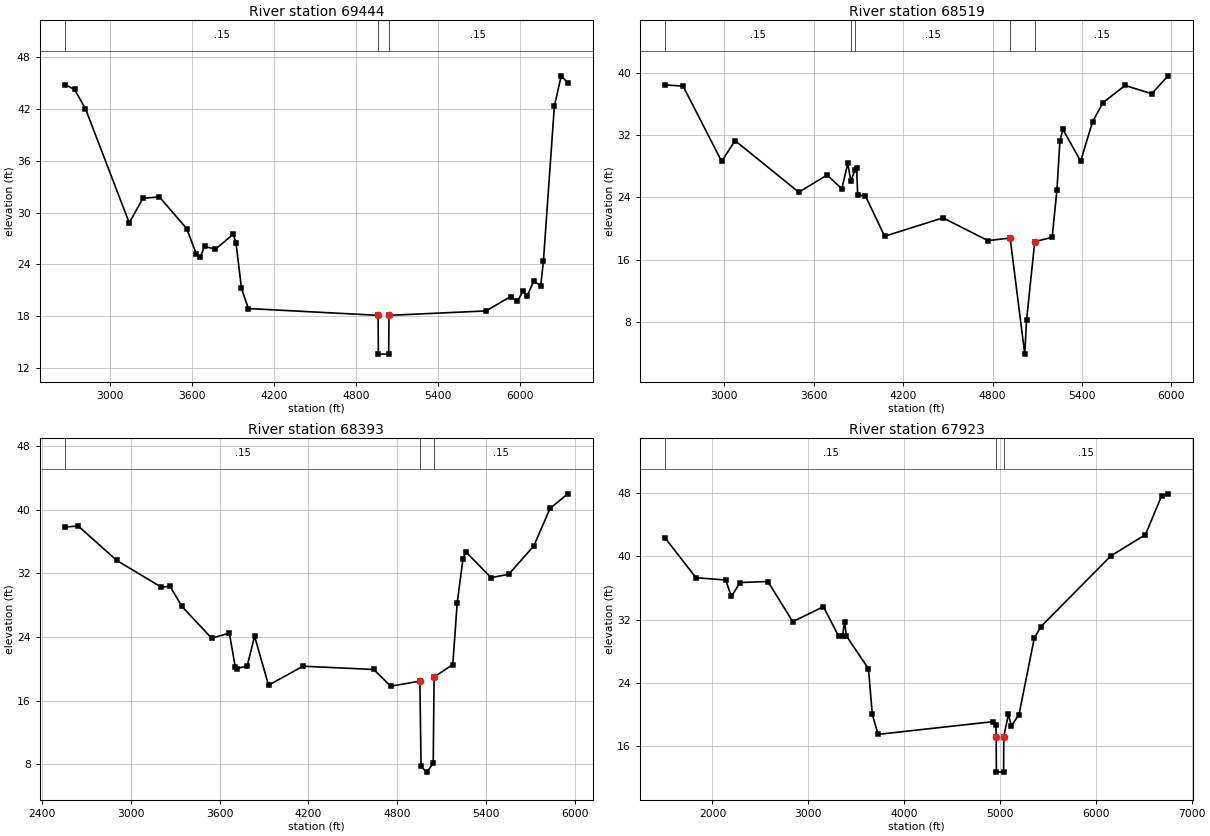
Type RM Length L Ch R = 1 ,69444   ,925,925,925
BEGIN DESCRIPTION:
Black Mingo Creek 140.0
END DESCRIPTION:
XS GIS Cut Line= 3
      2432526.37       688887.18      2432531.63       686551.21
      2432526.53       685213.79
#Sta/Elev= 30
  2672.2   44.85  2742.2   44.28  2822.2   42.04  3142.2    28.8  3242.2   31.65
  3362.2   31.81  3562.2   28.13  3632.2    25.2  3662.2   24.85  3692.2   26.06
  3772.2   25.75  3902.2   27.49  3922.2   26.46  3962.2   21.19  4012.2   18.86
  4960.2   18.07  4962.4   13.57  5037.6   13.57  5039.8   18.07  5748.2   18.58
  5928.2   20.25  5978.2   19.71  6018.2   20.86  6048.2   20.31  6098.2   22.05
  6148.2   21.48  6168.2   24.38  6248.2   42.35  6298.2   45.86  6345.6   45.05
#Mann= 3 ,-1 , 0
  2672.2     .15       0  4960.2     .05       0  5039.8     .15       0
Bank Sta=4960.2,5039.8
XS Rating Curve= 0 ,0
Exp/Cntr=0.3,0.1

Type RM Length L Ch R = 1 ,68519   ,126,126,126
BEGIN DESCRIPTION:
Battery Park Rd - US
END DESCRIPTION:
XS GIS Cut Line= 5
      2433143.53        688353.8      2432850.46       687123.91
      2433112.57       686271.48       2433042.9       685814.76
      2432779.69       685106.43
#Sta/Elev= 30
  2603.5    38.5 2722.96   38.33  2981.8   28.64  3071.4   31.32 3499.48   24.67
 3688.64   26.88 3788.19   25.13 3828.01   28.38 3847.92   26.18 3877.74   27.53
 3887.65   27.75  3894.5   24.28  3946.5   24.19  4075.5      19  4466.5   21.37
  4768.5   18.44  4917.5   18.77  5015.5    3.82  5027.5    8.17  5082.5   18.31
  5199.5   18.86 5231.59   24.98 5251.47   31.29 5271.35   32.76 5390.66   28.68
 5470.19   33.72 5539.78    36.2 5688.91   38.42 5867.86   37.35 5977.22   39.66
#Mann= 5 ,-1 , 0
  2603.5     .15       0 3847.92     .05       0 3877.74     .15       0
  4917.5     .05       0  5082.5     .15       0
Bank Sta=4917.5,5082.5
XS Rating Curve= 0 ,0
Exp/Cntr=0.3,0.1

Type RM Length L Ch R = 1 ,68393   ,470,470,470
BEGIN DESCRIPTION:
Battery Park Rd - DS
END DESCRIPTION:
XS GIS Cut Line= 5
       2433240.3       688342.21      2432959.45       687104.09
      2433232.55       686283.09      2433159.01        685756.7
      2432907.43       685075.48
#Sta/Elev= 30
    2557   37.83 2646.97   37.95 2906.88   33.63 3206.77   30.28 3266.75   30.37
 3346.72   27.85 3546.65   23.86  3666.6   24.49 3706.59    20.2 3716.59   20.05
 3786.56   20.36 3836.49   24.11    3931   17.95    4163   20.34    4640   19.93
    4755   17.83    4952   18.46    4960    7.74    4998    7.03    5042    8.12
    5048   18.98  5174.1   20.55 5203.63   28.25 5243.21   33.87  5263.1    34.7
 5432.21   31.47 5551.58   31.89 5720.69   35.45 5830.12   40.16 5949.49      42
#Mann= 3 ,-1 , 0
    2557     .15       0    4952     .05       0    5048     .15       0
Bank Sta=4952,5048
XS Rating Curve= 0 ,0
Exp/Cntr=0.3,0.1

Type RM Length L Ch R = 1 ,67923   ,1384,1384,1384
BEGIN DESCRIPTION:
Black Mingo Creek 136.0
END DESCRIPTION:
XS GIS Cut Line= 3
        2433620.       689414.69       2433654.5       685944.91
      2433571.35       684170.71
#Sta/Elev= 30
  1507.7   42.29  1827.7   37.29  2137.7      37  2197.7   34.92  2287.7   36.68
  2577.7   36.81  2837.7   31.73  3157.7   33.62  3317.7   29.85  3357.7   29.89
  3377.7   31.73  3397.7   29.92  3627.7   25.76  3667.7      20  3727.7   17.46
  4927.7   19.07  4957.7   18.69  4960.2   17.18  4962.4   12.68  5037.6   12.68
  5039.8   17.18  5087.6      20  5117.6   18.54  5197.6   19.92  5357.6   29.64
  5427.6   31.11  6157.6   40.06  6517.6   42.74  6687.6   47.68  6753.8   47.91
#Mann= 3 ,-1 , 0
  1507.7     .15       0  4960.2     .05       0  5039.8     .15       0
Bank Sta=4960.2,5039.8
XS Rating Curve= 0 ,0
Exp/Cntr=0.3,0.1

--- Black Mingo Creek.g05 (geometry) ---

Geom Title=Natural Pre-Scour SCDOT
Program Version=4.10

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
River Reach=Black Mingo Cree,Reach-1

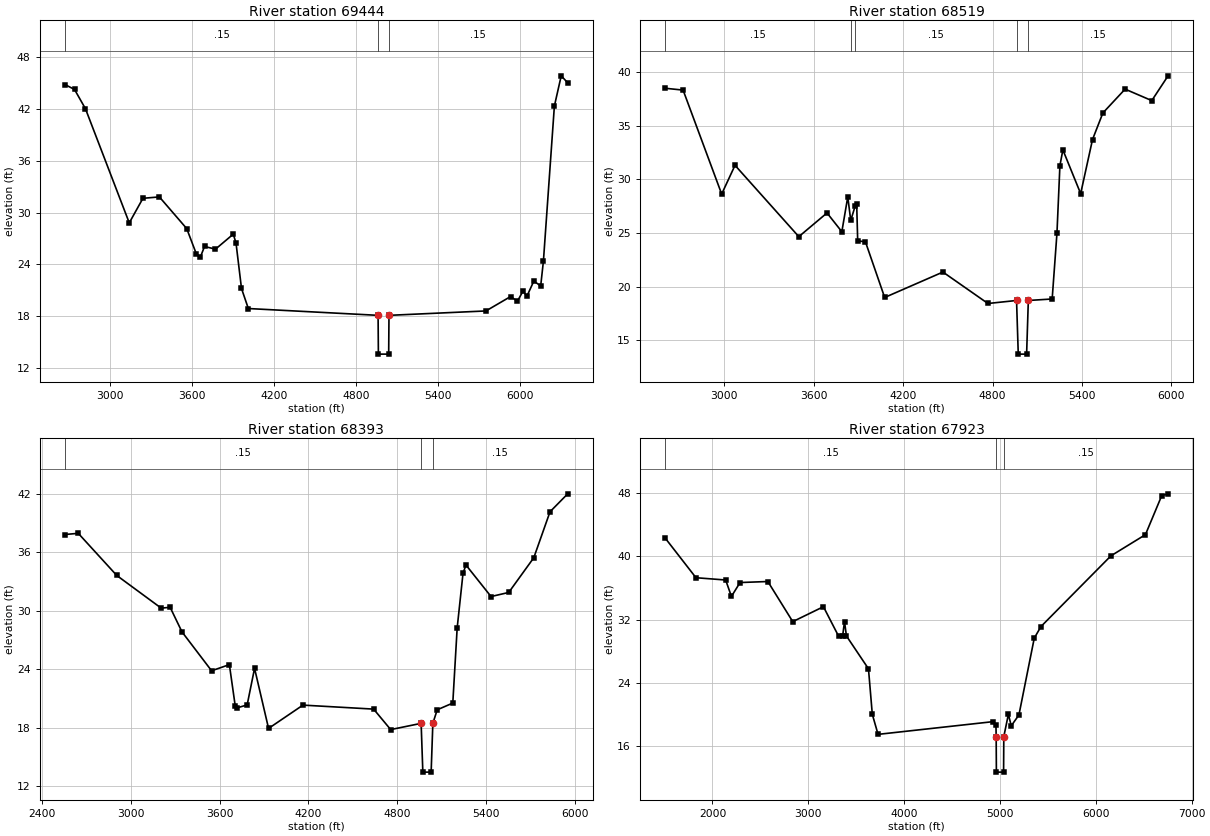
Type RM Length L Ch R = 1 ,69444   ,925,925,925
BEGIN DESCRIPTION:
Black Mingo Creek 140.0
END DESCRIPTION:
XS GIS Cut Line= 3
      2432526.37       688887.18      2432531.63       686551.21
      2432526.53       685213.79
#Sta/Elev= 30
  2672.2   44.85  2742.2   44.28  2822.2   42.04  3142.2    28.8  3242.2   31.65
  3362.2   31.81  3562.2   28.13  3632.2    25.2  3662.2   24.85  3692.2   26.06
  3772.2   25.75  3902.2   27.49  3922.2   26.46  3962.2   21.19  4012.2   18.86
  4960.2   18.07  4962.4   13.57  5037.6   13.57  5039.8   18.07  5748.2   18.58
  5928.2   20.25  5978.2   19.71  6018.2   20.86  6048.2   20.31  6098.2   22.05
  6148.2   21.48  6168.2   24.38  6248.2   42.35  6298.2   45.86  6345.6   45.05
#Mann= 3 ,-1 , 0
  2672.2     .15       0  4960.2     .05       0  5039.8     .15       0
Bank Sta=4960.2,5039.8
XS Rating Curve= 0 ,0
Exp/Cntr=0.3,0.1

Type RM Length L Ch R = 1 ,68519   ,126,126,126
BEGIN DESCRIPTION:
Battery Park Rd - US
END DESCRIPTION:
XS GIS Cut Line= 5
      2433143.53        688353.8      2432850.46       687123.91
      2433112.57       686271.48       2433042.9       685814.76
      2432779.69       685106.43
#Sta/Elev= 30
  2603.5    38.5 2722.96   38.33  2981.8   28.64  3071.4   31.32 3499.48   24.67
 3688.64   26.88 3788.19   25.13 3828.01   28.38 3847.92   26.18 3877.74   27.53
 3887.65   27.75  3894.5   24.28  3946.5   24.19  4075.5      19  4466.5   21.37
  4768.5   18.44  4960.5   18.72    4972   13.72    5028   13.72  5039.5   18.72
  5199.5   18.86 5231.59   24.98 5251.47   31.29 5271.35   32.76 5390.66   28.68
 5470.19   33.72 5539.78    36.2 5688.91   38.42 5867.86   37.35 5977.22   39.66
#Mann= 5 ,-1 , 0
  2603.5     .15       0 3847.92     .05       0 3877.74     .15       0
  4960.5     .05       0  5039.5     .15       0
Bank Sta=4960.5,5039.5
XS Rating Curve= 0 ,0
Exp/Cntr=0.3,0.1

Type RM Length L Ch R = 1 ,68393   ,470,470,470
BEGIN DESCRIPTION:
Battery Park Rd - DS
END DESCRIPTION:
XS GIS Cut Line= 5
       2433240.3       688342.21      2432959.45       687104.09
      2433232.55       686283.09      2433159.01        685756.7
      2432907.43       685075.48
#Sta/Elev= 30
    2557   37.83 2646.97   37.95 2906.88   33.63 3206.77   30.28 3266.75   30.37
 3346.72   27.85 3546.65   23.86  3666.6   24.49 3706.59    20.2 3716.59   20.05
 3786.56   20.36 3836.49   24.11    3931   17.95    4163   20.34    4640   19.93
    4755   17.83  4960.5   18.47    4972   13.47    5028   13.47  5039.5   18.47
    5069   19.86  5174.1   20.55 5203.63   28.25 5243.21   33.87  5263.1    34.7
 5432.21   31.47 5551.58   31.89 5720.69   35.45 5830.12   40.16 5949.49      42
#Mann= 3 ,-1 , 0
    2557     .15       0  4960.5     .05       0  5039.5     .15       0
Bank Sta=4960.5,5039.5
XS Rating Curve= 0 ,0
Exp/Cntr=0.3,0.1

Type RM Length L Ch R = 1 ,67923   ,1384,1384,1384
BEGIN DESCRIPTION:
Black Mingo Creek 136.0
END DESCRIPTION:
XS GIS Cut Line= 3
        2433620.       689414.69       2433654.5       685944.91
      2433571.35       684170.71
#Sta/Elev= 30
  1507.7   42.29  1827.7   37.29  2137.7      37  2197.7   34.92  2287.7   36.68
  2577.7   36.81  2837.7   31.73  3157.7   33.62  3317.7   29.85  3357.7   29.89
  3377.7   31.73  3397.7   29.92  3627.7   25.76  3667.7      20  3727.7   17.46
  4927.7   19.07  4957.7   18.69  4960.2   17.18  4962.4   12.68  5037.6   12.68
  5039.8   17.18  5087.6      20  5117.6   18.54  5197.6   19.92  5357.6   29.64
  5427.6   31.11  6157.6   40.06  6517.6   42.74  6687.6   47.68  6753.8   47.91
#Mann= 3 ,-1 , 0
  1507.7     .15       0  4960.2     .05       0  5039.8     .15       0
Bank Sta=4960.2,5039.8
XS Rating Curve= 0 ,0
Exp/Cntr=0.3,0.1